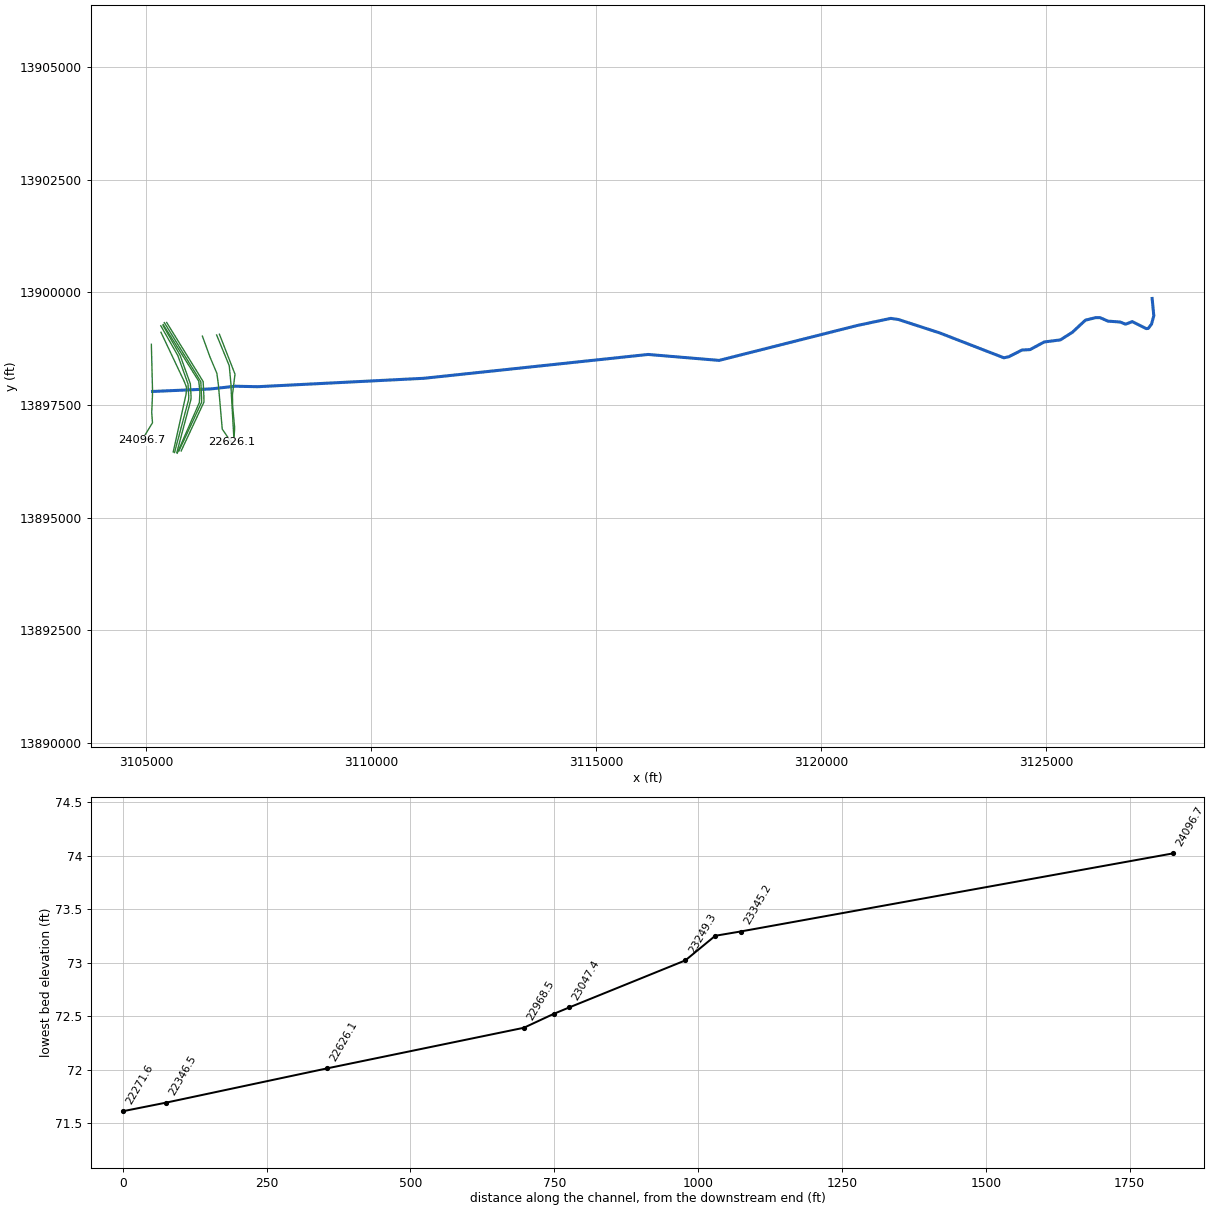
--- P138-00-00.prj (project) ---

Proj Title=P138-00-00
Current Plan=p02
Default Exp/Contr=.3,.1
English Units
Geom File=g01
Flow File=f01
Flow File=f02
Plan File=p01
Plan File=p02
Y Axis Title=Elevation
X Axis Title(PF)=Main Channel Distance
X Axis Title(XS)=Station
BEGIN DESCRIPTION:
The Greens Bayou Watershed
Tributary 24.97 to Greens Bayou
HCFCD Unit P138-00-00
Flood Hazard Model
10, 2, 1, 0.2% Event
Filename P138-00-00.prj
Prepared by:  Watershed Concepts  Date:
Reviewed by:                      Date:
STATUS FINAL
END DESCRIPTION:
DSS File=dss
DSS Export Rating Curves= 0
DSS Export Rating Curve Sorted= 0
DSS Export Volume Flow Curves= 0
DXF OffsetX= 0
DXF OffsetY= 0
DXF ScaleX= 1
DXF ScaleY= 10

--- P138-00-00.p02 (plan) ---

Plan Title=Effective FW 2011
Version=Version 3.0.1  May 2012
Short Identifier=Eff+LOMR FW
Geom File=g01
Flow File=f02
Subcritical Flow
K Sum by GR= 0
Std Step Tol= 0.01
Critical Tol= 0.01
Num of Std Step Trials= 20
Max Error Tol= 0.3
Flow Tol Ratio= 0.001
Split Flow NTrial= 30
Split Flow Tol= 0.02
Split Flow Ratio= 0.02
Log Output Level= 0
Friction Slope Method= 1
Unsteady Friction Slope Method= 2
Parabolic Critical Depth
Global Vel Dist= 0 , 0 , 0
Global Log Level= 0
CheckData=True
Encroach Param=-1 ,0,0, 2
Encroach River=P138-00-00
Encroach Reach=Reach - 1
Encroach Node=24096.7
       1    4580    5090
Encroach Node=23345.2
       1    4830    5070
Encroach Node=23301.3
       1    4840    5070
Encroach Node=23275.3
       1    4840    5070
Encroach Node=23249.3
       1    4840    5070
Encroach Node=23047.4
       1  4953.2    5070
Encroach Node=23020.5
       1  4982.4    5070
Encroach Node=22994.5
       1  4982.4    5070
Encroach Node=22968.5
       1  4982.4    5070
Encroach Node=22626.1
       1    4915    5045
Encroach Node=22346.5
       1    4950    5020
Encroach Node=22271.6
       1    4960    5014
Encroach Node=22011.6
       1    4960    5014
Encroach Node=21751.6
       1    4960    5014
Encroach Node=21380.5
       1  4977.2  5021.2
Encroach Node=20361.9
       1  4974.2    5075
Encroach Node=19624.2
       1  4973.3  5019.3
Encroach Node=18704.8
       1  4970.8  5019.3
Encroach Node=17782.6
       1  4971.5  5040.2
Encroach Node=17630.6
       1  4971.5    5050
Encroach Node=17602.6
       1  4971.5    5050
Encroach Node=17574.6
       1  4971.5    5050
Encroach Node=17042.2
       1    4150    5230
Encroach Node=16376.2
       1    3900    5200
Encroach Node=16257.4
       1    3900    5200
Encroach Node=16229.4
       1    3900    5200
Encroach Node=16201.4
       1    3900    5200
Encroach Node=15673.2
       1    4200    5210
Encroach Node=15066.8
       1    4670    5250
Encroach Node=14908.5
       1    4670    5210
Encroach Node=14882.5
       1    4670    5210
Encroach Node=14856.5
       1    4670    5210
Encroach Node=14058.6
       1    4420    5220
Encroach Node=13571.0
       1    4448    5511
Encroach Node=13069.5
       1    4950    5050
Encroach Node=13043.0
       1    4950    5050
Encroach Node=13016.5
       1    4950    5050
Encroach Node=12961.0
       1  4976.2    5030
Encroach Node=12936.0
       1  4976.2    5030
Encroach Node=12911.0
       1  4976.2    5030
Encroach Node=12828.8
       1  4978.5  5020.5
Encroach Node=12767.8
       1  4978.5  5020.5
Encroach Node=12706.8
       1  4978.5  5020.5
Encroach Node=12515.4
       1    4970    5022
Encroach Node=11628.9
       1    4850    5150
Encroach Node=11565.1
       1    4900    5100
Encroach Node=11538.1
       1    4900    5100
Encroach Node=11511.1
       1    4900    5100
Encroach Node=10669.0
       1    4900    5100
Encroach Node=10331.4
       1    4840    5150
Encroach Node=10219.5
       1    4840    5150
Encroach Node=10192.5
       1    4840    5150
Encroach Node=10165.5
       1    4840    5150
Encroach Node=9959.7
       1    4935    5050
Encroach Node=9003.0
       1    4660    5021
Encroach Node=8883.4
       1    4600    5028
Encroach Node=8856.4
       1    4600    5028
Encroach Node=8829.4
       1    4600    5028
Encroach Node=8566.8
       1    4568  5076.5
Encroach Node=7532.8
       1    4700    5589
Encroach Node=6856.2
       1    4500    5495
Encroach Node=6311.7
       1    4520    5630
Encroach Node=6213.1
       1    4500    5562
Encroach Node=6189.6
       1    4500    5562
Encroach Node=6166.1
       1    4500    5562
Encroach Node=5726.0
       1    4500    5405
Encroach Node=4838.1
       1    4200    5165
Encroach Node=4116.9
       1    4380    5125
Encroach Node=3399.5
       1    4470    5080
Encroach Node=3033.3
       1    4814    5066
Encroach Node=2585.7
       1    4744    5057
Encroach Node=1766.0
       1    4975  5038.2
Encroach Node=1307.3
       1  4945.9    5032
Encroach Node=676.2
       1  4965.6    5032
Encroach Reach=P138-00-00_0007
Encroach Node=24096.7
       1    4580    5090
Encroach Node=23345.2
       1    4830    5070
Encroach Node=23301.3
       1    4840    5070
Encroach Node=23275.3
       1    4840    5070
Encroach Node=23249.3
       1    4840    5070
Encroach Node=23047.4
       1  4953.2    5070
Encroach Node=23020.5
       1  4982.4    5070
Encroach Node=22994.5
       1  4982.4    5070
Encroach Node=22968.5
       1  4982.4    5070
Encroach Node=22626.1
       1    4915    5045
Encroach Node=22346.5
       1    4950    5020
Encroach Node=22271.6
       1    4960    5014
Encroach Node=22011.6
       1    4960    5014
Encroach Node=21751.6
       1    4960    5014
Encroach Node=21380.5
       1  4977.2  5021.2
Encroach Node=20361.9
       1  4974.2    5075
Encroach Node=19624.2
       1  4973.3  5019.3
Encroach Node=18704.8
       1  4970.8  5019.3
Encroach Node=17782.6
       1  4971.5  5040.2
Encroach Node=17630.6
       1  4971.5    5050
Encroach Node=17602.6
       1  4971.5    5050
Encroach Node=17574.6
       1  4971.5    5050
Encroach Node=17042.2
       1    4150    5230
Encroach Node=16376.2
       1    3900    5200
Encroach Node=16257.4
       1    3900    5200
Encroach Node=16229.4
       1    3940    5160
Encroach Node=16201.4
       1    3900    5200
Encroach Node=15673.2
       1    4200    5210
Encroach Node=15066.8
       1    4670    5250
Encroach Node=14908.5
       1    4670    5210
Encroach Node=14882.5
       1    4670    5210
Encroach Node=14856.5
       1    4670    5210
Encroach Node=14058.6
       1    4617    5220
Encroach Node=13571.0
       1    4682    5163
Encroach Node=13069.5
       1    4950    5046
Encroach Node=13043.0
       1    4950    5050
Encroach Node=13016.5
       1    4950    5050
Encroach Node=12961.0
       1  4976.2    5030
Encroach Node=12936.0
       1  4976.2    5030
Encroach Node=12911.0
       1  4976.2    5030
Encroach Node=12828.8
       1  4978.5  5020.5
Encroach Node=12767.8
       1  4978.5  5020.5
Encroach Node=12706.8
       1  4978.5  5020.5
Encroach Node=12515.4
       1    4970    5022
Encroach Node=11628.9
       1    4850    5150
Encroach Node=11565.1
       1    4900    5100
Encroach Node=11538.1
       1    4900    5100
Encroach Node=11511.1
       1    4900    5100
Encroach Node=10669.0
       1    4900    5100
Encroach Node=10331.4
       1    4840    5150
Encroach Node=10219.5
       1    4840    5150
Encroach Node=10192.5
       1    4840    5150
Encroach Node=10165.5
       1    4840    5150
Encroach Node=9959.7
       1    4935    5050
Encroach Node=9003.0
       1    4660    5021
Encroach Node=8883.4
       1    4600    5028
Encroach Node=8856.4
       1    4600    5028
Encroach Node=8829.4
       1    4600    5028
Encroach Node=8566.8
       1    4568  5076.5
Encroach Node=7532.8
       1    4700    5589
Encroach Node=6856.2
       1    4500    5495
Encroach Node=6311.7
       1    4520    5630
Encroach Node=6213.1
       1    4500    5562
Encroach Node=6189.6
       1    4500    5562
Encroach Node=6166.1
       1    4500    5562
Encroach Node=5726.0
       1    4500    5405
Encroach Node=4838.1
       1    4200    5165
Encroach Node=4116.9
       1    4380    5125
Encroach Node=3399.5
       1    4470    5080
Encroach Node=3033.3
       1    4814    5066
Encroach Node=2585.7
       1    4744    5057
Encroach Node=1766.0
       1    4975  5038.2
Encroach Node=1307.3
       1  4945.9    5032
Encroach Node=676.2
       1  4965.6    5032
BEGIN DESCRIPTION:
FEMA Effective Floodway 2007 + LOMR 11-06-0975P
END DESCRIPTION:
Computation Interval=1HOUR
Output Interval=1HOUR
Run HTab= 0
Run UNet= 0
Run PostProcess= 0
UNET Theta= 1
UNET ZTol= 0.02
UNET ZSATol= 0.1
UNET MxIter= 20
UNET MaxInSteps= 20
UNET DtIC= 0
UNET DtMin= 0
UNET MaxCRTS= 20
UNET WFStab= 2
UNET SFStab= 1
UNET WFX= 1
UNET SFX= 1
UNET Convert EG Bridges=-1
UNET Use Existing IB Tables=-1
Instantaneous Interval=1HOUR
DSS File=dss
Write IC File= 0
Write Velocity= 0
Write Detailed= 0

--- P138-00-00.p01 (plan) ---

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Plan Title=Effective MP 2011
Short Identifier=Eff+LOMR MP
Geom File=g01
Flow File=f01
Encroach Param=-1 ,0,0, 0
FEMA Effective Multi-Profile 2007 + LOMR 11-06-0975P

--- P138-00-00.f02 (steady flow) ---

Flow Title= Effective FW 2011
Number of Profiles= 2
Profile Names=1PCT_100yr, 1PCTFloodway_100yr
River Rch & RM=P138-00-00,P138-00-00_0007,24096.7
     563     563
River Rch & RM=P138-00-00,P138-00-00_0007,23020.5
     586     586
River Rch & RM=P138-00-00,P138-00-00_0007,22626.1
     611     611
River Rch & RM=P138-00-00,P138-00-00_0007,22271.6
     678     678
River Rch & RM=P138-00-00,P138-00-00_0007,21380.5
     764     764
River Rch & RM=P138-00-00,P138-00-00_0007,20361.9
     832     832
River Rch & RM=P138-00-00,P138-00-00_0007,19624.2
     927     927
River Rch & RM=P138-00-00,P138-00-00_0007,18704.8
     983     983
River Rch & RM=P138-00-00,P138-00-00_0007,17782.6
     996     996
River Rch & RM=P138-00-00,P138-00-00_0007,17630.6
    1030    1030
River Rch & RM=P138-00-00,P138-00-00_0007,17042.2
    1075    1075
River Rch & RM=P138-00-00,P138-00-00_0007,16376.2
    1087    1087
River Rch & RM=P138-00-00,P138-00-00_0007,16257.4
    1124    1124
River Rch & RM=P138-00-00,P138-00-00_0007,15673.2
    1169    1169
River Rch & RM=P138-00-00,P138-00-00_0007,15066.8
    1185    1185
River Rch & RM=P138-00-00,P138-00-00_0007,14908.5
    1246    1246
River Rch & RM=P138-00-00,P138-00-00_0007,14058.6
    1286    1286
River Rch & RM=P138-00-00,P138-00-00_0007,13571
    1328    1328
River Rch & RM=P138-00-00,P138-00-00_0007,13069.5
    1341    1341
River Rch & RM=P138-00-00,P138-00-00_0007,12961
    1367    1367
River Rch & RM=P138-00-00,P138-00-00_0007,12515.4
    1427    1427
River Rch & RM=P138-00-00,P138-00-00_0007,11628.9
    1495    1495
River Rch & RM=P138-00-00,P138-00-00_0007,10669
    1547    1547
River Rch & RM=P138-00-00,P138-00-00_0007,9959.7
    1620    1620
River Rch & RM=P138-00-00,P138-00-00_0007,9003
    1654    1654
River Rch & RM=P138-00-00,P138-00-00_0007,8566.8
    1739    1739
River Rch & RM=P138-00-00,P138-00-00_0007,7532.8
    1797    1797
River Rch & RM=P138-00-00,P138-00-00_0007,6856.2
    1845    1845
River Rch & RM=P138-00-00,P138-00-00_0007,6311.7
    1898    1898
River Rch & RM=P138-00-00,P138-00-00_0007,5726
    1981    1981
River Rch & RM=P138-00-00,P138-00-00_0007,4838.1
    2051    2051
River Rch & RM=P138-00-00,P138-00-00_0007,4116.9
    2123    2123
River Rch & RM=P138-00-00,P138-00-00_0007,3399.5
    2208    2208
River Rch & RM=P138-00-00,P138-00-00_0007,2585.7
    2297    2297
River Rch & RM=P138-00-00,P138-00-00_0007,1766
    2349    2349
River Rch & RM=P138-00-00,P138-00-00_0007,1307.3
    2941    2941
Boundary for River Rch & Prof#=P138-00-00,P138-00-00_0007, 1
Up Type= 0
Dn Type= 3
Dn Slope= 0.00240
Boundary for River Rch & Prof#=P138-00-00,P138-00-00_0007, 2
Up Type= 0
Dn Type= 1
Dn Known WS=60.27

--- P138-00-00.f01 (steady flow) ---

Flow Title= Effective MP 2011
Number of Profiles= 4
Profile Names=10PCT_10yr, 2PCT_50yr, 1PCT_100yr, 0.2PCT_500yr
River Rch & RM=P138-00-00,P138-00-00_0007,24096.7
     319     480     563     811
River Rch & RM=P138-00-00,P138-00-00_0007,23020.5
     332     500     586     844
River Rch & RM=P138-00-00,P138-00-00_0007,22626.1
     346     521     611     880
River Rch & RM=P138-00-00,P138-00-00_0007,22271.6
     384     578     678     976
River Rch & RM=P138-00-00,P138-00-00_0007,21380.5
     432     651     764    1099
River Rch & RM=P138-00-00,P138-00-00_0007,20361.9
     471     709     832    1198
River Rch & RM=P138-00-00,P138-00-00_0007,19624.2
     524     790     927    1333
River Rch & RM=P138-00-00,P138-00-00_0007,18704.8
     557     837     983    1376
River Rch & RM=P138-00-00,P138-00-00_0007,17782.6
     565     848     996    1385
River Rch & RM=P138-00-00,P138-00-00_0007,17630.6
     585     877    1030    1410
River Rch & RM=P138-00-00,P138-00-00_0007,17042.2
     612     914    1075    1443
River Rch & RM=P138-00-00,P138-00-00_0007,16376.2
     619     924    1087    1451
River Rch & RM=P138-00-00,P138-00-00_0007,16257.4
     641     955    1124    1477
River Rch & RM=P138-00-00,P138-00-00_0007,15673.2
     667     992    1169    1508
River Rch & RM=P138-00-00,P138-00-00_0007,15066.8
     677    1006    1185    1518
River Rch & RM=P138-00-00,P138-00-00_0007,14908.5
     714    1057    1246    1560
River Rch & RM=P138-00-00,P138-00-00_0007,14058.6
     737    1090    1286    1586
River Rch & RM=P138-00-00,P138-00-00_0007,13571
     762    1125    1328    1613
River Rch & RM=P138-00-00,P138-00-00_0007,13069.5
     770    1136    1341    1622
River Rch & RM=P138-00-00,P138-00-00_0007,12961
     786    1159    1367    1657
River Rch & RM=P138-00-00,P138-00-00_0007,12515.4
     822    1211    1427    1740
River Rch & RM=P138-00-00,P138-00-00_0007,11628.9
     864    1270    1495    1834
River Rch & RM=P138-00-00,P138-00-00_0007,10669
     896    1315    1547    1907
River Rch & RM=P138-00-00,P138-00-00_0007,9959.7
     940    1379    1620    2010
River Rch & RM=P138-00-00,P138-00-00_0007,9003
     962    1410    1654    2058
River Rch & RM=P138-00-00,P138-00-00_0007,8566.8
    1014    1484    1739    2178
River Rch & RM=P138-00-00,P138-00-00_0007,7532.8
    1049    1535    1797    2261
River Rch & RM=P138-00-00,P138-00-00_0007,6856.2
    1079    1577    1845    2329
River Rch & RM=P138-00-00,P138-00-00_0007,6311.7
    1112    1623    1898    2406
River Rch & RM=P138-00-00,P138-00-00_0007,5726
    1163    1696    1981    2526
River Rch & RM=P138-00-00,P138-00-00_0007,4838.1
    1207    1758    2051    2628
River Rch & RM=P138-00-00,P138-00-00_0007,4116.9
    1252    1822    2123    2733
River Rch & RM=P138-00-00,P138-00-00_0007,3399.5
    1305    1897    2208    2858
River Rch & RM=P138-00-00,P138-00-00_0007,2585.7
    1361    1976    2297    2990
River Rch & RM=P138-00-00,P138-00-00_0007,1766
    1393    2021    2349    3066
River Rch & RM=P138-00-00,P138-00-00_0007,1307.3
    1766    2547    2941    3958
Boundary for River Rch & Prof#=P138-00-00,P138-00-00_0007, 1
Up Type= 0
Dn Type= 3
Dn Slope= 0.00240
Boundary for River Rch & Prof#=P138-00-00,P138-00-00_0007, 2
Up Type= 0
Dn Type= 3
Dn Slope= 0.00240
Boundary for River Rch & Prof#=P138-00-00,P138-00-00_0007, 3
Up Type= 0
Dn Type= 3
Dn Slope= 0.00240
Boundary for River Rch & Prof#=P138-00-00,P138-00-00_0007, 4
Up Type= 0
Dn Type= 3
Dn Slope= 0.00240

--- P138-00-00.g01 (geometry) ---

Geom Title=P138-00-00 2011
Version=Version 3.0.1  May 2012

River Reach=P138-00-00      ,P138-00-00_0007
Reach XY= 30
       3105148.3     13897802.28        3106446.       13897859.
      3106987.75       13897919.        3107484.       13897908.
        3111181.       13898095.       3116162.5       13898624.
      3117739.25       13898492.        3120805.       13899266.
       3121554.5       13899425.      3121724.25       13899400.
       3122639.5       13899103.      3124067.75       13898550.
      3124174.75       13898572.      3124469.25       13898722.
      3124650.25       13898732.      3124966.75       13898902.
      3125322.75       13898947.        3125589.       13899115.
      3125880.35     13899385.71      3126105.39     13899441.05
      3126204.66     13899441.05      3126381.75       13899364.
        3126653.       13899344.       3126771.5       13899296.
       3126921.5       13899353.      3127231.81     13899197.94
      3127276.39     13899201.99        3127349.       13899297.
      3127399.97      13899483.6       3127362.5       13899867.

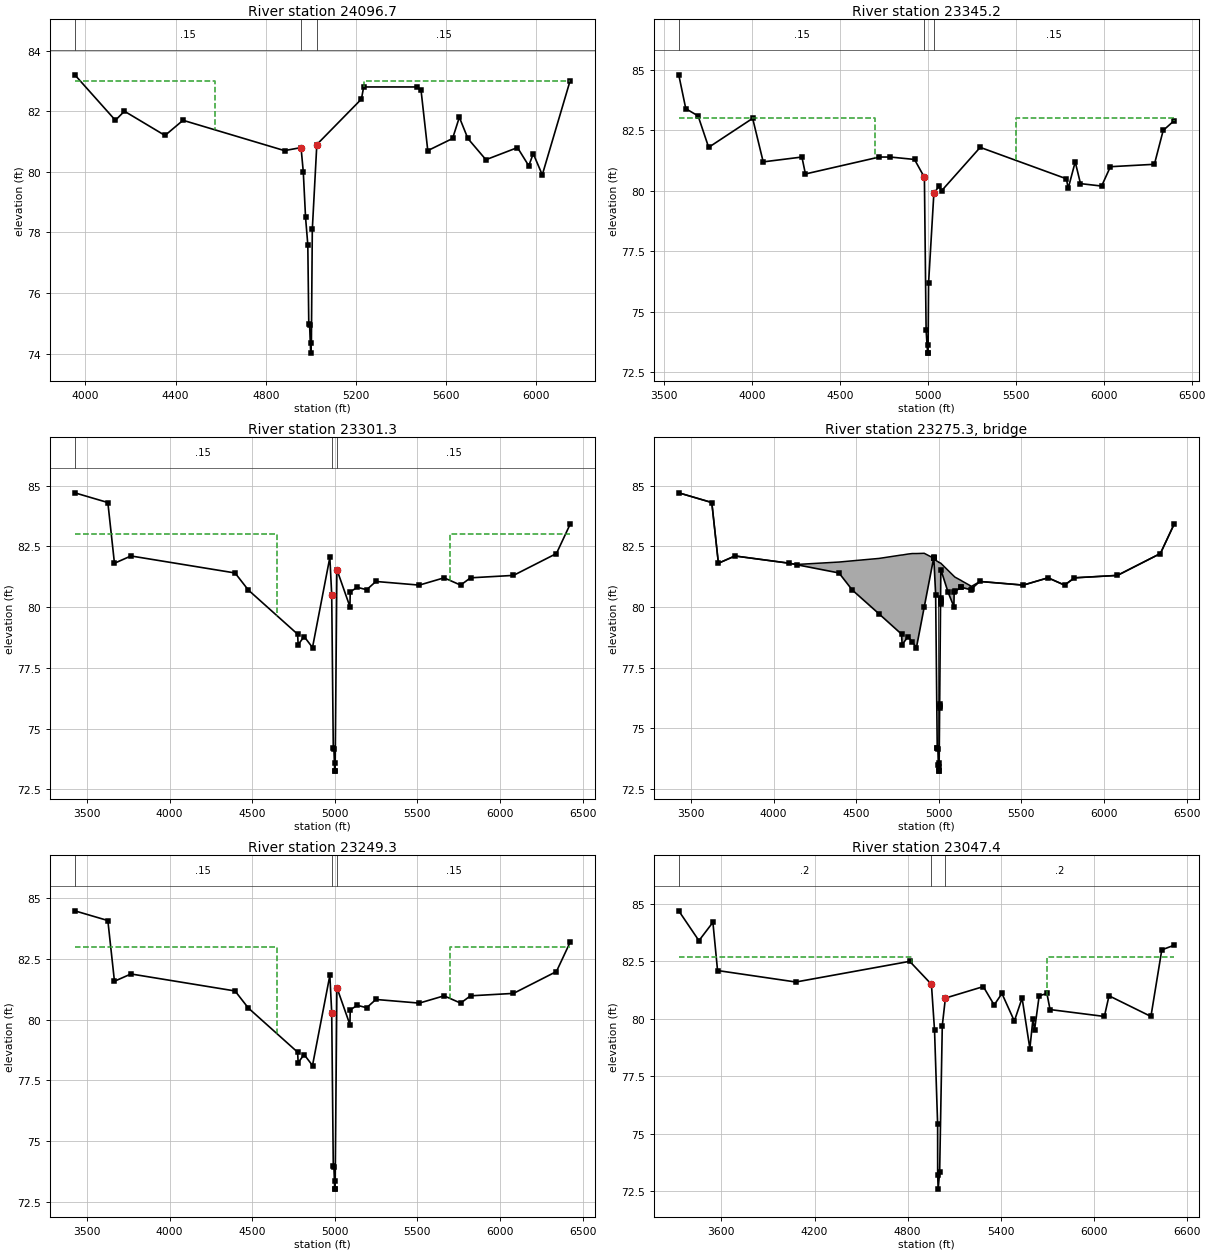
Type RM Length L Ch R = 1 ,24096.7 ,630.8,751.5,691.4
BEGIN DESCRIPTION:
Cross Section 24096.7-Interpolated
END DESCRIPTION:
XS GIS Cut Line= 6
      3105123.09     13898848.88      3105148.33     13897855.88
      3105148.33     13897738.07       3105131.5     13897334.14
      3105148.33     13897106.93       3104912.7     13896719.83
#Sta/Elev= 30
  3953.1    83.2  4133.1    81.7  4173.1      82  4353.1    81.2  4433.1    81.7
  4883.1    80.7  4956.4    80.8  4966.4      80  4976.4    78.5  4986.4    77.6
  4990.8   74.97  4994.5   74.94  4999.2   74.02  5002.3   74.34  5006.4    78.1
  5026.4    80.9  5224.2    82.4  5234.2    82.8  5468.5    82.8  5488.5    82.7
  5518.5    80.7  5628.5    81.1  5658.5    81.8  5696.3    81.1  5776.3    80.4
  5916.3    80.8  5966.3    80.2  5986.3    80.6  6026.3    79.9  6149.5      83
#Mann= 3 , 1 , 0
  3953.1     .15       0  4956.4     .04       0  5026.4     .15       0
#XS Ineff= 2 , 0
       0    4575      83    5235       0      83
Permanent Ineff=
       F       F
Bank Sta=4956.4,5026.4
XS Rating Curve= 0
Exp/Cntr=.3,.1

Type RM Length L Ch R = 1 ,23345.2 ,42.1,43.9,77.9
BEGIN DESCRIPTION:
Cross Section 23345.2-Interpolated
END DESCRIPTION:
XS GIS Cut Line= 5
      3105336.64     13899116.01      3105851.38     13898029.33
      3105902.47     13897901.62      3105896.08     13897748.37
      3105608.74     13896458.51
#Sta/Elev= 30
  3584.9    84.8  3624.9    83.4  3694.9    83.1  3754.9    81.8  4004.9      83
  4064.9    81.2  4284.9    81.4  4304.9    80.7  4724.9    81.4  4787.4    81.4
  4924.9    81.3  4981.1   80.56  4990.8   74.24  4999.2   73.29  5000.2   73.29
  5002.3   73.61  5004.9    76.2  5034.9    79.9  5064.9    80.2  5078.3      80
  5298.3    81.8  5788.3    80.5  5798.3    80.1  5838.3    81.2  5868.3    80.3
  5988.3    80.2  6038.3      81  6288.3    81.1  6338.3    82.5  6399.8    82.9
#Mann= 3 , 1 , 0
  3584.9     .15       0  4981.1     .04       0  5034.9     .15       0
#XS Ineff= 2 , 0
       0    4700      83    5500       0      83
Permanent Ineff=
       F       F
Bank Sta=4981.1,5034.9
XS Rating Curve= 0
Exp/Cntr=.5,.3

Type RM Length L Ch R = 1 ,23301.3 ,52,52,52
BEGIN DESCRIPTION:
Upstream Section of Bridge/Culvert/Weir
END DESCRIPTION:
XS GIS Cut Line= 6
       3105332.7     13899262.27      3105712.42     13898596.53
      3105937.48      13897970.1      3105954.12     13897687.22
      3105950.36     13897618.25      3105637.88     13896445.87
#Sta/Elev= 30
  3426.1   84.71  3626.1   84.31  3666.1   81.81  3766.1   82.11  4396.1   81.41
  4476.1   80.71  4774.7   78.89  4778.1   78.46  4814.4   78.79  4864.9   78.34
  4969.9   82.05  4981.1   80.52  4990.7    74.2  4994.5   74.17  4999.2   73.25
  5000.2   73.25  5002.3   73.57  5012.5   81.55  5091.5   80.02  5093.2   80.63
  5135.7   80.82  5192.6   80.72  5248.8   81.06  5511.4   80.91  5661.4   81.21
  5761.4   80.91  5821.4   81.21  6081.4   81.31  6341.4   82.21  6423.9   83.41
#Mann= 3 , 1 , 0
  3426.1     .15       0  4981.1     .04       0  5012.5     .15       0
#XS Ineff= 2 , 0
       0    4650      83    5700       0      83
Permanent Ineff=
       F       F
Bank Sta=4981.1,5012.5
XS Rating Curve= 0
Exp/Cntr=.5,.3

Type RM Length L Ch R = 3 ,23275.3 ,,,
BEGIN DESCRIPTION:
ACCESS ROAD 2
Structure ID: P38-19
END DESCRIPTION:
Bridge Culvert--1,0,-1,-1, 0
Deck Dist Width WeirC Skew NumUp NumDn MinLoCord MaxHiCord MaxSubmerge Is_Ogee
10,32,2.6,0, 54, 54, , , .95, 0, 1,1,,
  3426.1  3626.1  3666.1  3766.1  4096.1  4139.3  4396.1  4476.1  4639.3  4774.7
  4778.1  4814.4  4839.3  4864.9  4912.1 4968.77 4968.88 4968.99 4969.21  4969.3
  4969.9  4981.1  4990.7  4990.8  4994.5  4997.6  4999.2  5000.2  5001.7  5002.3
 5005.19  5005.3 5005.41  5010.7  5010.8 5010.89    5011  5012.5  5055.7  5091.5
  5093.2  5097.8  5135.7  5137.4  5192.6  5198.7  5248.8  5511.4  5661.4  5761.4
  5821.4  6081.4  6341.4  6423.9
    84.7    84.3    81.8    82.1    81.8   81.75   81.85    81.9      82   82.14
   82.14   82.18    82.2    82.2   82.21   82.01   82.01   82.02   82.03   82.03
   82.05   81.93   81.88   81.88   81.87   81.85   81.85   81.84   81.84   81.83
   81.82   81.82   81.82   81.81   81.81   81.81   81.81    81.8   81.51   81.27
   81.26   81.23   81.09   81.08   80.87   80.85   81.05    80.9    81.2    80.9
    81.2    81.3    82.2    83.4
    84.7    84.3    81.8    82.1    81.8   81.74    81.4    80.7   79.71   78.88
   78.45   78.78   78.56   78.33      80      82      82   82.01   82.02   82.02
   82.04   80.51   80.38   80.38   80.37   80.35   80.35   80.34   80.34   80.33
   80.32   80.32   80.32   80.31   80.31   80.31   80.37   81.54   80.62   80.01
   80.62   80.64   80.81   80.81   80.71   80.75   81.05    80.9    81.2    80.9
    81.2    81.3    82.2    83.4
  3426.1  3626.1  3666.1  3766.1  4096.1  4139.3  4396.1  4476.1  4639.3  4774.7
  4778.1  4814.4  4839.3  4864.9  4912.1 4968.77 4968.88 4968.99 4969.21  4969.3
  4969.9  4981.1  4990.7  4990.8  4994.5  4997.6  4999.2  5000.2  5001.7  5002.3
 5005.19  5005.3 5005.41  5010.7  5010.8 5010.89    5011  5012.5  5055.7  5091.5
  5093.2  5097.8  5135.7  5137.4  5192.6  5198.7  5248.8  5511.4  5661.4  5761.4
  5821.4  6081.4  6341.4  6423.9
    84.7    84.3    81.8    82.1    81.8   81.75   81.85    81.9      82   82.14
   82.14   82.18    82.2    82.2   82.21   82.01   82.01   82.02   82.03   82.03
   82.05   81.93   81.88   81.88   81.87   81.85   81.85   81.84   81.84   81.83
   81.82   81.82   81.82   81.81   81.81   81.81   81.81    81.8   81.51   81.27
   81.26   81.23   81.09   81.08   80.87   80.85   81.05    80.9    81.2    80.9
    81.2    81.3    82.2    83.4
    84.5    84.1    81.6    81.9    81.6   81.54    81.2    80.5   79.51   78.68
   78.25   78.58   78.36   78.13    79.8    81.8    81.8   81.81   81.82   81.82
   81.84   80.31   80.18   80.18   80.17   80.15   80.15   80.14   80.14   80.13
   80.12   80.12   80.12   80.11   80.11   80.11   80.17   81.34   80.42   79.81
   80.42   80.44   80.61   80.61   80.51   80.55   80.85    80.7      81    80.7
      81    81.1      82    83.2
Pier Skew, UpSta & Num, DnSta & Num=  ,4994.5, 2 ,4994.5, 2 , 0 , 0 , 0 ,,
       2       2
   72.95   81.37
       2       2
   72.75   81.17
Abutment Skew #Up #Dn= , 2 , 2
  4969.1  4990.8
   82.02   74.19
  4969.1  4990.8
   81.82   73.99
BR Coef= 1 , 1 , 0 ,1.25, 0 ,,,.8,0,2,0,
WSPro=,,,, 1 ,,,, 0 ,,,, 0 ,,,,-1 ,-1 ,-1 , 0 , 0 , 0 , 0 , 0
BR U #Sta/Elev= 54
  3426.1    84.7  3626.1    84.3  3666.1    81.8  3766.1    82.1  4096.1    81.8
  4139.3   81.74  4396.1    81.4  4476.1    80.7  4639.3   79.71  4774.7   78.88
  4778.1   78.45  4814.4   78.78  4839.3   78.56  4864.9   78.33  4912.1      80
 4968.77      82 4968.88      82 4968.99   82.01 4969.21   82.02  4969.3   82.02
  4969.9   82.04  4981.1   80.51  4990.7   74.19  4990.8   74.19  4994.5   74.16
  4997.6   73.51  4999.2   73.24  5000.2   73.24  5001.7   73.42  5002.3   73.56
 5005.19   75.82  5005.3   75.91 5005.41   75.99  5010.7   80.13  5010.8   80.21
 5010.89   80.28    5011   80.37  5012.5   81.54  5055.7   80.62  5091.5   80.01
  5093.2   80.62  5097.8   80.64  5135.7   80.81  5137.4   80.81  5192.6   80.71
  5198.7   80.75  5248.8   81.05  5511.4    80.9  5661.4    81.2  5761.4    80.9
  5821.4    81.2  6081.4    81.3  6341.4    82.2  6423.9    83.4
BR U #Mann= 3
  3426.1     .15  4981.1     .04  5012.5     .15
BR U Banks=4981.1,5012.5
BR D #Sta/Elev= 54
  3426.1    84.5  3626.1    84.1  3666.1    81.6  3766.1    81.9  4096.1    81.6
  4139.3   81.54  4396.1    81.2  4476.1    80.5  4639.3   79.51  4774.7   78.68
  4778.1   78.25  4814.4   78.58  4839.3   78.36  4864.9   78.13  4912.1    79.8
 4968.77    81.8 4968.88    81.8 4968.99   81.81 4969.21   81.82  4969.3   81.82
  4969.9   81.84  4981.1   80.31  4990.7   73.99  4990.8   73.99  4994.5   73.96
  4997.6   73.31  4999.2   73.04  5000.2   73.04  5001.7   73.22  5002.3   73.36
 5005.19   75.62  5005.3   75.71 5005.41   75.79  5010.7   79.93  5010.8   80.01
 5010.89   80.08    5011   80.17  5012.5   81.34  5055.7   80.42  5091.5   79.81
  5093.2   80.42  5097.8   80.44  5135.7   80.61  5137.4   80.61  5192.6   80.51
  5198.7   80.55  5248.8   80.85  5511.4    80.7  5661.4      81  5761.4    80.7
  5821.4      81  6081.4    81.1  6341.4      82  6423.9    83.2
BR D #Mann= 3
  3426.1     .15  4981.1     .04  5012.5     .15
BR D Banks=4981.1,5012.5
BC Design=,, 0 ,, 0 ,,,,,,

Type RM Length L Ch R = 1 ,23249.3 ,201.9,201.9,201.9
BEGIN DESCRIPTION:
Downstream Section of Bridge/Culvert/Weir
END DESCRIPTION:
XS GIS Cut Line= 6
      3105384.61     13899265.38      3105764.32     13898599.63
      3105989.38      13897973.2      3106006.02     13897690.32
      3106002.26     13897621.35      3105689.79     13896448.97
#Sta/Elev= 30
  3426.1   84.48  3626.1   84.08  3666.1   81.58  3766.1   81.88  4396.1   81.18
  4476.1   80.48  4774.7   78.66  4778.1   78.23  4814.4   78.56  4864.9   78.11
  4969.9   81.82  4981.1   80.29  4990.7   73.97  4994.5   73.94  4999.2   73.02
  5000.2   73.02  5002.3   73.34  5012.5   81.32  5091.5   79.79  5093.2    80.4
  5135.7   80.59  5192.6   80.49  5248.8   80.83  5511.4   80.68  5661.4   80.98
  5761.4   80.68  5821.4   80.98  6081.4   81.08  6341.4   81.98  6423.9   83.18
#Mann= 3 , 1 , 0
  3426.1     .15       0  4981.1     .04       0  5012.5     .15       0
#XS Ineff= 2 , 0
       0    4650      83    5700       0      83
Permanent Ineff=
       F       F
Bank Sta=4981.1,5012.5
XS Rating Curve= 0
Exp/Cntr=.5,.3

Type RM Length L Ch R = 1 ,23047.4 ,24.8,26.9,35.5
BEGIN DESCRIPTION:
Cross Section 23047.4-Interpolated
END DESCRIPTION:
XS GIS Cut Line= 5
      3105385.75     13899289.31      3106177.04     13898029.33
      3106202.58     13897786.68      3106189.81     13897556.81
      3105697.56     13896430.98
#Sta/Elev= 30
  3325.3    84.7  3455.3    83.4  3545.3    84.2  3575.3    82.1  4079.7    81.6
  4813.2    82.5  4953.2    81.5  4973.2    79.5  4993.2    75.4  4993.5   73.21
  4996.5   72.58  5006.1   73.31  5023.2    79.7  5043.2    80.9  5287.4    81.4
  5357.4    80.6  5407.4    81.1  5487.4    79.9  5537.4    80.9  5587.4    78.7
  5607.4      80  5617.4    79.5  5647.4      81  5697.4    81.1  5717.4    80.4
  6067.4    80.1  6097.4      81  6367.4    80.1  6437.4      83  6516.1    83.2
#Mann= 3 , 1 , 0
  3325.3      .2       0  4953.2     .04       0  5043.2      .2       0
#XS Ineff= 2 , 0
       0    4825    82.7    5700       0    82.7
Permanent Ineff=
       F       F
Bank Sta=4953.2,5043.2
XS Rating Curve= 0
Exp/Cntr=.5,.3

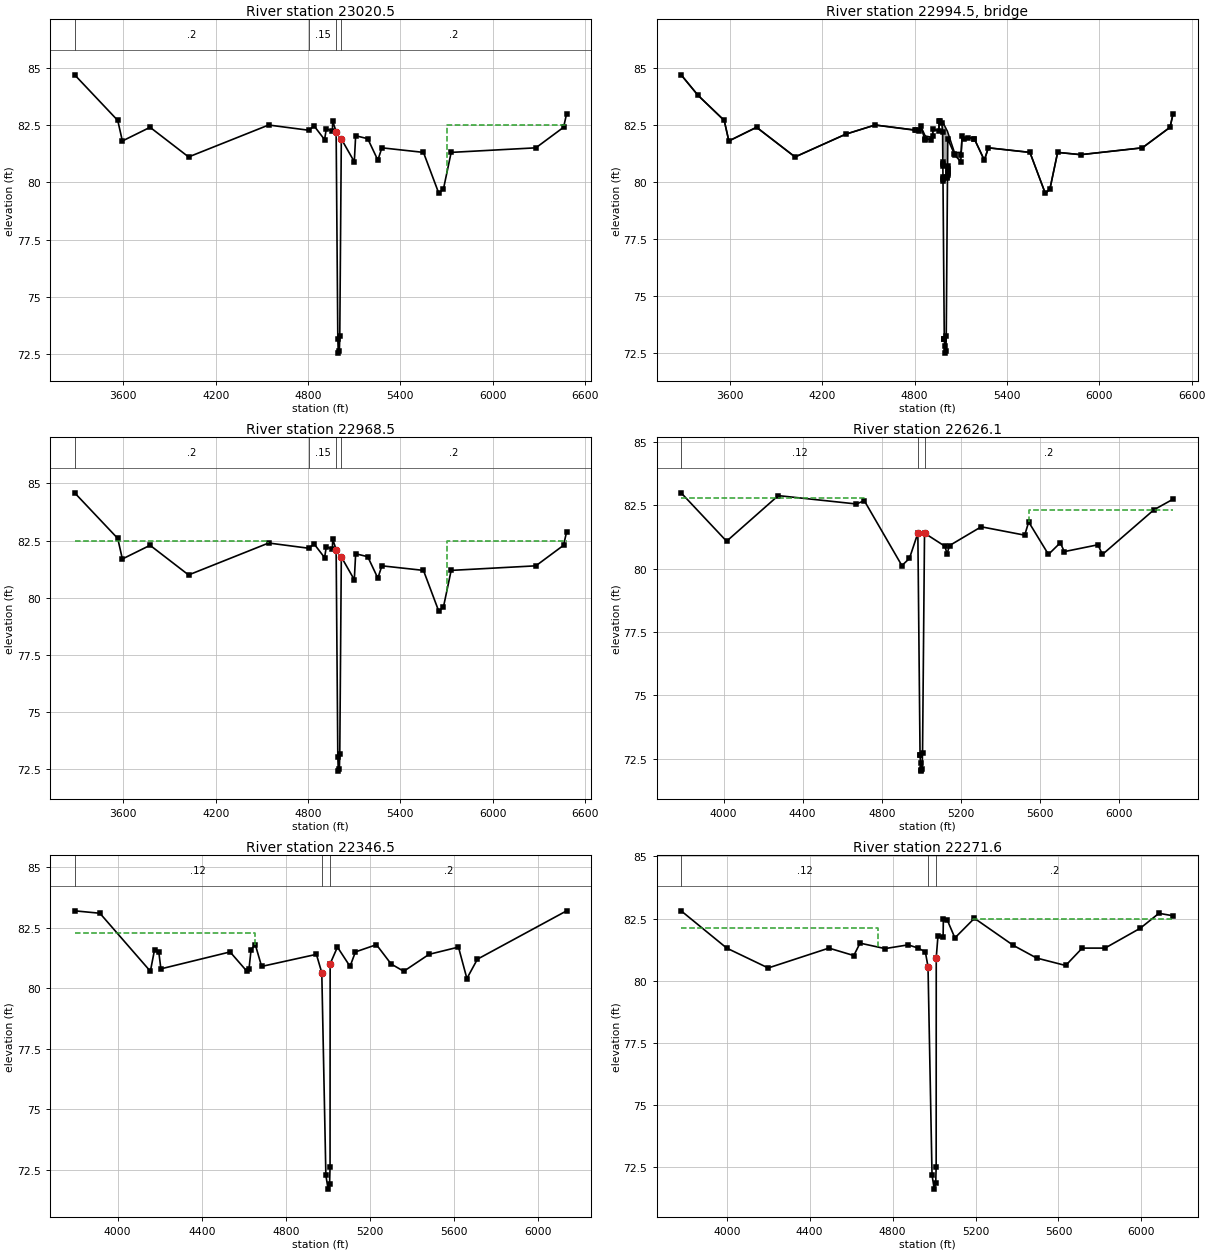
Type RM Length L Ch R = 1 ,23020.5 ,52,52,52
BEGIN DESCRIPTION:
Upstream Section of Bridge/Culvert/Weir
END DESCRIPTION:
XS GIS Cut Line= 5
      3105411.61     13899330.85      3106222.56     13898018.92
      3106237.76     13897697.11      3106240.68       13897565.
      3105733.48     13896478.72
#Sta/Elev= 30
  3284.1   84.72  3564.1   82.72  3594.1   81.82  3774.1   82.42  4024.1   81.12
  4544.1   82.52    4805   82.29  4839.2   82.48  4907.4   81.88  4918.9   82.36
  4957.9   82.24  4960.2   82.69  4982.4   82.23  4993.4   73.15  4996.5   72.52
  5003.4   72.61  5006.1   73.25  5016.1   81.91  5100.5   80.91  5109.2   82.05
  5187.7   81.92  5253.4   80.98  5279.6   81.52  5549.6   81.32  5649.6   79.52
  5679.6   79.72  5729.6   81.32  6279.6   81.52  6459.6   82.42  6479.6   83.02
#Mann= 4 , 1 , 0
  3284.1      .2       0    4805     .15       0  4982.4     .04       0
  5016.1      .2       0
#XS Ineff= 2 , 0
       0    4542    82.5    5700       0    82.5
Permanent Ineff=
       F       F
Bank Sta=4982.4,5016.1
XS Rating Curve= 0
Exp/Cntr=.5,.3

Type RM Length L Ch R = 3 ,22994.5 ,,,
BEGIN DESCRIPTION:
ACCESS ROAD 1
Structure ID: P38-18
END DESCRIPTION:
Bridge Culvert--1,0,-1,-1, 0
Deck Dist Width WeirC Skew NumUp NumDn MinLoCord MaxHiCord MaxSubmerge Is_Ogee
10,32,2.6,0, 41, 41, , , .95, 0, 1,1,,
  3284.1  3394.1  3564.1  3594.1  3774.1  4024.1  4354.1  4544.1  4830.7  4839.2
  4869.7  4871.1  4907.4  4918.2  4918.9  4957.9  4960.2  4976.9  4982.4 4984.81
  4984.9 5014.19  5014.3  5016.1  5059.5  5100.5  5102.9  5109.2  5121.1  5147.9
  5187.7  5253.4  5279.6  5549.6  5649.6  5679.6  5729.6  5879.6  6279.6  6459.6
  6479.6
    84.7    83.8    82.7    81.8    82.4    81.1    82.1    82.5   82.26   82.47
   82.02   82.02   81.97   82.04   82.35   82.23   82.68   82.61   82.56   82.61
   82.61   82.22   82.22   82.18    81.3    81.3    81.3   82.04   81.89   81.96
   81.91   80.96    81.5    81.3    79.5    79.7    81.3    81.2    81.5    82.4
      83
    84.7    83.8    82.7    81.8    82.4    81.1    82.1    82.5   82.25   82.46
   81.83   81.89   81.86   82.03   82.34   82.22   82.67    82.6   82.21   80.22
   81.11   80.72   80.33   81.89   81.22   80.89    81.2   82.03   81.88   81.95
    81.9   80.96    81.5    81.3    79.5    79.7    81.3    81.2    81.5    82.4
      83
  3284.1  3394.1  3564.1  3594.1  3774.1  4024.1  4354.1  4544.1  4830.7  4839.2
  4869.7  4871.1  4907.4  4918.2  4918.9  4957.9  4960.2  4976.9  4982.4 4984.81
  4984.9 5014.19  5014.3  5016.1  5059.5  5100.5  5102.9  5109.2  5121.1  5147.9
  5187.7  5253.4  5279.6  5549.6  5649.6  5679.6  5729.6  5879.6  6279.6  6459.6
  6479.6
    84.7    83.8    82.7    81.8    82.4    81.1    82.1    82.5   82.26   82.47
   82.02   82.02   81.97   82.04   82.35   82.23   82.68   82.61   82.56   82.61
   82.61   82.22   82.22   82.18    81.3    81.3    81.3   82.04   81.89   81.96
   81.91   80.96    81.5    81.3    79.5    79.7    81.3    81.2    81.5    82.4
      83
    84.6    83.7    82.6    81.7    82.3      81      82    82.4   82.15   82.36
   81.73   81.79   81.76   81.93   82.24   82.12   82.57    82.5   82.11   80.12
   81.01   80.62   80.23   81.79   81.12   80.79    81.1   81.93   81.78   81.85
    81.8   80.86    81.4    81.2    79.4    79.6    81.2    81.1    81.4    82.3
    82.9
Abutment Skew #Up #Dn= , 2 , 2
  4984.7  4993.5
   81.11   73.13
  4984.7  4993.5
   81.01   73.03
BR Coef= 1 , 1 , 0 ,1.25, 0 ,,,.8,0,2,0,
WSPro=,,,, 1 ,,,, 0 ,,,, 0 ,,,,-1 ,-1 ,-1 , 0 , 0 , 0 , 0 , 0
BR U #Sta/Elev= 62
  3284.1    84.7  3394.1    83.8  3564.1    82.7  3594.1    81.8  3774.1    82.4
  4024.1    81.1  4354.1    82.1  4544.1    82.5    4805   82.27  4812.9   82.27
  4830.7   82.25  4839.2   82.46  4869.7   81.83  4871.1   81.89  4907.4   81.86
  4918.2   82.03  4918.9   82.34  4957.9   82.22  4960.2   82.67  4962.9   82.66
  4976.9    82.6  4982.4   82.21 4983.99    80.9  4984.1   80.81 4984.21   80.72
 4984.81   80.22  4984.9   80.15    4985   80.06  4993.4   73.13  4993.5   73.13
  4993.8   73.14  4996.5    72.5  4999.3   72.81  5003.4   72.59  5006.1   73.23
  5014.1   80.16 5014.19   80.24  5014.3   80.33 5014.39   80.41  5014.5    80.5
  5014.6   80.59 5014.71   80.69  5016.1   81.89  5059.5   81.22  5062.3   81.18
  5100.5   80.89  5102.9    81.2  5109.2   82.03  5121.1   81.88  5147.9   81.95
  5187.7    81.9  5189.2   81.88  5253.4   80.96  5279.6    81.5  5549.6    81.3
  5649.6    79.5  5679.6    79.7  5729.6    81.3  5879.6    81.2  6279.6    81.5
  6459.6    82.4  6479.6      83
BR U #Mann= 4
  3284.1      .2    4805     .15  4982.4     .04  5016.1      .2
BR U Banks=4982.4,5016.1
BR D #Sta/Elev= 62
  3284.1    84.6  3394.1    83.7  3564.1    82.6  3594.1    81.7  3774.1    82.3
  4024.1      81  4354.1      82  4544.1    82.4    4805   82.17  4812.9   82.17
  4830.7   82.15  4839.2   82.36  4869.7   81.73  4871.1   81.79  4907.4   81.76
  4918.2   81.93  4918.9   82.24  4957.9   82.12  4960.2   82.57  4962.9   82.56
  4976.9    82.5  4982.4   82.11 4983.99    80.8  4984.1   80.71 4984.21   80.62
 4984.81   80.12  4984.9   80.05    4985   79.96  4993.4   73.03  4993.5   73.03
  4993.8   73.04  4996.5    72.4  4999.3   72.71  5003.4   72.49  5006.1   73.13
  5014.1   80.06 5014.19   80.14  5014.3   80.23 5014.39   80.31  5014.5    80.4
  5014.6   80.49 5014.71   80.59  5016.1   81.79  5059.5   81.12  5062.3   81.08
  5100.5   80.79  5102.9    81.1  5109.2   81.93  5121.1   81.78  5147.9   81.85
  5187.7    81.8  5189.2   81.78  5253.4   80.86  5279.6    81.4  5549.6    81.2
  5649.6    79.4  5679.6    79.6  5729.6    81.2  5879.6    81.1  6279.6    81.4
  6459.6    82.3  6479.6    82.9
BR D #Mann= 4
  3284.1      .2    4805     .15  4982.4     .04  5016.1      .2
BR D Banks=4982.4,5016.1
BC Design=,, 0 ,, 0 ,,,,,,

Type RM Length L Ch R = 1 ,22968.5 ,342.4,342.4,342.4
BEGIN DESCRIPTION:
Downstream Section of Bridge/Culvert/Weir
END DESCRIPTION:
XS GIS Cut Line= 5
      3105463.51     13899333.95      3106274.46     13898022.02
      3106289.66     13897700.21      3106292.58      13897568.1
      3105785.39     13896481.82
#Sta/Elev= 30
  3284.1   84.59  3564.1   82.59  3594.1   81.69  3774.1   82.29  4024.1   80.99
  4544.1   82.39    4805   82.16  4839.2   82.35  4907.4   81.75  4918.9   82.23
  4957.9   82.11  4960.2   82.56  4982.4    82.1  4993.4   73.02  4996.5   72.39
  5003.4   72.48  5006.1   73.12  5016.1   81.78  5100.5   80.78  5109.2   81.92
  5187.7   81.79  5253.4   80.85  5279.6   81.39  5549.6   81.19  5649.6   79.39
  5679.6   79.59  5729.6   81.19  6279.6   81.39  6459.6   82.29  6479.6   82.89
#Mann= 4 , 1 , 0
  3284.1      .2       0    4805     .15       0  4982.4     .04       0
  5016.1      .2       0
#XS Ineff= 2 , 0
       0    4542    82.5    5700       0    82.5
Permanent Ineff=
       F       F
Bank Sta=4982.4,5016.1
XS Rating Curve= 0
Exp/Cntr=.5,.3

Type RM Length L Ch R = 1 ,22626.1 ,309.3,279.6,269.3
BEGIN DESCRIPTION:
Cross Section 22626.1-Interpolated
END DESCRIPTION:
XS GIS Cut Line= 6
       3106257.6     13899029.87      3106425.48      13898568.2
      3106579.36     13898204.46      3106614.34     13897938.66
      3106698.28     13896966.36      3106901.13     13896672.57
#Sta/Elev= 29
  3785.4   82.99  4015.4   81.08  4276.6   82.88  4671.6   82.55  4711.6   82.68
  4901.6   80.12  4939.7    80.4  4982.4    81.4  4993.5   72.64  4993.8   72.65
  4996.5   72.01  4998.5   72.06  4999.3   72.32  5003.4    72.1  5006.1   72.74
  5016.1    81.4  5119.7   80.88  5129.7   80.58  5142.7   80.91  5302.7   81.65
  5522.7   81.32  5542.7   81.84  5642.7   80.56  5702.7   81.02  5722.7   80.67
  5892.7   80.94  5915.9   80.56  6175.9   82.32    6273   82.74
#Mann= 3 , 1 , 0
  3785.4     .12       0  4982.4     .04       0  5016.1      .2       0
#XS Ineff= 2 , 0
       0    4712    82.8    5543       0    82.3
Permanent Ineff=
       F       F
Bank Sta=4982.4,5016.1
XS Rating Curve= 0
Exp/Cntr=.3,.1

Type RM Length L Ch R = 1 ,22346.5 ,65.7,74.9,75.5
BEGIN DESCRIPTION:
Cross Section 22346.5-Interpolated
END DESCRIPTION:
XS GIS Cut Line= 5
      3106572.94     13899057.39       3106853.9     13898374.14
      3106892.21     13897965.48       3106898.6      13897780.3
      3106956.07     13896777.78
#Sta/Elev= 30
  3795.9    83.2  3915.9    83.1  4155.9    80.7  4175.9    81.6  4195.9    81.5
  4205.9    80.8  4534.7    81.5  4614.7    80.7  4624.7    80.8  4634.7    81.6
  4654.7    81.8  4684.7    80.9  4945.1    81.4  4970.7   80.64  4990.1   72.26
  5000.7   71.69  5007.8   71.92    5010    72.6  5010.4   81.01  5045.1    81.7
  5105.1    80.9  5130.4    81.5  5230.4    81.8  5300.4      81  5360.4    80.7
  5480.4    81.4  5620.4    81.7  5660.4    80.4  5710.4    81.2  6134.6    83.2
#Mann= 3 , 1 , 0
  3795.9     .12       0  4970.7     .04       0  5010.4      .2       0
#XS Ineff= 2 , 0
       0  4654.7    82.3    5620       0    81.5
Permanent Ineff=
       F       F
Bank Sta=4970.7,5010.4
XS Rating Curve= 0
Exp/Cntr=.5,.3

Type RM Length L Ch R = 1 ,22271.6 ,520,520,520
BEGIN DESCRIPTION:
Upstream Section of Bridge/Culvert/Weir
END DESCRIPTION:
XS GIS Cut Line= 6
      3106635.83     13899072.79      3106981.72     13898187.29
      3106925.34     13897729.21      3106930.04     13897475.51
      3106974.67     13896993.94      3106961.04     13896771.03
#Sta/Elev= 30
  3779.9   82.81  3999.9   81.31  4199.9   80.51  4492.8   81.31  4612.8   81.01
  4642.8   81.51  4763.4   81.29  4874.7   81.44  4920.1   81.32  4957.8   81.16
  4970.7   80.56  4990.1   72.18  5000.7   71.61  5007.8   71.84    5010   72.52
  5010.4   80.93  5018.8   81.81  5043.5   81.77  5044.7   82.49    5063   82.45
  5100.4   81.72  5194.5   82.51  5382.1   81.42  5494.5   80.91  5634.5   80.61
  5714.5   81.31  5824.5   81.31  5994.5   82.11  6084.5   82.71  6152.8   82.61
#Mann= 3 , 1 , 0
  3779.9     .12       0  4970.7     .04       0  5010.4      .2       0
#XS Ineff= 2 , 0
       0    4730    82.1    5188       0    82.5
Permanent Ineff=
       F       F
Bank Sta=4970.7,5010.4
XS Rating Curve= 0
Exp/Cntr=.5,.3