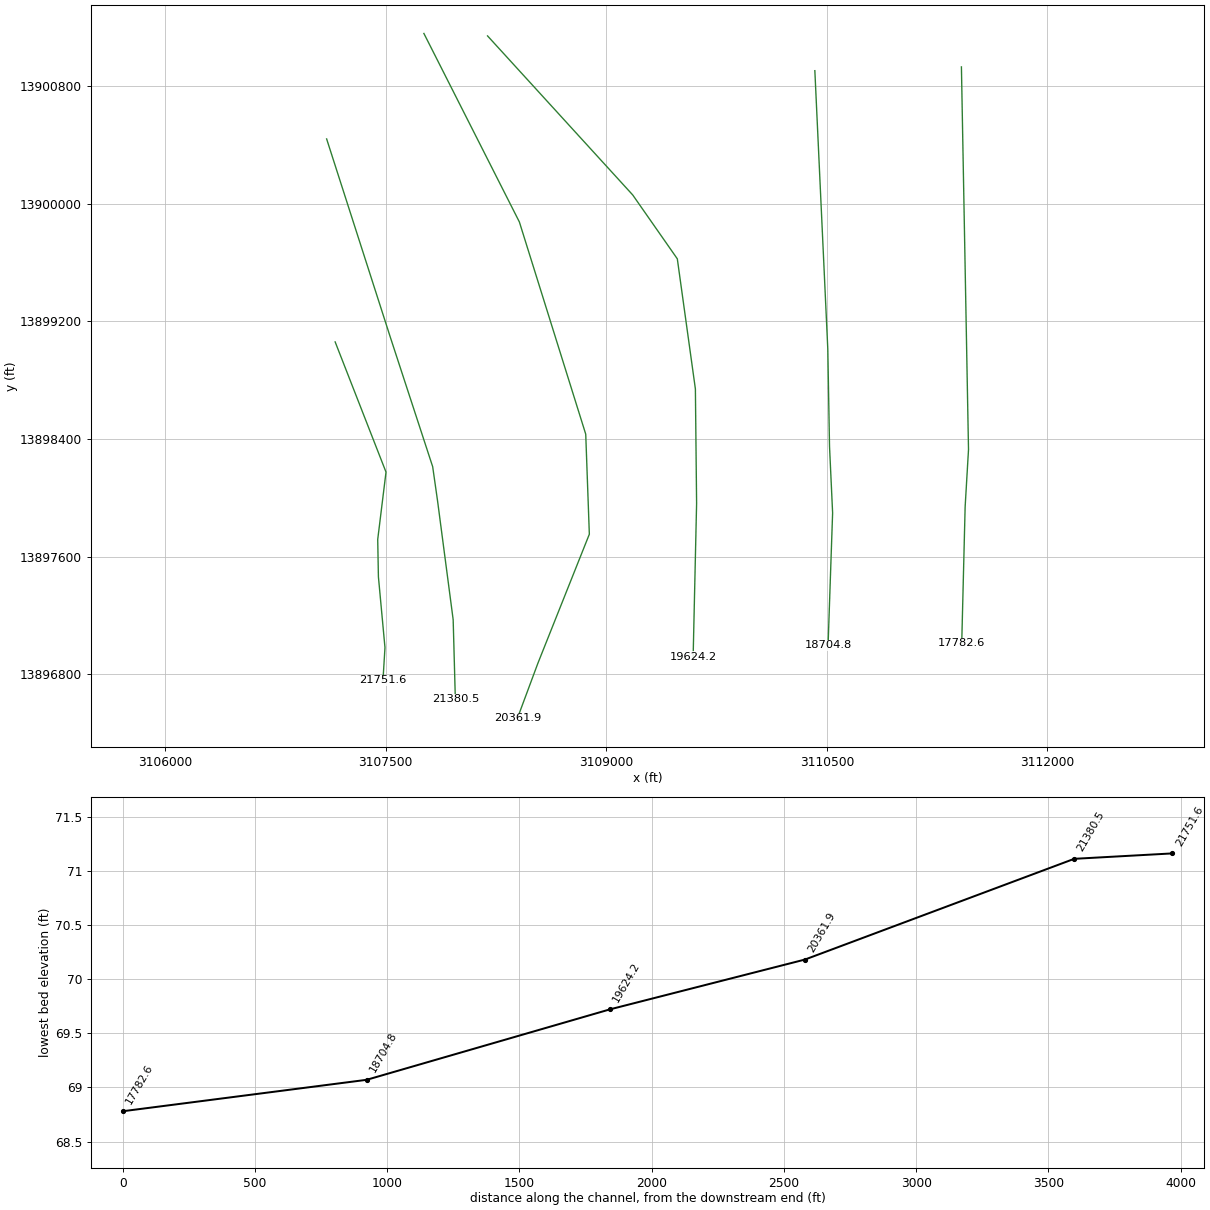
HEC-RAS study P138-00-00.prj: P138-00-00

--- P138-00-00.g01 (geometry) --- (continued)

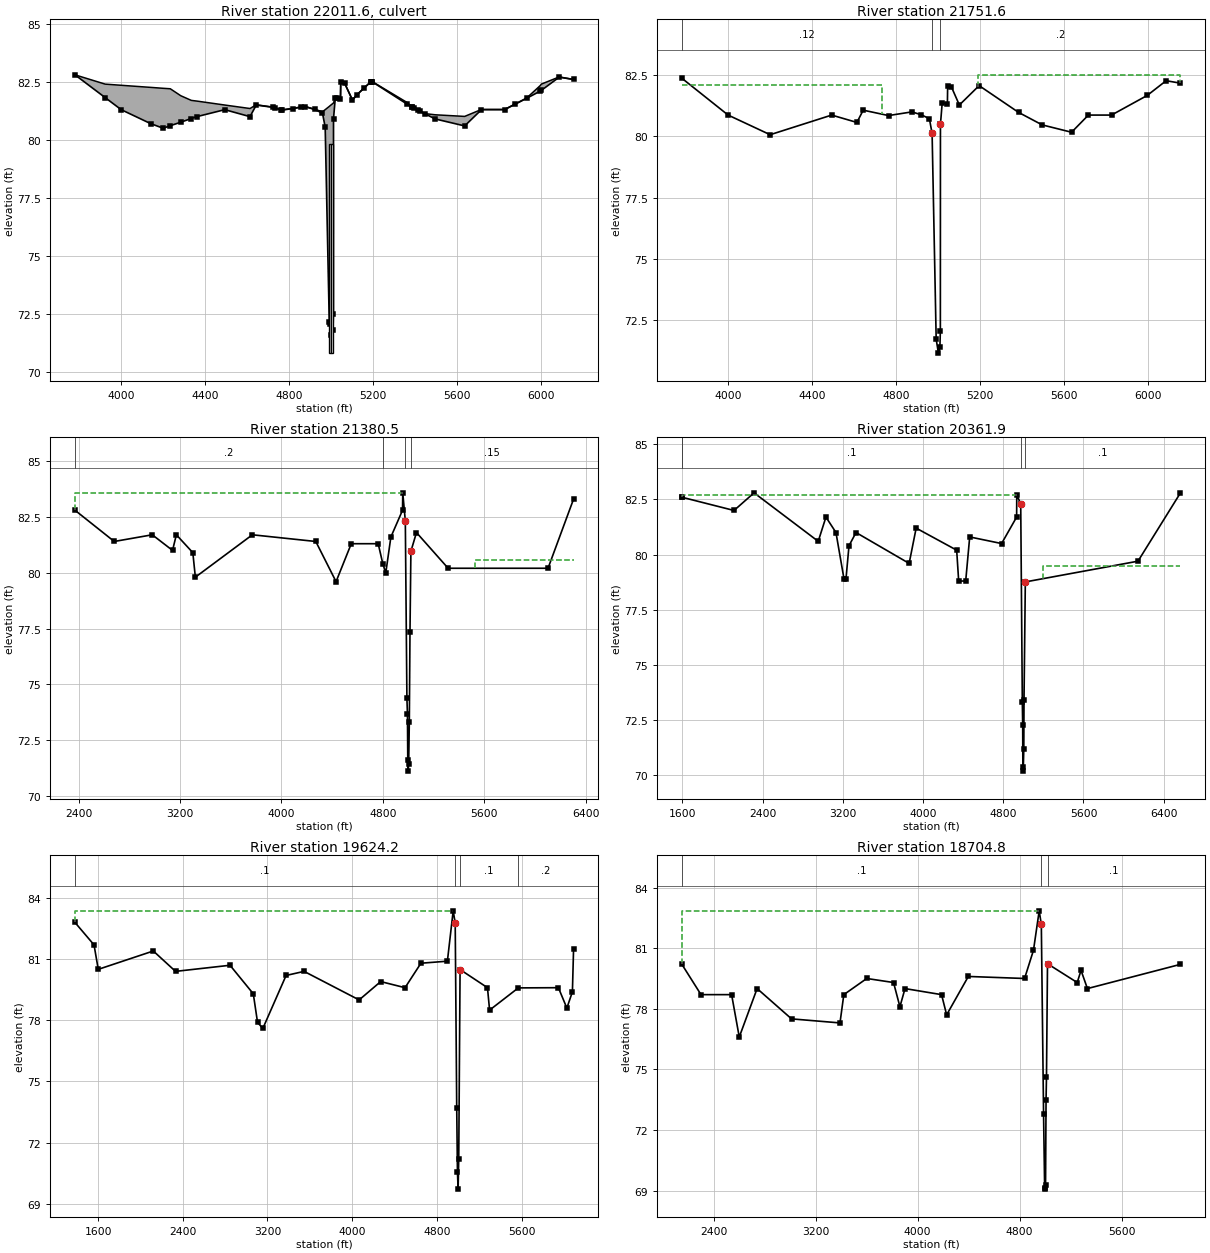
Type RM Length L Ch R = 2 ,22011.6 ,,,
BEGIN DESCRIPTION:
AIRLINE ROAD
Structure ID: P38-17
END DESCRIPTION:
Bridge Culvert--1,0,-1,-1, 0
Deck Dist Width WeirC Skew NumUp NumDn MinLoCord MaxHiCord MaxSubmerge Is_Ogee
10,500,3,0, 57, 57, , , .95, 0, 1,1,,
  3779.9  3923.5  3999.9  4139.9  4199.9  4233.5  4283.5  4333.5  4359.9  4492.8
  4612.8  4642.8  4722.8  4730.5  4758.8  4763.4  4818.8  4857.8  4874.7  4920.1
  4957.8  4970.7  4990.1  4992.7  5000.7  5007.8    5010  5010.4  5018.8  5026.1
  5043.5  5044.7    5063  5100.4  5123.2  5156.1    5187  5190.5  5192.1  5194.5
  5362.1  5382.1  5384.5  5392.1  5412.1  5422.1  5445.8  5494.5  5634.5  5714.5
  5824.5  5875.8  5929.4  5994.5  5999.4  6084.5  6152.8
    82.8    82.4   82.35   82.26   82.22    82.2    81.9    81.7   81.67    81.5
   81.35   81.51   81.41   81.39    81.3   81.29   81.36   81.42   81.44   81.32
   81.21    81.3   81.44   81.46   81.52   81.57   81.59   81.59   81.81    81.8
   81.77   82.49   82.45   81.72   81.96   82.24    82.5    82.5   82.51   82.51
    81.6   81.42   81.41   81.38   81.28   81.24   81.13   81.08   81.01   81.31
   81.31   81.55    81.8   82.34    82.4   82.71    82.6
    82.8   81.82    81.3    80.7    80.5   80.61   80.76   80.92      81    81.3
      81    81.5    81.4   81.38   81.29   81.28   81.35   81.41   81.43   81.31
   81.15   80.55   72.17   72.07    71.6   71.83   72.51   80.92    81.8   81.79
   81.76   82.48   82.44   81.71   81.95   82.23   82.49   82.49    82.5    82.5
   81.53   81.41    81.4   81.37   81.27   81.23   81.12    80.9    80.6    81.3
    81.3   81.54   81.79    82.1   82.13    82.7    82.6
  3779.9  3923.5  3999.9  4139.9  4199.9  4233.5  4283.5  4333.5  4359.9  4492.8
  4612.8  4642.8  4722.8  4730.5  4758.8  4763.4  4818.8  4857.8  4874.7  4920.1
  4957.8  4970.7  4990.1  4992.7  5000.7  5007.8    5010  5010.4  5018.8  5026.1
  5043.5  5044.7    5063  5100.4  5123.2  5156.1    5187  5190.5  5192.1  5194.5
  5362.1  5382.1  5384.5  5392.1  5412.1  5422.1  5445.8  5494.5  5634.5  5714.5
  5824.5  5875.8  5929.4  5994.5  5999.4  6084.5  6152.8
    82.8    82.4   82.35   82.26   82.22    82.2    81.9    81.7   81.67    81.5
   81.35   81.51   81.41   81.39    81.3   81.29   81.36   81.42   81.44   81.32
   81.21    81.3   81.44   81.46   81.52   81.57   81.59   81.59   81.81    81.8
   81.77   82.49   82.45   81.72   81.96   82.24    82.5    82.5   82.51   82.51
    81.6   81.42   81.41   81.38   81.28   81.24   81.13   81.08   81.01   81.31
   81.31   81.55    81.8   82.34    82.4   82.71    82.6
   82.36   81.38   80.86   80.26   80.06   80.17   80.32   80.48   80.56   80.86
   80.56   81.06   80.96   80.94   80.85   80.84   80.91   80.97   80.99   80.87
   80.71   80.11   71.73   71.63   71.16   71.39   72.07   80.48   81.36   81.35
   81.32   82.04      82   81.27   81.51   81.79   82.05   82.05   82.06   82.06
   81.09   80.97   80.96   80.93   80.83   80.79   80.68   80.46   80.16   80.86
   80.86    81.1   81.35   81.66   81.69   82.26   82.16
BR Coef= 1 , 0 , 0 ,1.25, 0 ,,,.8,-1,2,0,
WSPro=,,,, 1 ,,,, 0 ,,,, 0 ,,,,-1 ,-1 ,-1 , 0 , 0 , 0 , 0 , 0
Culvert=2,9,10,500,.015,.4,1,8,1,70.82,4994.2,68.72,4994.2,Culvert #1  , 0 ,10
Culvert Bottom n=.015
Culvert=2,9,10,500,.015,.4,1,8,1,70.82,5004.7,68.72,5004.7,Culvert #2  , 0 ,10
Culvert Bottom n=.015
BR U #Sta/Elev= 57
  3779.9    82.8  3923.5   81.82  3999.9    81.3  4139.9    80.7  4199.9    80.5
  4233.5   80.61  4283.5   80.76  4333.5   80.92  4359.9      81  4492.8    81.3
  4612.8      81  4642.8    81.5  4722.8    81.4  4730.5   81.38  4758.8   81.29
  4763.4   81.28  4818.8   81.35  4857.8   81.41  4874.7   81.43  4920.1   81.31
  4957.8   81.15  4970.7   80.55  4990.1   72.17  4992.7   72.07  5000.7    71.6
  5007.8   71.83    5010   72.51  5010.4   80.92  5018.8    81.8  5026.1   81.79
  5043.5   81.76  5044.7   82.48    5063   82.44  5100.4   81.71  5123.2   81.95
  5156.1   82.23    5187   82.49  5190.5   82.49  5192.1    82.5  5194.5    82.5
  5362.1   81.53  5382.1   81.41  5384.5    81.4  5392.1   81.37  5412.1   81.27
  5422.1   81.23  5445.8   81.12  5494.5    80.9  5634.5    80.6  5714.5    81.3
  5824.5    81.3  5875.8   81.54  5929.4   81.79  5994.5    82.1  5999.4   82.13
  6084.5    82.7  6152.8    82.6
BR U #Mann= 3
  3779.9     .12  4970.7     .04  5010.4      .2
BR U Banks=4970.7,5010.4
BR D #Sta/Elev= 57
  3779.9   82.36  3923.5   81.38  3999.9   80.86  4139.9   80.26  4199.9   80.06
  4233.5   80.17  4283.5   80.32  4333.5   80.48  4359.9   80.56  4492.8   80.86
  4612.8   80.56  4642.8   81.06  4722.8   80.96  4730.5   80.94  4758.8   80.85
  4763.4   80.84  4818.8   80.91  4857.8   80.97  4874.7   80.99  4920.1   80.87
  4957.8   80.71  4970.7   80.11  4990.1   71.73  4992.7   71.63  5000.7   71.16
  5007.8   71.39    5010   72.07  5010.4   80.48  5018.8   81.36  5026.1   81.35
  5043.5   81.32  5044.7   82.04    5063      82  5100.4   81.27  5123.2   81.51
  5156.1   81.79    5187   82.05  5190.5   82.05  5192.1   82.06  5194.5   82.06
  5362.1   81.09  5382.1   80.97  5384.5   80.96  5392.1   80.93  5412.1   80.83
  5422.1   80.79  5445.8   80.68  5494.5   80.46  5634.5   80.16  5714.5   80.86
  5824.5   80.86  5875.8    81.1  5929.4   81.35  5994.5   81.66  5999.4   81.69
  6084.5   82.26  6152.8   82.16
BR D #Mann= 3
  3779.9     .12  4970.7     .04  5010.4      .2
BR D Banks=4970.7,5010.4
BC Design=,, 0 ,, 0 ,,,,,,

Type RM Length L Ch R = 1 ,21751.6 ,371.1,371.1,371.1
BEGIN DESCRIPTION:
Downstream Section of Bridge/Culvert/Weir
END DESCRIPTION:
XS GIS Cut Line= 6
       3107155.7     13899061.26       3107501.6     13898175.77
      3107445.22     13897717.69      3107449.92     13897463.99
      3107494.55     13896982.42      3107480.91      13896759.5
#Sta/Elev= 30
  3779.9   82.36  3999.9   80.86  4199.9   80.06  4492.8   80.86  4612.8   80.56
  4642.8   81.06  4763.4   80.84  4874.7   80.99  4920.1   80.87  4957.8   80.71
  4970.7   80.11  4990.1   71.73  5000.7   71.16  5007.8   71.39    5010   72.07
  5010.4   80.48  5018.8   81.36  5043.5   81.32  5044.7   82.04    5063      82
  5100.4   81.27  5194.5   82.06  5382.1   80.97  5494.5   80.46  5634.5   80.16
  5714.5   80.86  5824.5   80.86  5994.5   81.66  6084.5   82.26  6152.8   82.16
#Mann= 3 , 1 , 0
  3779.9     .12       0  4970.7     .04       0  5010.4      .2       0
#XS Ineff= 2 , 0
       0    4730    82.1    5188       0    82.5
Permanent Ineff=
       F       F
Bank Sta=4970.7,5010.4
XS Rating Curve= 0
Exp/Cntr=.5,.3

Type RM Length L Ch R = 1 ,21380.5 ,1076.9,1018.6,910.6
BEGIN DESCRIPTION:
Cross Section 21380.5
END DESCRIPTION:
XS GIS Cut Line= 6
       3107097.8     13900441.67      3107532.18     13899089.35
      3107819.04      13898212.4      3107851.82     13897982.91
      3107958.37     13897171.52       3107973.2     13896630.26
#Sta/Elev= 30
  2370.2    82.8  2680.2    81.4  2980.2    81.7  3140.2      81  3170.2    81.7
  3300.2    80.9  3320.2    79.8  3770.2    81.7  4270.6    81.4  4430.6    79.6
  4550.6    81.3  4763.2    81.3    4800   80.39  4823.2      80  4863.2    81.6
  4955.1    82.8    4957   83.58  4977.2   82.32  4989.7   74.37    4994   73.66
  4996.5   71.62  4999.8   71.11  5003.6   71.43  5008.8   73.33    5014   77.34
  5021.2   80.96  5065.1    81.8  5315.1    80.2  6103.4    80.2  6304.9    83.3
#Mann= 4 , 1 , 0
  2370.2      .2       0    4800      .1       0  4977.2     .04       0
  5021.2     .15       0
#XS Ineff= 2 , 0
       0    4957   83.58    5528       0   80.58
Permanent Ineff=
       F       F
Bank Sta=4977.2,5021.2
XS Rating Curve= 0
Exp/Cntr=.3,.1

Type RM Length L Ch R = 1 ,20361.9 ,820.9,737.7,734.6
BEGIN DESCRIPTION:
Cross Section 20361.9
END DESCRIPTION:
XS GIS Cut Line= 6
       3107759.3     13901158.97      3108408.59     13899877.05
      3108859.91     13898433.68       3108884.5     13897753.43
      3108534.85     13896876.48      3108395.42     13896501.61
#Sta/Elev= 30
    1594    82.6  1594.1    82.6  2114.1      82  2314.1    82.8  2954.1    80.6
  3031.1    81.7  3131.1      81  3211.1    78.9  3231.1    78.9  3261.1    80.4
  3331.1      81  3861.1    79.6  3931.1    81.2  4335.3    80.2  4355.3    78.8
  4425.3    78.8  4465.3    80.8  4783.4    80.5  4933.4    81.7  4934.8   82.72
  4974.2   82.29  4990.2   73.33  4993.9   72.27  4995.7   70.37    4999   70.18
    5005   71.19  5007.1   73.41  5020.2   78.76  6144.1    79.7  6568.1    82.8
#Mann= 4 , 1 , 0
    1594      .2       0  1594.1      .1       0  4974.2     .04       0
  5020.2      .1       0
#XS Ineff= 2 , 0
       0  4934.8   82.72    5200       0    79.5
Permanent Ineff=
       F       F
Bank Sta=4974.2,5020.2
XS Rating Curve= 0
Exp/Cntr=.3,.1

Type RM Length L Ch R = 1 ,19624.2 ,917.2,919.4,933.5
BEGIN DESCRIPTION:
Cross Section 19624.2
END DESCRIPTION:
XS GIS Cut Line= 6
      3108192.16     13901142.32      3109179.55     13900060.56
       3109482.8     13899626.18      3109605.74     13898741.03
      3109613.93     13897962.42      3109590.37      13896919.4
#Sta/Elev= 30
  1381.4    82.8  1561.4    81.7  1601.4    80.5  2121.4    81.4  2331.4    80.4
    2846    80.7    3066    79.3    3106    77.9    3156    77.6  3375.8    80.2
  3545.8    80.4  4065.8      79  4269.4    79.9  4499.4    79.6  4649.4    80.8
  4899.4    80.9  4954.2   83.37  4973.3   82.77  4987.6   73.72  4994.4   70.57
  5000.8   69.72  5006.7   71.22  5019.3   80.49  5278.1    79.6  5298.1    78.5
  5569.4   79.59  5948.1    79.6  6028.1    78.6  6080.5    79.4  6091.4    81.5
#Mann= 4 , 1 , 0
  1381.4      .1       0  4973.3     .04       0  5019.3      .1       0
  5569.4      .2       0
#XS Ineff= 2 , 0
       0  4954.2   83.37    5158       0      80
Permanent Ineff=
       F       F
Bank Sta=4973.3,5019.3
XS Rating Curve= 0
Exp/Cntr=.3,.1

Type RM Length L Ch R = 1 ,18704.8 ,956.3,922.2,902.6
BEGIN DESCRIPTION:
Cross Section 18704.8
END DESCRIPTION:
XS GIS Cut Line= 5
      3110418.16     13900905.87      3110506.28     13899011.34
      3110517.94     13898350.37      3110538.98     13897897.91
      3110508.05     13896998.44
#Sta/Elev= 30
  2151.7    80.2  2301.7    78.7  2541.7    78.7  2601.7    76.6  2741.7      79
  3011.7    77.5  3391.7    77.3  3421.7    78.7  3601.7    79.5  3811.7    79.3
  3861.7    78.1  3901.7      79  4188.3    78.7  4228.3    77.7  4398.3    79.6
  4839.4    79.5  4909.4    80.9  4954.1   82.85  4970.8   82.18  4988.4   72.78
  4996.9   69.11  5000.1   69.07    5004   69.25  5007.9   73.49  5011.3   74.63
  5019.3   80.23  5252.3    79.3  5282.3    79.9  5332.3      79  6062.3    80.2
#Mann= 3 , 1 , 0
  2151.7      .1       0  4970.8     .04       0  5019.3      .1       0
#XS Ineff= 2 , 0
       0  4954.1   82.85               0
Permanent Ineff=
       F       F
Bank Sta=4970.8,5019.3
XS Rating Curve= 0
Exp/Cntr=.3,.1

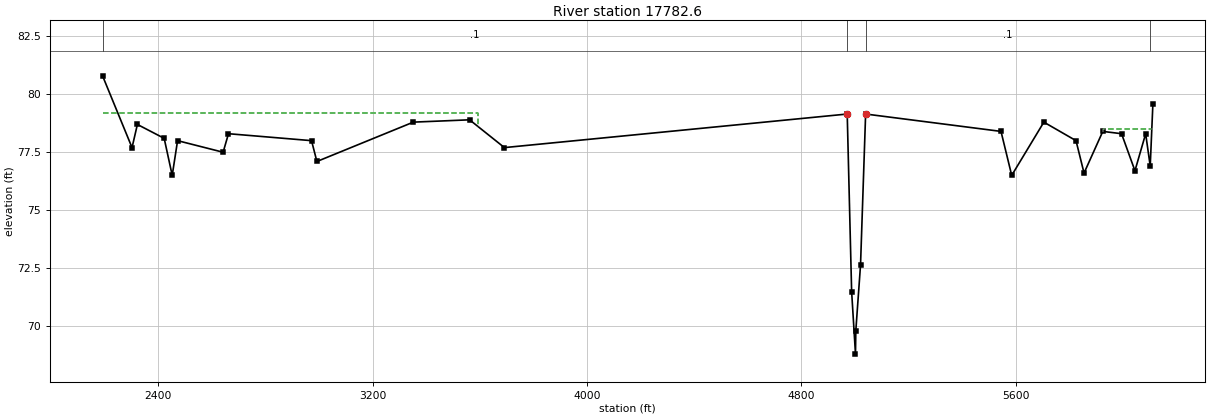
Type RM Length L Ch R = 1 ,17782.6 ,194.8,152,148.6
BEGIN DESCRIPTION:
Cross Section 17782.6-Interpolated
END DESCRIPTION:
XS GIS Cut Line= 4
      3111414.97     13900931.51      3111463.17     13898328.78
      3111440.25     13897939.19      3111417.08     13897012.42
#Sta/Elev= 30
    2192    80.8    2302    77.7    2322    78.7    2422    78.1    2452    76.5
    2472      78    2642    77.5    2662    78.3    2972      78    2992    77.1
    3352    78.8    3562    78.9    3692    77.7  4971.5   79.15    4988   71.48
  5002.4   68.78  5003.6   69.79  5021.2   72.63  5040.2   79.15  5545.5    78.4
  5585.5    76.5  5705.5    78.8  5825.5      78  5855.5    76.6  5925.5    78.4
  5995.5    78.3  6045.5    76.7  6085.5    78.3  6102.5    76.9  6112.5    79.6
#Mann= 4 , 1 , 0
    2192      .1       0  4971.5     .04       0  5040.2      .1       0
  6102.5      .2       0
#XS Ineff= 2 , 0
       0    3594    79.2    5925       0    78.5
Permanent Ineff=
       F       F
Bank Sta=4971.5,5040.2
XS Rating Curve= 0
Exp/Cntr=.5,.3