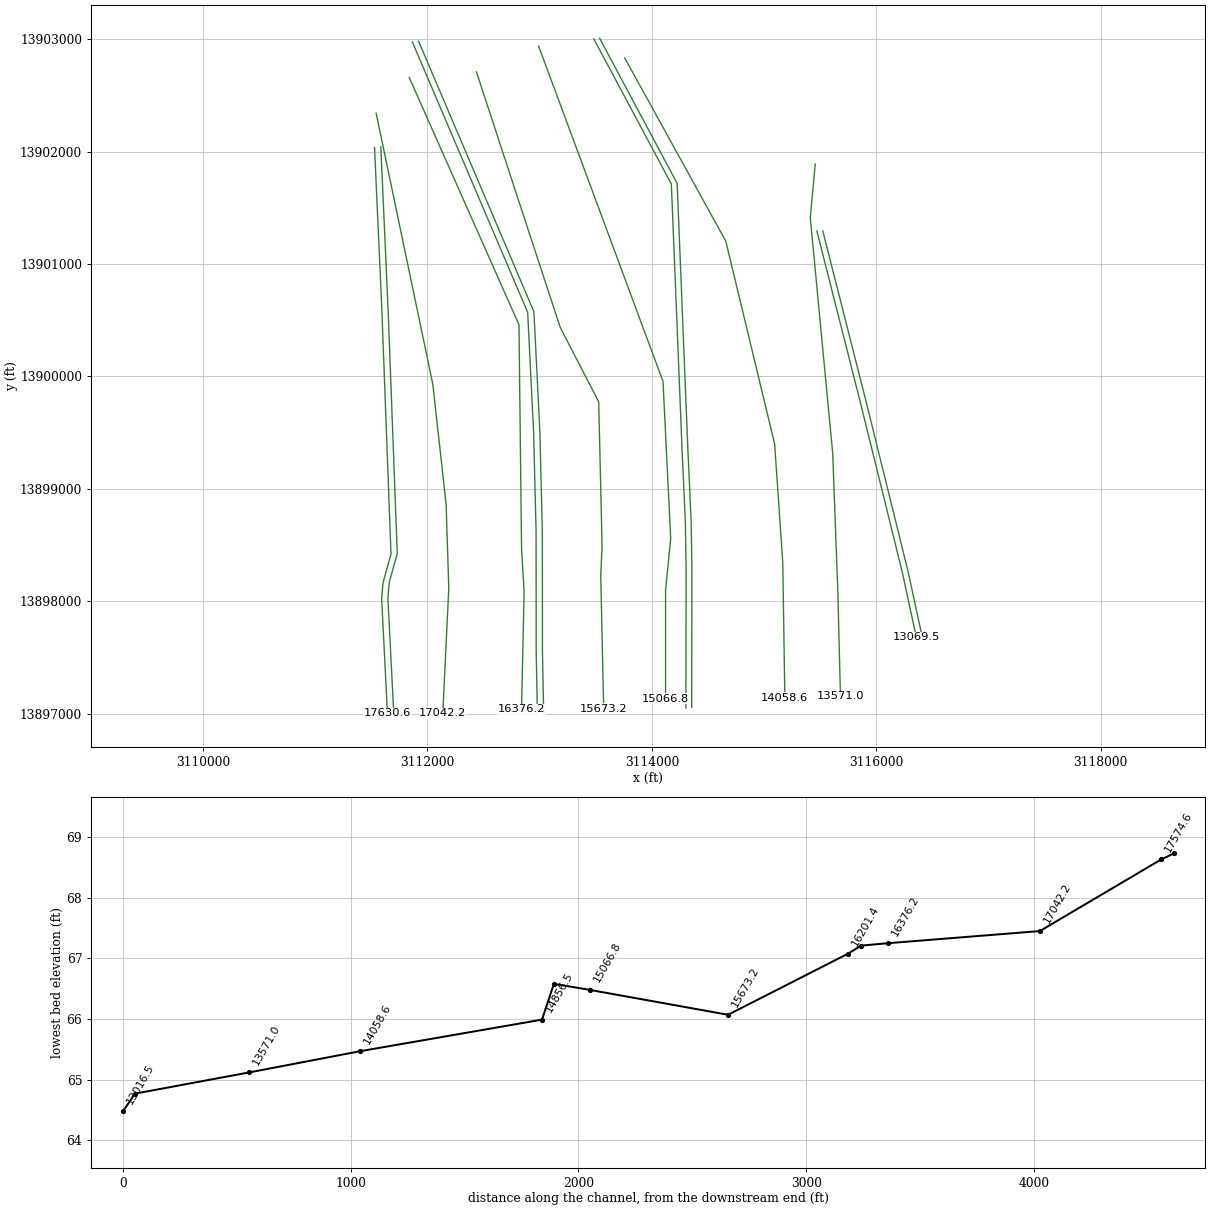
HEC-RAS study P138-00-00.prj: P138-00-00

--- P138-00-00.g01 (geometry) --- (continued)

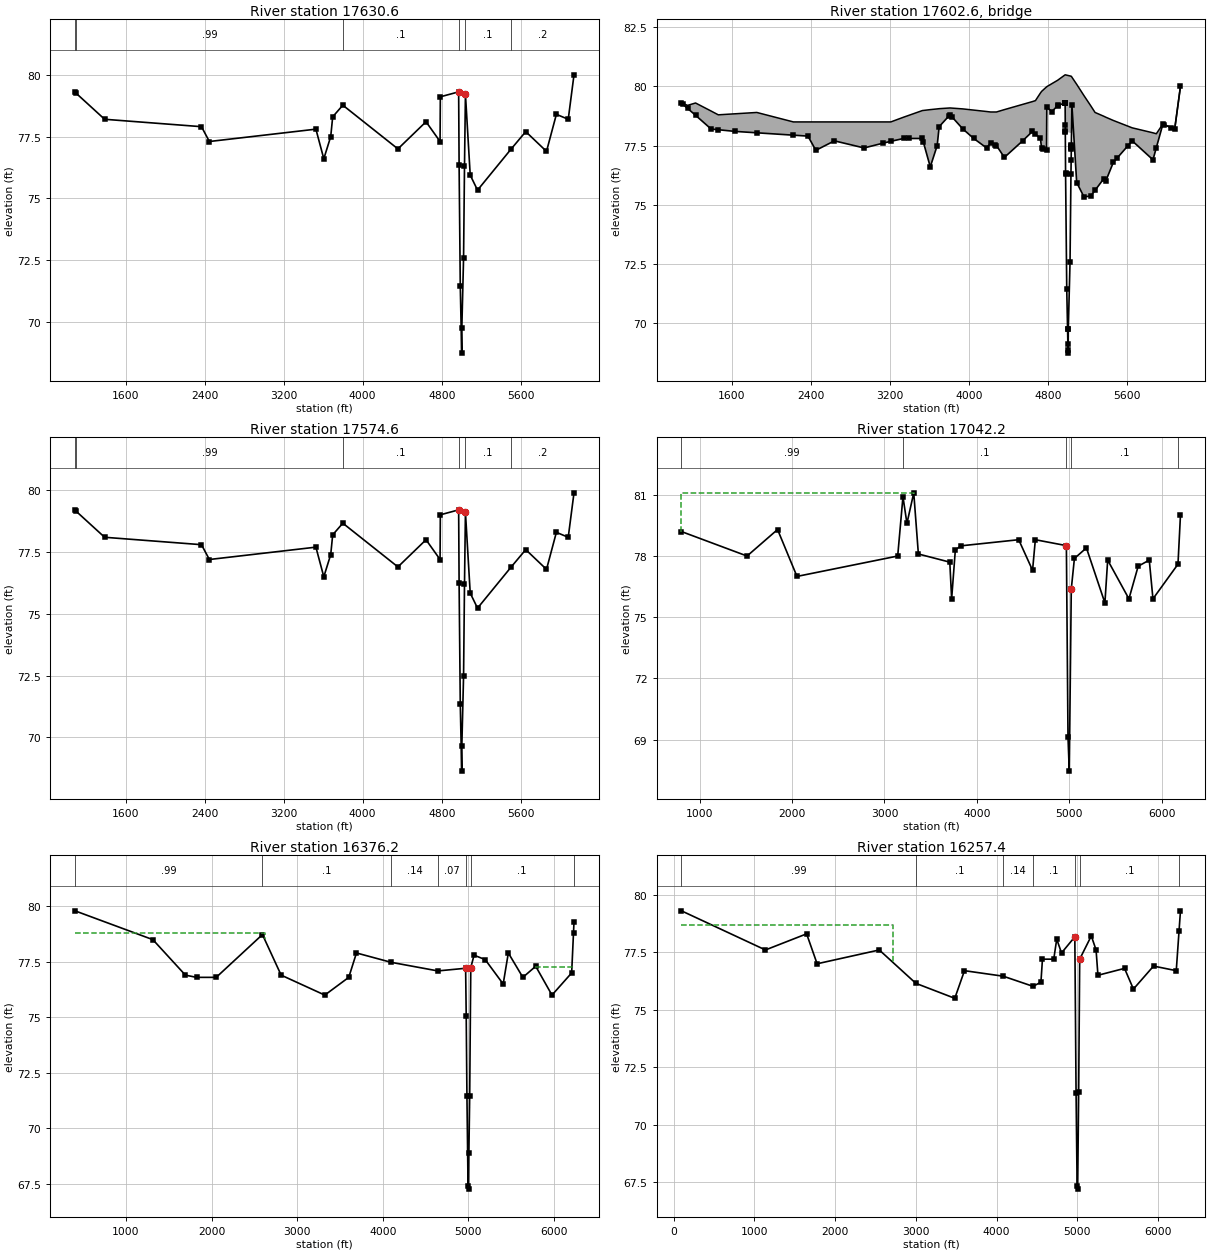
Type RM Length L Ch R = 1 ,17630.6 ,56,56,56
BEGIN DESCRIPTION:
Upstream Section of Bridge/Culvert/Weir
END DESCRIPTION:
XS GIS Cut Line= 6
      3111528.22     13902037.15      3111593.33     13900590.23
      3111674.83     13898420.11      3111604.05      13898165.6
      3111591.36     13898023.47      3111643.37     13897001.89
#Sta/Elev= 30
  1088.8    79.3  1101.4   79.25  1388.8    78.2  2368.8    77.9  2448.8    77.3
  3526.8    77.8  3606.8    76.6  3676.8    77.5  3696.8    78.3  3799.4   78.77
  4356.8      77  4641.3    78.1  4783.4    77.3  4786.2   79.11  4971.5   79.31
    4976   76.36    4988   71.43  5002.4   68.73  5003.6   69.74  5021.2   72.58
  5030.6   76.29  5040.2   79.21  5088.5   75.94  5162.5   75.33  5499.4   76.98
  5650.5    77.7  5860.5    76.9  5960.5    78.4  6080.5    78.2  6138.8      80
#Mann= 6 , 1 , 0
  1088.8      .2       0  1101.4     .99       0  3799.4      .1       0
  4971.5     .04       0  5040.2      .1       0  5499.4      .2       0
#XS Ineff= 2 , 0
       0    4960    78.5    5050       0      78
Permanent Ineff=
       F       F
Bank Sta=4971.5,5040.2
XS Rating Curve= 0
Exp/Cntr=.5,.3

Type RM Length L Ch R = 3 ,17602.6 ,,,
BEGIN DESCRIPTION:
LILLJA ROAD
Structure ID: P38-15
END DESCRIPTION:
Bridge Culvert--1,0,-1,-1, 0
Deck Dist Width WeirC Skew NumUp NumDn MinLoCord MaxHiCord MaxSubmerge Is_Ogee
10,36,2.6,0, 49, 49, , , .95, 0, 1,1,,
  1088.8  1151.4  1231.4  1388.8  1461.4  1851.4  2221.4  2368.8  2448.8  2636.8
  2936.8  3207.2  3336.8  3526.8  3606.8  3676.8  3696.8  3806.8  3936.8  4176.8
  4216.8  4276.8  4356.8  4641.3  4671.1  4721.3  4733.4  4783.4  4786.2  4838.6
  4895.6  4971.5  4973.4 5034.09  5034.2  5040.2  5088.5  5162.5  5231.2  5274.5
  5362.7  5382.7  5460.5  5650.5  5860.5  5894.5  5960.5  6080.5  6138.8
    79.3    79.2    79.3   78.96    78.8    78.9    78.5    78.5    78.5    78.5
    78.5    78.5    78.7   78.98   79.02   79.05   79.06   79.09   79.05   78.94
   78.92   78.92   79.02   79.36    79.4   79.72   79.79   79.98   79.99   80.12
   80.26   80.49   80.49   80.43   80.43   80.39   80.09   79.61   79.18    78.9
   78.74    78.7   78.56   78.25   78.04      78   78.41    78.2      80
    79.3   79.07   78.78    78.2   78.17   78.04   77.94    77.9    77.3    77.7
    77.4   77.68    77.8    77.8    76.6    77.5    78.3    78.8    78.2    77.4
    77.6    77.5      77    78.1   77.99    77.8    77.4    77.3   79.11   78.94
   79.19   79.31   78.09   78.03   77.38   79.21   75.94   75.33   75.37   75.61
    76.1      76    76.8    77.7    76.9   77.41    78.4    78.2      80
  1088.8  1151.4  1231.4  1388.8  1461.4  1851.4  2221.4  2368.8  2448.8  2636.8
  2936.8  3207.2  3336.8  3526.8  3606.8  3676.8  3696.8  3806.8  3936.8  4176.8
  4216.8  4276.8  4356.8  4641.3  4671.1  4721.3  4733.4  4783.4  4786.2  4838.6
  4895.6  4971.5  4973.4 5034.09  5034.2  5040.2  5088.5  5162.5  5231.2  5274.5
  5362.7  5382.7  5460.5  5650.5  5860.5  5894.5  5960.5  6080.5  6138.8
    79.3    79.2    79.3   78.96    78.8    78.9    78.5    78.5    78.5    78.5
    78.5    78.5    78.7   78.98   79.02   79.05   79.06   79.09   79.05   78.94
   78.92   78.92   79.02   79.36    79.4   79.72   79.79   79.98   79.99   80.12
   80.26   80.49   80.49   80.43   80.43   80.39   80.09   79.61   79.18    78.9
   78.74    78.7   78.56   78.25   78.04      78   78.41    78.2      80
   79.22   78.99    78.7   78.12   78.09   77.96   77.86   77.82   77.22   77.62
   77.32    77.6   77.72   77.72   76.52   77.42   78.22   78.72   78.12   77.32
   77.52   77.42   76.92   78.02   77.91   77.72   77.32   77.22   79.03   78.86
   79.11   79.23   78.01   77.95    77.3   79.13   75.86   75.25   75.29   75.53
   76.02   75.92   76.72   77.62   76.82   77.33   78.32   78.12   79.92
Abutment Skew #Up #Dn= , 2 , 2
  4973.2  4976.1
   78.09   76.32
  4973.2  4976.1
   78.01   76.24
Abutment Skew #Up #Dn= , 2 , 2
  5032.6 5034.29
    76.9   78.03
  5032.6 5034.29
   76.82   77.95
BR Coef= 1 , 1 , 0 ,1.25, 0 ,,,.8,-1,2,0,
WSPro=,,,, 1 ,,,, 0 ,,,, 0 ,,,,-1 ,-1 ,-1 , 0 , 0 , 0 , 0 , 0
BR U #Sta/Elev= 84
  1088.8    79.3  1101.4   79.25  1151.4   79.07  1231.4   78.78  1388.8    78.2
  1461.4   78.17  1628.8    78.1  1851.4   78.04  2221.4   77.94  2368.8    77.9
  2448.8    77.3  2636.8    77.7  2936.8    77.4  3126.8    77.6  3207.2   77.68
  3336.8    77.8  3386.8    77.8  3526.8    77.8  3537.2   77.64  3606.8    76.6
  3676.8    77.5  3696.8    78.3  3799.4   78.77  3806.8    78.8  3827.2   78.71
  3936.8    78.2  4046.8    77.8  4176.8    77.4  4216.8    77.6  4257.2   77.53
  4276.8    77.5  4356.8      77  4541.6    77.7  4641.3    78.1  4671.1   77.99
  4721.3    77.8  4733.4    77.4  4750.2   77.37  4783.4    77.3  4786.2   79.11
  4838.6   78.94  4895.6   79.19  4904.3    79.2 4968.29    79.3  4968.4   79.31
 4968.51   79.31  4971.5   79.31  4972.9   78.39 4973.31   78.12  4973.4   78.06
    4976   76.36  4976.1   76.32    4988   71.43  4996.4   69.73  4999.4    69.1
  5001.4   68.86  5002.4   68.73  5003.6   69.74  5021.2   72.58  5030.6   76.29
  5032.6    76.9 5034.09   77.35  5034.2   77.38 5034.39   77.44  5034.5   77.48
 5034.61   77.51  5040.2   79.21  5088.5   75.94  5162.5   75.33  5231.2   75.37
  5274.5   75.61  5362.7    76.1  5382.7      76  5460.5    76.8  5499.4   76.98
  5604.5   77.48  5650.5    77.7  5860.5    76.9  5894.5   77.41  5960.5    78.4
  5974.5   78.38  6044.5   78.26  6080.5    78.2  6138.8      80
BR U #Mann= 6
  1088.8      .2  1101.4     .99  3799.4      .1  4971.5     .04  5040.2      .1
  5499.4      .2
BR U Banks=4971.5,5040.2
BR D #Sta/Elev= 84
  1088.8   79.22  1101.4   79.17  1151.4   78.99  1231.4    78.7  1388.8   78.12
  1461.4   78.09  1628.8   78.02  1851.4   77.96  2221.4   77.86  2368.8   77.82
  2448.8   77.22  2636.8   77.62  2936.8   77.32  3126.8   77.52  3207.2    77.6
  3336.8   77.72  3386.8   77.72  3526.8   77.72  3537.2   77.56  3606.8   76.52
  3676.8   77.42  3696.8   78.22  3799.4   78.69  3806.8   78.72  3827.2   78.63
  3936.8   78.12  4046.8   77.72  4176.8   77.32  4216.8   77.52  4257.2   77.45
  4276.8   77.42  4356.8   76.92  4541.6   77.62  4641.3   78.02  4671.1   77.91
  4721.3   77.72  4733.4   77.32  4750.2   77.29  4783.4   77.22  4786.2   79.03
  4838.6   78.86  4895.6   79.11  4904.3   79.12 4968.29   79.22  4968.4   79.23
 4968.51   79.23  4971.5   79.23  4972.9   78.31 4973.31   78.04  4973.4   77.98
    4976   76.28  4976.1   76.24    4988   71.35  4996.4   69.65  4999.4   69.02
  5001.4   68.78  5002.4   68.65  5003.6   69.66  5021.2    72.5  5030.6   76.21
  5032.6   76.82 5034.09   77.27  5034.2    77.3 5034.39   77.36  5034.5    77.4
 5034.61   77.43  5040.2   79.13  5088.5   75.86  5162.5   75.25  5231.2   75.29
  5274.5   75.53  5362.7   76.02  5382.7   75.92  5460.5   76.72  5499.4    76.9
  5604.5    77.4  5650.5   77.62  5860.5   76.82  5894.5   77.33  5960.5   78.32
  5974.5    78.3  6044.5   78.18  6080.5   78.12  6138.8   79.92
BR D #Mann= 6
  1088.8      .2  1101.4     .99  3799.4      .1  4971.5     .04  5040.2      .1
  5499.4      .2
BR D Banks=4971.5,5040.2
BC Design=,, 0 ,, 0 ,,,,,,

Type RM Length L Ch R = 1 ,17574.6 ,532.4,532.4,532.4
BEGIN DESCRIPTION:
Downstream Section of Bridge/Culvert/Weir
END DESCRIPTION:
XS GIS Cut Line= 6
      3111583.96     13902042.54      3111649.07     13900595.63
      3111730.57     13898425.51      3111659.79       13898171.
       3111647.1     13898028.87      3111699.11     13897007.28
#Sta/Elev= 30
  1088.8    79.2  1101.4   79.15  1388.8    78.1  2368.8    77.8  2448.8    77.2
  3526.8    77.7  3606.8    76.5  3676.8    77.4  3696.8    78.2  3799.4   78.67
  4356.8    76.9  4641.3      78  4783.4    77.2  4786.2   79.01  4971.5   79.21
    4976   76.26    4988   71.33  5002.4   68.63  5003.6   69.64  5021.2   72.48
  5030.6   76.19  5040.2   79.11  5088.5   75.84  5162.5   75.23  5499.4   76.88
  5650.5    77.6  5860.5    76.8  5960.5    78.3  6080.5    78.1  6138.8    79.9
#Mann= 6 , 1 , 0
  1088.8      .2       0  1101.4     .99       0  3799.4      .1       0
  4971.5     .04       0  5040.2      .1       0  5499.4      .2       0
#XS Ineff= 2 , 0
       0    4960    78.5    5050       0      78
Permanent Ineff=
       F       F
Bank Sta=4971.5,5040.2
XS Rating Curve= 0
Exp/Cntr=.5,.3

Type RM Length L Ch R = 1 ,17042.2 ,715.4,666,662.8
BEGIN DESCRIPTION:
Cross Section 17042.2
END DESCRIPTION:
XS GIS Cut Line= 6
      3111542.32     13902342.79      3112047.34     13899931.34
      3112166.14      13898862.2      3112183.96     13898297.93
       3112189.9     13898119.74      3112136.53     13897003.35
#Sta/Elev= 30
     803    79.2    1513      78    1843    79.3    2053      77    3143      78
    3200   80.91    3243    79.6  3316.8    81.1  3366.8    78.1  3706.8    77.7
  3726.8    75.9  3766.8    78.3  3826.8    78.5  4452.5    78.8  4602.5    77.3
  4632.5    78.8  4968.4   78.51    4986   69.11  4999.8   67.45  5021.4   76.38
  5055.3   77.88  5185.3    78.4  5385.3    75.7  5415.3    77.8  5645.3    75.9
  5745.3    77.5  5865.3    77.8  5905.3    75.9  6176.1    77.6    6203      80
#Mann= 5 , 1 , 0
     803     .99       0    3200      .1       0  4968.4     .04       0
  5021.4      .1       0  6176.1      .2       0
#XS Ineff= 2 , 0
       0    3319    81.1               0
Permanent Ineff=
       F       F
Bank Sta=4968.4,5021.4
XS Rating Curve= 0
Exp/Cntr=.3,.1

Type RM Length L Ch R = 1 ,16376.2 ,130.2,118.8,117.1
BEGIN DESCRIPTION:
Cross Section 16376.2-Interpolated
END DESCRIPTION:
XS GIS Cut Line= 6
      3111837.11     13902660.97      3112815.28     13900460.08
      3112837.07     13898563.85       3112838.2     13898466.28
      3112861.11     13898076.69      3112838.07     13897039.61
#Sta/Elev= 30
     405    79.8    1315    78.5    1695    76.9    1825    76.8    2055    76.8
    2595   78.73  2813.5    76.9  3323.5      76  3603.5    76.8  3693.5    77.9
    4096   77.48  4644.2   77.09  4968.8   77.21  4975.7   75.07  4984.2   71.43
  4997.2   67.37  5003.8   67.25    5007    68.9  5016.3   71.46  5029.1   77.24
  5067.4    77.8  5197.4    77.6  5407.7    76.5  5467.7    77.9  5637.7    76.8
  5787.7    77.3  5977.7      76  6207.7      77  6229.2   78.81    6235    79.3
#Mann= 7 , 1 , 0
     405     .99       0    2595      .1       0    4096     .14       0
  4644.2     .07       0  4968.8     .04       0  5029.1      .1       0
  6229.2      .2       0
#XS Ineff= 2 , 0
       0    2620    78.8    5775       0   77.27
Permanent Ineff=
       F       F
Bank Sta=4968.8,5029.1
XS Rating Curve= 0
Exp/Cntr=.5,.3

Type RM Length L Ch R = 1 ,16257.4 ,56,56,56
BEGIN DESCRIPTION:
Upstream Section of Bridge/Culvert/Weir
END DESCRIPTION:
XS GIS Cut Line= 6
      3111864.91     13902977.39      3112892.71     13900570.73
      3112946.14     13899492.23      3112967.83      13898614.4
      3112968.63     13897552.63      3112979.31     13897009.37
#Sta/Elev= 30
    97.1    79.3  1137.1    77.6  1647.1    78.3  1777.1      77  2547.1    77.6
    3000   76.15  3482.1    75.5  3602.1    76.7  4082.1   76.46  4450.6   76.02
    4549    76.2  4567.9    77.2  4707.9    77.2  4744.7   78.07  4803.9   77.47
  4968.8   78.17  4984.2   71.39  4997.2   67.33  5003.8   67.21  5016.3   71.42
  5029.1    77.2  5172.9   78.21  5231.9    77.6  5255.1    76.5  5584.4    76.8
  5694.4    75.9  5943.7    76.9    6225    76.7  6259.4   78.42  6277.1    79.3
#Mann= 7 , 1 , 0
    97.1     .99       0    3000      .1       0  4082.1     .14       0
  4450.6      .1       0  4968.8     .04       0  5029.1      .1       0
  6259.4      .2       0
#XS Ineff= 2 , 0
       0    2715    78.7    5034       0   77.05
Permanent Ineff=
       F       F
Bank Sta=4968.8,5029.1
XS Rating Curve= 0
Exp/Cntr=.5,.3

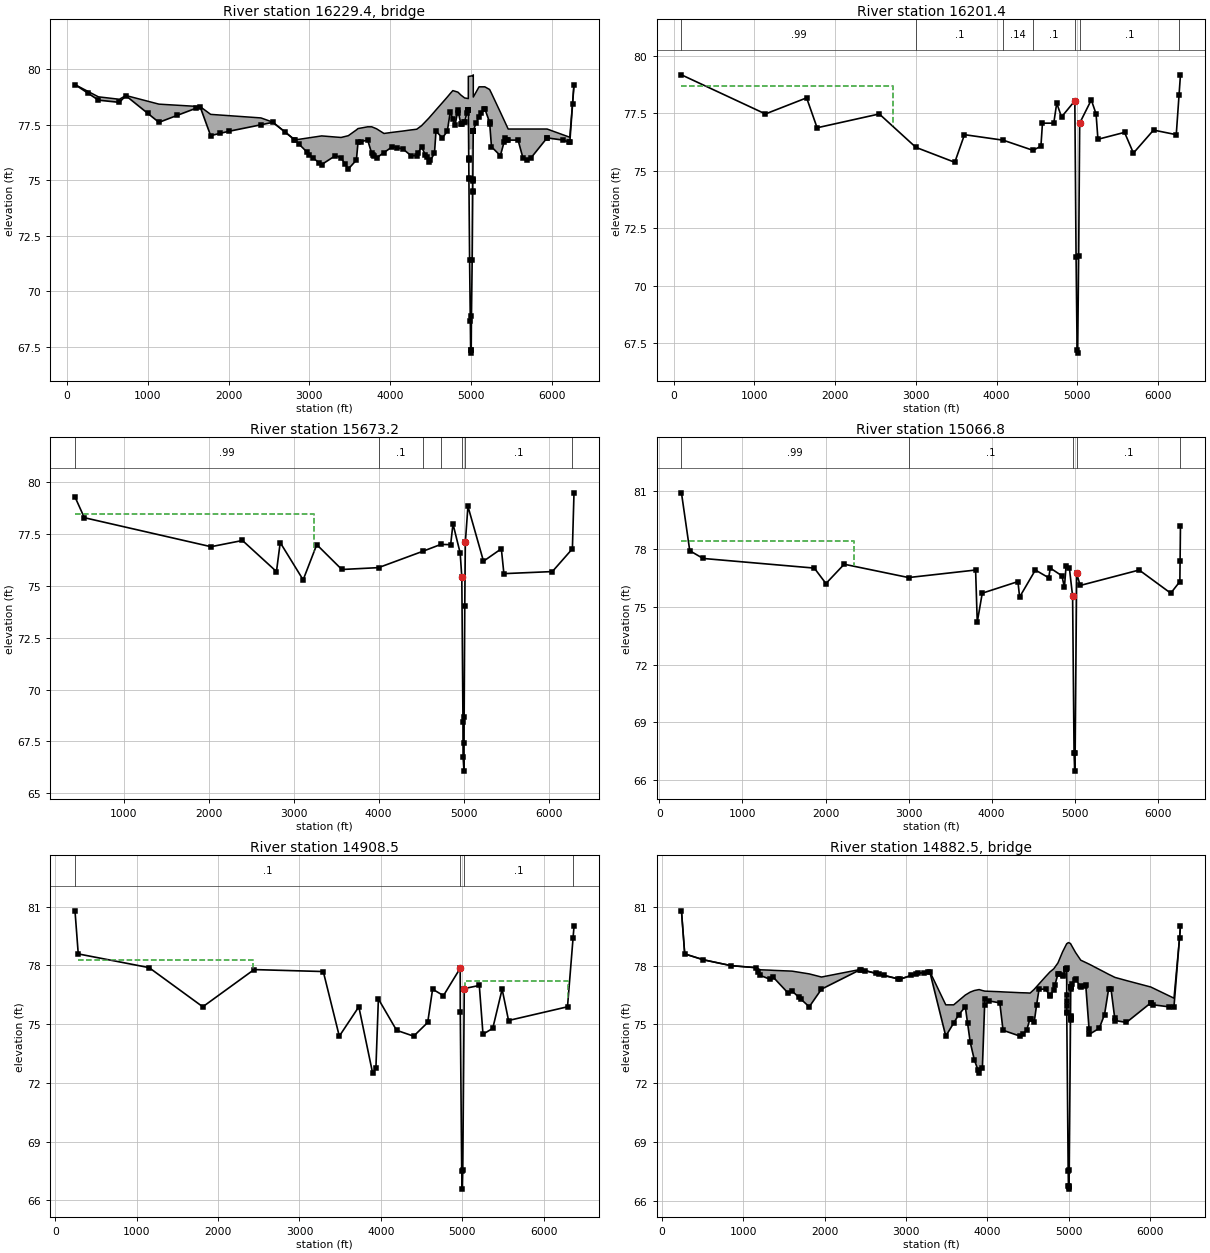
Type RM Length L Ch R = 3 ,16229.4 ,,,
BEGIN DESCRIPTION:
SELLERS ROAD
Structure ID: P38-13,,,,
END DESCRIPTION:
Bridge Culvert--1,0,-1,-1, 0
Deck Dist Width WeirC Skew NumUp NumDn MinLoCord MaxHiCord MaxSubmerge Is_Ogee
10,36,2.6,0, 60, 60, , , .95, 0, 1,1,,
    97.1   387.1   647.1   727.1  1137.1  1647.1  1777.1  2399.9  2547.1  2822.1
  3152.1  3322.1  3392.1  3482.1  3582.1  3602.1  3722.1  3772.1  3832.1  3923.8
  4025.8    4159    4259    4329    4389    4479    4549  4567.9  4647.9  4707.9
  4744.7  4776.7  4803.9  4839.7  4876.3  4922.1 4968.09  4968.2  4968.8 4973.71
  4973.8 5023.89    5024  5029.1  5029.8 5029.91  5101.1  5172.9  5231.9  5255.1
  5365.1  5425.1  5461.9  5584.4  5644.4  5694.4  5744.4  5943.7    6225  6277.1
    79.3   78.75   78.64   78.81   78.42   78.31   77.96    77.8   77.61   76.81
   76.99   76.94   76.92      77   77.26   77.32    77.4    77.4   77.31    77.1
   77.15   77.21   77.26   77.29   77.45   77.79   78.08   78.16   78.49   78.74
    78.9   79.03      79   78.96   78.83    78.7   78.67   79.67   79.67   79.67
   79.67    79.7    79.7   79.74   79.74   78.74    79.2    79.2   79.08   78.91
   78.06   77.59    77.3    77.3    77.3    77.3    77.3    77.3   76.93    79.3
    79.3    78.6    78.5    78.8    77.6    78.3      77   77.49    77.6    76.8
    75.7    76.1      76    75.5    75.9    76.7    76.8    76.2      76   76.24
    76.5    76.4    76.1    76.1    76.5    75.8    76.2    77.2    76.9    77.2
   78.07   77.75   77.47   78.15   77.52   77.61   78.16   78.17   78.17   75.94
   76.37    76.4      75    77.2   77.21   77.21   77.83   78.21    77.6    76.5
    76.1    76.9    76.8    76.8      76    75.9      76    76.9    76.7    79.3
    97.1   387.1   647.1   727.1  1137.1  1647.1  1777.1  2399.9  2547.1  2822.1
  3152.1  3322.1  3392.1  3482.1  3582.1  3602.1  3722.1  3772.1  3832.1  3923.8
  4025.8    4159    4259    4329    4389    4479    4549  4567.9  4647.9  4707.9
  4744.7  4776.7  4803.9  4839.7  4876.3  4922.1 4968.09  4968.2  4968.8 4973.71
  4973.8 5023.89    5024  5029.1  5029.8 5029.91  5101.1  5172.9  5231.9  5255.1
  5365.1  5425.1  5461.9  5584.4  5644.4  5694.4  5744.4  5943.7    6225  6277.1
    79.3   78.75   78.64   78.81   78.42   78.31   77.96    77.8   77.61   76.81
   76.99   76.94   76.92      77   77.26   77.32    77.4    77.4   77.31    77.1
   77.15   77.21   77.26   77.29   77.45   77.79   78.08   78.16   78.49   78.74
    78.9   79.03      79   78.96   78.83    78.7   78.67   79.67   79.67   79.67
   79.67    79.7    79.7   79.74   79.74   78.74    79.2    79.2   79.08   78.91
   78.06   77.59    77.3    77.3    77.3    77.3    77.3    77.3   76.93    79.3
   79.19   78.49   78.39   78.69   77.49   78.19   76.89   77.38   77.49   76.69
   75.59   75.99   75.89   75.39   75.79   76.59   76.69   76.09   75.89   76.13
   76.39   76.29   75.99   75.99   76.39   75.69   76.09   77.09   76.79   77.09
   77.96   77.64   77.36   78.04   77.41    77.5   78.05   78.06   78.06   75.83
   76.26   76.29   74.89   77.09    77.1    77.1   77.72    78.1   77.49   76.39
   75.99   76.79   76.69   76.69   75.89   75.79   75.89   76.79   76.59   79.19
Abutment Skew #Up #Dn= , 2 , 2
  4973.6  4975.7
   76.37   75.03
  4973.6  4975.7
   76.26   74.92
Abutment Skew #Up #Dn= , 2 , 2
  5022.9 5024.09
   74.52    76.4
  5022.9 5024.09
   74.41   76.29
BR Coef= 1 , 1 , 0 ,1.25, 0 ,,,.8,-1,2,0,
WSPro=,,,, 1 ,,,, 0 ,,,, 0 ,,,,-1 ,-1 ,-1 , 0 , 0 , 0 , 0 , 0
BR U #Sta/Elev= 111
    97.1    79.3   258.9   78.91   387.1    78.6   647.1    78.5   727.1    78.8
   999.9      78  1137.1    77.6  1359.9   77.91  1599.9   78.24  1647.1    78.3
  1777.1      77  1887.1    77.1  2007.1    77.2  2399.9   77.49  2547.1    77.6
  2698.9   77.16    2814   76.82  2822.1    76.8    2874   76.61    2974   76.25
    3000   76.15  3042.1      76    3124   75.78  3152.1    75.7  3322.1    76.1
  3392.1      76    3444   75.71  3482.1    75.5  3582.1    75.9  3602.1    76.7
    3634   76.73  3722.1    76.8  3772.1    76.2  3793.8   76.13  3802.1    76.1
  3832.1      76  3923.8   76.24  4025.8    76.5  4082.1   76.46    4159    76.4
    4259    76.1    4329    76.1  4343.8    76.2    4389    76.5  4433.8   76.15
  4450.6   76.02    4479    75.8    4499    75.9    4549    76.2  4567.9    77.2
  4647.9    76.9  4707.9    77.2  4744.7   78.07  4776.7   77.75  4803.9   77.47
  4839.7   78.15  4845.8   78.04  4876.3   77.52  4887.6   77.54    4920   77.61
  4922.1   77.61  4949.2   78.01 4968.09   78.16  4968.2   78.17 4968.31   78.17
  4968.8   78.17  4973.6   75.99 4973.71   75.94  4973.8   75.89  4975.6   75.08
  4975.7   75.03  4984.2   71.39    4993   68.65  4997.2   67.33  5000.9   67.34
  5003.8   67.21    5007   68.86  5016.3   71.42  5022.8   74.47  5022.9   74.52
 5023.89   74.95    5024      75  5024.1   75.04  5029.1    77.2 5029.69   77.21
  5029.8   77.21 5029.91   77.21  5063.4   77.57  5101.1   77.83  5128.8   78.02
  5167.7   78.19  5172.9   78.21  5231.9    77.6  5233.6   77.52  5255.1    76.5
  5365.1    76.1  5411.9   76.72  5425.1    76.9  5445.1    76.8  5461.9    76.8
  5584.4    76.8  5644.4      76  5694.4    75.9  5744.4      76  5943.7    76.9
  5944.4    76.9  6144.4    76.8  6213.7   76.71    6225    76.7  6259.4   78.42
  6277.1    79.3
BR U #Mann= 7
    97.1     .99    3000      .1  4082.1     .14  4450.6      .1  4968.8     .04
  5029.1      .1  6259.4      .2
BR U Banks=4968.8,5029.1
BR D #Sta/Elev= 111
    97.1   79.19   258.9    78.8   387.1   78.49   647.1   78.39   727.1   78.69
   999.9   77.89  1137.1   77.49  1359.9    77.8  1599.9   78.13  1647.1   78.19
  1777.1   76.89  1887.1   76.99  2007.1   77.09  2399.9   77.38  2547.1   77.49
  2698.9   77.05    2814   76.71  2822.1   76.69    2874    76.5    2974   76.14
    3000   76.04  3042.1   75.89    3124   75.67  3152.1   75.59  3322.1   75.99
  3392.1   75.89    3444    75.6  3482.1   75.39  3582.1   75.79  3602.1   76.59
    3634   76.62  3722.1   76.69  3772.1   76.09  3793.8   76.02  3802.1   75.99
  3832.1   75.89  3923.8   76.13  4025.8   76.39  4082.1   76.35    4159   76.29
    4259   75.99    4329   75.99  4343.8   76.09    4389   76.39  4433.8   76.04
  4450.6   75.91    4479   75.69    4499   75.79    4549   76.09  4567.9   77.09
  4647.9   76.79  4707.9   77.09  4744.7   77.96  4776.7   77.64  4803.9   77.36
  4839.7   78.04  4845.8   77.93  4876.3   77.41  4887.6   77.43    4920    77.5
  4922.1    77.5  4949.2    77.9 4968.09   78.05  4968.2   78.06 4968.31   78.06
  4968.8   78.06  4973.6   75.88 4973.71   75.83  4973.8   75.78  4975.6   74.97
  4975.7   74.92  4984.2   71.28    4993   68.54  4997.2   67.22  5000.9   67.23
  5003.8    67.1    5007   68.75  5016.3   71.31  5022.8   74.36  5022.9   74.41
 5023.89   74.84    5024   74.89  5024.1   74.93  5029.1   77.09 5029.69    77.1
  5029.8    77.1 5029.91    77.1  5063.4   77.46  5101.1   77.72  5128.8   77.91
  5167.7   78.08  5172.9    78.1  5231.9   77.49  5233.6   77.41  5255.1   76.39
  5365.1   75.99  5411.9   76.61  5425.1   76.79  5445.1   76.69  5461.9   76.69
  5584.4   76.69  5644.4   75.89  5694.4   75.79  5744.4   75.89  5943.7   76.79
  5944.4   76.79  6144.4   76.69  6213.7    76.6    6225   76.59  6259.4   78.31
  6277.1   79.19
BR D #Mann= 7
    97.1     .99    3000      .1  4082.1     .14  4450.6      .1  4968.8     .04
  5029.1      .1  6259.4      .2
BR D Banks=4968.8,5029.1
BC Design=,, 0 ,, 0 ,,,,,,

Type RM Length L Ch R = 1 ,16201.4 ,528.2,528.2,528.2
BEGIN DESCRIPTION:
Downstream Section of Bridge/Culvert/Weir
END DESCRIPTION:
XS GIS Cut Line= 6
      3111920.61     13902983.19      3112948.41     13900576.53
      3113001.84     13899498.03      3113023.53      13898620.2
      3113024.33     13897558.43      3113035.01     13897015.17
#Sta/Elev= 30
    97.1   79.17  1137.1   77.47  1647.1   78.17  1777.1   76.87  2547.1   77.47
    3000   76.02  3482.1   75.37  3602.1   76.57  4082.1   76.33  4450.6   75.89
    4549   76.07  4567.9   77.07  4707.9   77.07  4744.7   77.94  4803.9   77.34
  4968.8   78.04  4984.2   71.26  4997.2    67.2  5003.8   67.08  5016.3   71.29
  5029.1   77.07  5172.9   78.08  5231.9   77.47  5255.1   76.37  5584.4   76.67
  5694.4   75.77  5943.7   76.77    6225   76.57  6259.4   78.29  6277.1   79.17
#Mann= 7 , 1 , 0
    97.1     .99       0    3000      .1       0  4082.1     .14       0
  4450.6      .1       0  4968.8     .04       0  5029.1      .1       0
  6259.4      .2       0
#XS Ineff= 2 , 0
       0    2715    78.7    5034       0   77.05
Permanent Ineff=
       F       F
Bank Sta=4968.8,5029.1
XS Rating Curve= 0
Exp/Cntr=.5,.3

Type RM Length L Ch R = 1 ,15673.2 ,589.8,606.4,572.3
BEGIN DESCRIPTION:
Cross Section 15673.2
END DESCRIPTION:
XS GIS Cut Line= 6
      3112435.94     13902710.64      3113182.92     13900436.25
      3113525.72     13899774.71      3113555.79     13898487.71
      3113543.76     13898229.11      3113569.99     13897044.63
#Sta/Elev= 30
   429.2    79.3   539.2    78.3  2029.2    76.9  2399.2    77.2  2799.2    75.7
  2843.2    77.1  3113.2    75.3  3273.2      77  3568.2    75.8    4000   75.89
  4528.1   76.69  4732.2   77.01  4848.2      77  4875.6      78 4960.56   76.59
 4979.46   75.42 4993.06   68.46 4994.26   66.75 5005.16   66.07 5005.76   67.42
 5007.06   68.66 5014.36   74.05 5021.06   77.12 5051.56   78.85  5234.5    76.2
  5444.5    76.8  5474.5    75.6  6044.5    75.7  6280.4    76.8  6299.2    79.5
#Mann= 7 , 1 , 0
   429.2     .99       0    4000      .1       0  4528.1     .07       0
  4732.2      .1       0 4979.46     .04       0 5021.06      .1       0
  6280.4      .2       0
#XS Ineff= 2 , 0
       0    3240    78.5               0
Permanent Ineff=
       F       F
Bank Sta=4979.46,5021.06
XS Rating Curve= 0
Exp/Cntr=.3,.1

Type RM Length L Ch R = 1 ,15066.8 ,155.6,158.3,180.9
BEGIN DESCRIPTION:
Cross Section 15066.8-Interpolated
END DESCRIPTION:
XS GIS Cut Line= 5
      3112990.52     13902939.31      3114098.64      13899955.9
      3114167.39     13898557.95      3114121.56     13898099.61
      3114121.56     13897132.43
#Sta/Elev= 30
   264.9    80.9   364.9    77.9   524.9    77.5  1864.9      77  2004.9    76.2
  2224.9    77.2    3000   76.51  3807.5    76.9  3827.5    74.2  3887.5    75.7
  4317.5    76.3  4337.5    75.5  4527.5    76.9  4687.5    76.5  4707.5      77
  4847.1    76.6  4877.1      76  4897.1    77.1  4937.1      77  4975.9   75.54
  4993.4   67.41  5001.1   66.48  5006.5   67.44  5024.7   76.72  5067.1    76.1
  5777.7    76.9  6157.7    75.7  6267.7    76.3  6270.3   77.35  6274.9    79.2
#Mann= 5 , 1 , 0
   264.9     .99       0    3000      .1       0  4975.9     .04       0
  5024.7      .1       0  6270.3      .2       0
#XS Ineff= 2 , 0
       0    2338    78.4               0
Permanent Ineff=
       F       F
Bank Sta=4975.9,5024.7
XS Rating Curve= 0
Exp/Cntr=.5,.3

Type RM Length L Ch R = 1 ,14908.5 ,52,52,52
BEGIN DESCRIPTION:
Upstream Section of Bridge/Culvert/Weir
END DESCRIPTION:
XS GIS Cut Line= 6
      3113482.52     13903003.03      3114173.25     13901711.99
      3114268.25     13899356.65      3114297.94     13898703.49
      3114304.75     13898284.39      3114302.72     13897048.84
#Sta/Elev= 30
   242.8   80.79   282.8   78.59  1152.8   77.89  1812.8   75.89  2442.8   77.79
  3292.8   77.69  3489.7   74.39  3729.7   75.89  3899.7   72.49  3939.7   72.79
  3969.7   76.29  4193.3   74.69  4403.3   74.39  4575.6   75.09  4635.6   76.79
  4769.2   76.46    4975   77.86  4975.8   75.64  4993.4   67.51  5001.1   66.58
  5006.5   67.54  5024.7   76.82  5209.5   76.98  5254.9   74.49  5374.9   74.79
  5489.9   76.79  5568.7   75.19    6293   75.89  6361.1   79.39  6372.8   79.99
#Mann= 4 , 1 , 0
   242.8      .1       0    4975     .04       0  5024.7      .1       0
  6361.1      .2       0
#XS Ineff= 3 ,-1
     275    2430    78.3    3290    4965      76    5032    6300    77.2
Permanent Ineff=
       F       F       F
Bank Sta=4975,5024.7
XS Rating Curve= 0
Exp/Cntr=.5,.3

Type RM Length L Ch R = 3 ,14882.5 ,,,
BEGIN DESCRIPTION:
HENRY ROAD
Structure ID: P38-11
END DESCRIPTION:
Bridge Culvert--1,0,-1,-1, 0
Deck Dist Width WeirC Skew NumUp NumDn MinLoCord MaxHiCord MaxSubmerge Is_Ogee
10,32,2.6,0, 60, 60, , , .95, 0, 1,1,,
   242.8   282.8   512.8   852.8  1152.8  1212.8  1332.8  1372.8  1552.8  1602.8
  1812.8  1962.8  2442.8  2922.8  3142.8  3292.8  3489.7    3587  3649.7  3729.7
  3789.7  3839.7  3899.7  3939.7  3969.7  4153.3  4193.3  4403.3  4483.3  4525.6
  4575.6  4635.6  4715.6  4769.2  4816.4  4867.7  4925.2    4975 4975.61  4975.7
  4996.9 5022.19  5022.3  5024.7  5039.4  5084.4    5148  5209.5  5254.9  5374.9
  5439.9  5489.9  5519.9  5568.7  5708.7  6008.7  6038.7    6293  6361.1  6372.8
    80.8    78.6    78.3      78    77.9   77.79   77.77   77.76   77.73   77.72
   77.58   77.42   77.81   77.31   77.61   77.71      76      76   76.22    76.5
   76.65   76.73   76.78   76.73    76.7   76.67   76.66   76.62   76.61    76.6
   76.79   77.07   77.44   77.68   77.84   78.14   78.71   79.12   79.12   79.12
   79.18   79.13   79.13   79.11      79   78.67   78.28   78.16   78.07   77.81
   77.67   77.56    77.5    77.4   77.24   76.91   76.85   76.34   79.41      80
    80.8    78.6    78.3      78    77.9    77.5    77.3    77.4    76.6    76.7
    75.9    76.8    77.8    77.3    77.6    77.7    74.4   75.07    75.5    75.9
    74.1    73.2    72.5    72.8    76.3    76.1    74.7    74.4    74.7    75.3
    75.1    76.8    76.8   76.47   76.78   77.58   77.48   77.87   76.18   76.97
   77.03   76.98   75.38   76.83   77.07   77.34   76.89   76.99    74.5    74.8
    75.5    76.8    76.8    75.2    75.1    76.1      76    75.9    79.4      80
   242.8   282.8   512.8   852.8  1152.8  1212.8  1332.8  1372.8  1552.8  1602.8
  1812.8  1962.8  2442.8  2922.8  3142.8  3292.8  3489.7    3587  3649.7  3729.7
  3789.7  3839.7  3899.7  3939.7  3969.7  4153.3  4193.3  4403.3  4483.3  4525.6
  4575.6  4635.6  4715.6  4769.2  4816.4  4867.7  4925.2    4975 4975.61  4975.7
  4996.9 5022.19  5022.3  5024.7  5039.4  5084.4    5148  5209.5  5254.9  5374.9
  5439.9  5489.9  5519.9  5568.7  5708.7  6008.7  6038.7    6293  6361.1  6372.8
    80.8    78.6    78.3      78    77.9   77.79   77.77   77.76   77.73   77.72
   77.58   77.42   77.81   77.31   77.61   77.71      76      76   76.22    76.5
   76.65   76.73   76.78   76.73    76.7   76.67   76.66   76.62   76.61    76.6
   76.79   77.07   77.44   77.68   77.84   78.14   78.71   79.12   79.12   79.12
   79.18   79.13   79.13   79.11      79   78.67   78.28   78.16   78.07   77.81
   77.67   77.56    77.5    77.4   77.24   76.91   76.85   76.34   79.41      80
   80.21   78.01   77.71   77.41   77.31   76.91   76.71   76.81   76.01   76.11
   75.31   76.21   77.21   76.71   77.01   77.11   73.81   74.48   74.91   75.31
   73.51   72.61   71.91   72.21   75.71   75.51   74.11   73.81   74.11   74.71
   74.51   76.21   76.21   75.88   76.19   76.99   76.89   77.28   75.59   76.38
   76.44   76.39   74.79   76.24   76.48   76.75    76.3    76.4   73.91   74.21
   74.91   76.21   76.21   74.61   74.51   75.51   75.41   75.31   78.81   79.41
BR Coef= 1 , 1 , 0 ,1.25, 0 ,,,.8,0,2,0,
WSPro=,,,, 1 ,,,, 0 ,,,, 0 ,,,,-1 ,-1 ,-1 , 0 , 0 , 0 , 0 , 0
BR U #Sta/Elev= 108
   242.8    80.8   282.8    78.6   512.8    78.3   852.8      78  1152.8    77.9
  1187.2   77.67  1212.8    77.5  1332.8    77.3  1372.8    77.4  1552.8    76.6
  1602.8    76.7  1681.2    76.4    1707    76.3  1812.8    75.9  1962.8    76.8
    2437   77.79  2442.8    77.8    2497   77.74    2627   77.61    2667   77.57
    2727    77.5    2897   77.33  2922.8    77.3    3067    77.5    3127   77.58
  3142.8    77.6    3217   77.65    3277   77.69  3292.8    77.7  3489.7    74.4
    3587   75.07  3649.7    75.5  3729.7    75.9    3757   75.08  3789.7    74.1
  3839.7    73.2    3887   72.65  3899.7    72.5  3939.7    72.8    3967   75.99
  3969.7    76.3  4019.7    76.2  4153.3    76.1  4193.3    74.7  4403.3    74.4
  4433.3    74.5  4483.3    74.7  4525.6    75.3  4534.2   75.27  4575.6    75.1
  4605.6      76  4635.6    76.8  4715.6    76.8    4766   76.49  4769.2   76.47
  4816.4   76.78  4829.6   76.99  4867.7   77.58  4879.5   77.56  4925.2   77.48
  4931.5   77.53 4967.39   77.81  4967.5   77.81 4967.61   77.81    4975   77.87
  4975.5   76.48 4975.61   76.18  4975.7   75.93  4975.8   75.65  4975.9    75.6
  4993.4   67.52  4996.9   66.75  4998.8   66.68  5001.1   66.59    5004   66.74
  5006.5   67.55    5022   75.21  5022.1   75.26 5022.19   75.31  5022.3   75.38
  5022.4   75.44  5024.7   76.83 5029.19    76.9  5029.3   76.91 5029.41   76.91
  5039.4   77.07  5074.8   77.28  5084.4   77.34  5138.5   76.96    5148   76.89
  5196.2   76.97  5209.5   76.99  5250.1   74.76  5254.9    74.5  5374.9    74.8
  5439.9    75.5  5489.9    76.8  5519.9    76.8  5564.2   75.35  5568.7    75.2
  5708.7    75.1  6008.7    76.1  6014.2   76.08  6038.7      76  6228.7    75.9
    6293    75.9  6361.1    79.4  6372.8      80
BR U #Mann= 4
   242.8      .1    4975     .04  5024.7      .1  6361.1      .2
BR U Banks=4975,5024.7
BR D #Sta/Elev= 108
   242.8   80.21   282.8   78.01   512.8   77.71   852.8   77.41  1152.8   77.31
  1187.2   77.08  1212.8   76.91  1332.8   76.71  1372.8   76.81  1552.8   76.01
  1602.8   76.11  1681.2   75.81    1707   75.71  1812.8   75.31  1962.8   76.21
    2437    77.2  2442.8   77.21    2497   77.15    2627   77.02    2667   76.98
    2727   76.91    2897   76.74  2922.8   76.71    3067   76.91    3127   76.99
  3142.8   77.01    3217   77.06    3277    77.1  3292.8   77.11  3489.7   73.81
    3587   74.48  3649.7   74.91  3729.7   75.31    3757   74.49  3789.7   73.51
  3839.7   72.61    3887   72.06  3899.7   71.91  3939.7   72.21    3967    75.4
  3969.7   75.71  4019.7   75.61  4153.3   75.51  4193.3   74.11  4403.3   73.81
  4433.3   73.91  4483.3   74.11  4525.6   74.71  4534.2   74.68  4575.6   74.51
  4605.6   75.41  4635.6   76.21  4715.6   76.21    4766    75.9  4769.2   75.88
  4816.4   76.19  4829.6    76.4  4867.7   76.99  4879.5   76.97  4925.2   76.89
  4931.5   76.94 4967.39   77.22  4967.5   77.22 4967.61   77.22    4975   77.28
  4975.5   75.89 4975.61   75.59  4975.7   75.34  4975.8   75.06  4975.9   75.01
  4993.4   66.93  4996.9   66.16  4998.8   66.09  5001.1      66    5004   66.15
  5006.5   66.96    5022   74.62  5022.1   74.67 5022.19   74.72  5022.3   74.79
  5022.4   74.85  5024.7   76.24 5029.19   76.31  5029.3   76.32 5029.41   76.32
  5039.4   76.48  5074.8   76.69  5084.4   76.75  5138.5   76.37    5148    76.3
  5196.2   76.38  5209.5    76.4  5250.1   74.17  5254.9   73.91  5374.9   74.21
  5439.9   74.91  5489.9   76.21  5519.9   76.21  5564.2   74.76  5568.7   74.61
  5708.7   74.51  6008.7   75.51  6014.2   75.49  6038.7   75.41  6228.7   75.31
    6293   75.31  6361.1   78.81  6372.8   79.41
BR D #Mann= 4
   242.8      .1    4975     .04  5024.7      .1  6361.1      .2
BR D Banks=4975,5024.7
BC Design=,, 0 ,, 0 ,,,,,,

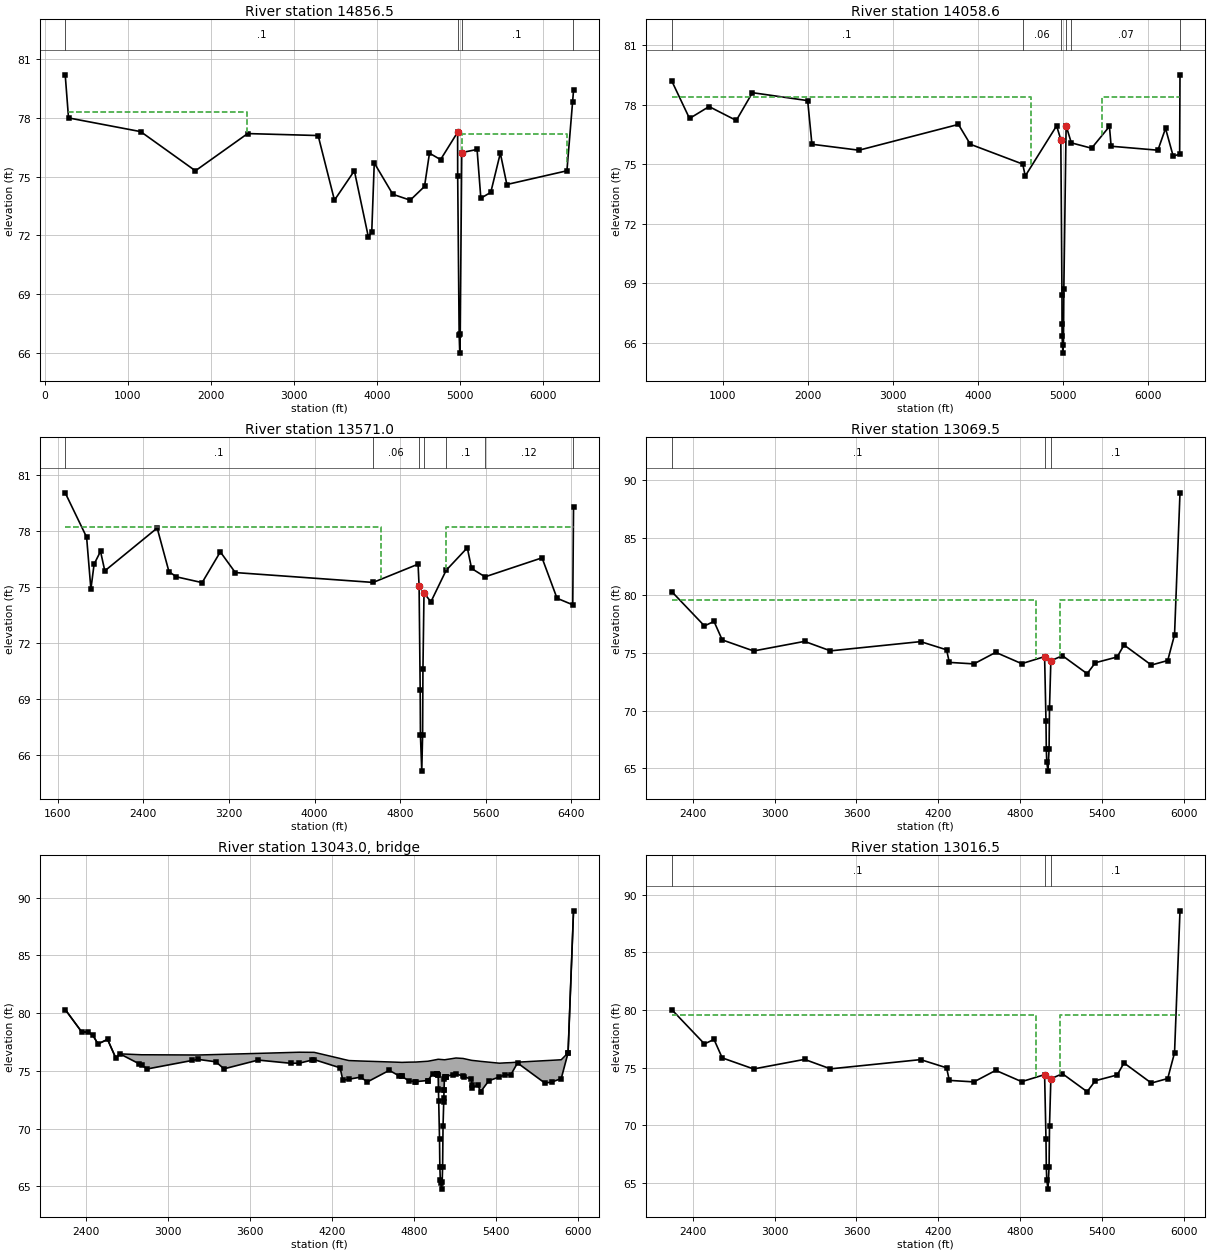
Type RM Length L Ch R = 1 ,14856.5 ,797.9,797.9,797.9
BEGIN DESCRIPTION:
Downstream Section of Bridge/Culvert/Weir
END DESCRIPTION:
XS GIS Cut Line= 6
      3113534.16     13903009.09      3114224.89     13901718.05
      3114319.89     13899362.71      3114349.58     13898709.55
      3114356.39     13898290.45      3114354.36      13897054.9
#Sta/Elev= 30
   242.8    80.2   282.8      78  1152.8    77.3  1812.8    75.3  2442.8    77.2
  3292.8    77.1  3489.7    73.8  3729.7    75.3  3899.7    71.9  3939.7    72.2
  3969.7    75.7  4193.3    74.1  4403.3    73.8  4575.6    74.5  4635.6    76.2
  4769.2   75.87    4975   77.27  4975.8   75.05  4993.4   66.92  5001.1   65.99
  5006.5   66.95  5024.7   76.23  5209.5   76.39  5254.9    73.9  5374.9    74.2
  5489.9    76.2  5568.7    74.6    6293    75.3  6361.1    78.8  6372.8    79.4
#Mann= 4 , 1 , 0
   242.8      .1       0    4975     .04       0  5024.7      .1       0
  6361.1      .2       0
#XS Ineff= 3 ,-1
     275    2430    78.3    3290    4965    75.8    5032    6300    77.2
Permanent Ineff=
       F       F       F
Bank Sta=4975,5024.7
XS Rating Curve= 0
Exp/Cntr=.5,.3

Type RM Length L Ch R = 1 ,14058.6 ,509.6,487.6,484.9
BEGIN DESCRIPTION:
Cross Section 14058.6
END DESCRIPTION:
XS GIS Cut Line= 5
      3113756.71      13902835.8      3114657.86     13901204.97
      3115093.44     13899400.43      3115166.04     13898342.59
      3115184.52     13897142.67
#Sta/Elev= 30
     398    79.2     608    77.3     838    77.9    1158    77.2    1348    78.6
    1998    78.2    2048      76  2601.2    75.7  3771.2      77  3911.2      76
  4527.6      75  4557.6    74.4  4926.5   76.93    4976   76.23  4989.5    68.4
  4989.9   66.94  4990.7   66.33  5000.1   65.47  5007.1   65.88  5011.5    68.7
  5038.3   76.93  5099.6   76.07  5337.9    75.8  5547.9    76.9  5567.9    75.9
  6117.9    75.7  6207.9    76.8  6297.9    75.4  6373.9    75.5    6378    79.5
#Mann= 6 ,-1 , 0
     398      .1       0  4527.6     .06       0    4976     .04       0
  5038.3     .06       0  5099.6     .07       0  6373.9      .2       0
#XS Ineff= 2 , 0
       0    4621    78.4    5455       0    78.4
Permanent Ineff=
       F       F
Bank Sta=4976,5038.3
XS Rating Curve= 0
Exp/Cntr=.3,.1

Type RM Length L Ch R = 1 ,13571.0 ,475.7,501.5,591.1
BEGIN DESCRIPTION:
Cross Section 13571.0-Interpolated
END DESCRIPTION:
XS GIS Cut Line= 5
      3115455.29     13901890.04      3115411.22     13901412.58
      3115611.17     13899314.22        3115657.     13898076.69
       3115680.1     13897152.71
#Sta/Elev= 30
  1670.4   80.06  1870.4   77.68  1910.4   74.89  1940.4   76.23  2000.4   76.92
  2040.4   75.87  2529.8   78.17  2639.8   75.83  2709.8   75.55  2949.8   75.24
  3119.8   76.89  3259.8   75.78  4547.7   75.25  4967.7   76.23  4977.3   75.04
  4987.4   69.49  4989.8   67.06  5002.2   65.12  5010.1   67.07  5013.2   70.58
  5023.1   74.68  5087.7   74.21    5230    75.9  5427.7   77.11  5467.7      76
  5593.3   75.55  6126.1   76.57  6266.1    74.4  6413.1   74.05  6420.4    79.3
#Mann= 7 ,-1 , 0
  1670.4      .1       0  4547.7     .06       0  4977.3    .035       0
  5023.1     .06       0    5230      .1       0  5593.3     .12       0
  6413.1      .2       0
#XS Ineff= 2 , 0
       0    4623    78.2    5230       0    78.2
Permanent Ineff=
       F       F
Bank Sta=4977.3,5023.1
XS Rating Curve= 0
Exp/Cntr=.5,.3

Type RM Length L Ch R = 1 ,13069.5 ,53,53,53
BEGIN DESCRIPTION:
Upstream Section of Bridge/Culvert/Weir
END DESCRIPTION:
XS GIS Cut Line= 6
      3115469.87     13901294.33      3115853.31     13899785.26
      3116132.69     13898656.69      3116150.39     13898583.91
      3116230.45     13898260.27      3116356.23     13897679.69
#Sta/Elev= 30
  2246.7   80.33  2486.7   77.35  2556.7   77.74  2616.7   76.14  2846.7   75.18
  3219.6   76.01  3409.6   75.19  4069.6   75.99  4259.6   75.28  4279.6   74.19
  4459.6   74.06  4619.6   75.06  4809.6   74.08  4977.3   74.69  4987.4   69.14
  4989.8   66.71  4993.1   65.56  5002.2   64.77  5010.1   66.72  5013.2   70.23
  5023.1   74.33  5107.9   74.77  5288.7   73.21  5348.7   74.16  5508.7   74.66
  5558.7    75.7  5758.7   73.96  5878.7   74.35  5928.7   76.58  5968.7   88.88
#Mann= 3 , 1 , 0
  2246.7      .1       0  4977.3    .035       0  5023.1      .1       0
#XS Ineff= 2 , 0
       0    4916    79.6    5087       0    79.6
Permanent Ineff=
       F       F
Bank Sta=4977.3,5023.1
XS Rating Curve= 0
Exp/Cntr=.5,.3

Type RM Length L Ch R = 3 ,13043.0 ,,,
BEGIN DESCRIPTION:
WEST HARDY ROAD
Structure ID: P38-10
END DESCRIPTION:
Bridge Culvert--1,0,-1,-1, 0
Deck Dist Width WeirC Skew NumUp NumDn MinLoCord MaxHiCord MaxSubmerge Is_Ogee
10,33,2.6,0, 50, 50, , , .95, 0, 1,1,,
  2246.7  2366.7  2416.7  2446.7  2486.7  2556.7  2616.7  2646.7  2806.7  2846.7
  3219.6  3349.6  3409.6  3659.6  3899.6  3959.6  4069.6  4259.6  4279.6  4323.8
  4409.6  4459.6  4619.6  4691.4  4712.3  4763.2  4813.3  4902.4  4938.5  4977.3
 4979.61  5020.7  5023.1  5026.7  5107.9  5160.2    5221  5227.8  5267.8  5288.7
  5348.7  5426.3  5468.7  5508.7  5558.7  5758.7  5808.7  5878.7  5928.7  5968.7
   80.32   78.39   78.34   78.14   77.34   77.73   76.13   76.48    76.4    76.4
   76.38   76.42   76.44   76.52    76.6   76.62   76.61   76.08   76.02    75.9
   75.86   75.84   75.78   75.75   75.74   75.76   75.77   75.84   75.92   76.01
   76.01   75.97   75.97   75.97   76.12   76.08   75.92   75.91   75.86   75.83
   75.76   75.67    75.7   75.72   75.76   75.89   75.92   75.97   76.57   88.87
   80.32   78.39   78.34   78.14   77.34   77.73   76.13   76.48    75.5   75.17
      76   75.79   75.18   75.94   75.66   75.67   75.98   75.27   74.18   74.28
   74.46   74.05   75.05   74.57   74.53   74.13   74.07   74.17   74.77   74.68
   73.41   73.35   74.32   74.48   74.76   74.53   74.28   73.54   73.77    73.2
   74.15   74.48   74.66   74.65   75.69   73.95   74.03   74.34   76.57   88.87
  2246.7  2366.7  2416.7  2446.7  2486.7  2556.7  2616.7  2646.7  2806.7  2846.7
  3219.6  3349.6  3409.6  3659.6  3899.6  3959.6  4069.6  4259.6  4279.6  4323.8
  4409.6  4459.6  4619.6  4691.4  4712.3  4763.2  4813.3  4902.4  4938.5  4977.3
 4979.61  5020.7  5023.1  5026.7  5107.9  5160.2    5221  5227.8  5267.8  5288.7
  5348.7  5426.3  5468.7  5508.7  5558.7  5758.7  5808.7  5878.7  5928.7  5968.7
   80.32   78.39   78.34   78.14   77.34   77.73   76.13   76.48    76.4    76.4
   76.38   76.42   76.44   76.52    76.6   76.62   76.61   76.08   76.02    75.9
   75.86   75.84   75.78   75.75   75.74   75.76   75.77   75.84   75.92   76.01
   76.01   75.97   75.97   75.97   76.12   76.08   75.92   75.91   75.86   75.83
   75.76   75.67    75.7   75.72   75.76   75.89   75.92   75.97   76.57   88.87
   80.18   78.25    78.2      78    77.2   77.59   75.99   76.34   75.36   75.03
   75.86   75.65   75.04    75.8   75.52   75.53   75.84   75.13   74.04   74.14
   74.32   73.91   74.91   74.43   74.39   73.99   73.93   74.03   74.63   74.54
   73.27   73.21   74.18   74.34   74.62   74.39   74.14    73.4   73.63   73.06
   74.01   74.34   74.52   74.51   75.55   73.81   73.89    74.2   76.43   88.73
Abutment Skew #Up #Dn= , 2 , 2
  4979.5  4981.4
   73.41   72.43
  4979.5  4981.4
   73.27   72.29
Abutment Skew #Up #Dn= , 2 , 2
  5018.2 5020.79
   72.33   73.37
  5018.2 5020.79
   72.19   73.23
BR Coef= 1 , 1 , 0 ,1.25, 0 ,,,.8,0,2,0,
WSPro=,,,, 1 ,,,, 0 ,,,, 0 ,,,,-1 ,-1 ,-1 , 0 , 0 , 0 , 0 , 0
BR U #Sta/Elev= 81
  2246.7   80.32  2366.7   78.39  2416.7   78.34  2446.7   78.14  2486.7   77.34
  2556.7   77.73  2616.7   76.13  2646.7   76.48  2787.8   75.62  2806.7    75.5
  2846.7   75.17  3177.8   75.91  3219.6      76  3349.6   75.79  3409.6   75.18
  3659.6   75.94  3899.6   75.66  3959.6   75.67  4053.8   75.94  4069.6   75.98
  4259.6   75.27  4279.6   74.18  4323.8   74.28  4409.6   74.46  4459.6   74.05
  4619.6   75.05  4691.4   74.57  4712.2   74.53  4712.3   74.53  4763.2   74.13
  4809.6   74.07  4813.3   74.07  4899.7   74.17  4902.4   74.17  4938.5   74.77
 4969.89    74.7    4970    74.7 4970.11    74.7  4976.2   74.68  4977.3   74.68
 4979.61   73.41  4979.7   73.36  4981.4   72.43  4987.4   69.13  4989.8    66.7
  4993.1   65.55  4996.7   65.31  5002.2   64.76  5006.8   65.35  5010.1   66.71
  5013.2   70.22  5018.2   72.33    5019   72.67 5020.59   73.31  5020.7   73.35
  5023.1   74.32  5026.2   74.46  5026.7   74.48 5031.89    74.5    5032    74.5
 5032.11    74.5  5086.8   74.69  5107.9   74.76  5160.2   74.53  5164.5   74.51
    5221   74.28  5225.5   73.79  5227.8   73.54  5267.8   73.77  5288.7    73.2
  5348.7   74.15  5426.3   74.48  5468.7   74.66  5508.7   74.65  5558.7   75.69
  5758.7   73.95  5808.7   74.03  5878.7   74.34  5927.8   76.53  5928.7   76.57
  5968.7   88.87
BR U #Mann= 3
  2246.7      .1  4977.3    .035  5023.1      .1
BR U Banks=4977.3,5023.1
BR D #Sta/Elev= 81
  2246.7   80.18  2366.7   78.25  2416.7    78.2  2446.7      78  2486.7    77.2
  2556.7   77.59  2616.7   75.99  2646.7   76.34  2787.8   75.48  2806.7   75.36
  2846.7   75.03  3177.8   75.77  3219.6   75.86  3349.6   75.65  3409.6   75.04
  3659.6    75.8  3899.6   75.52  3959.6   75.53  4053.8    75.8  4069.6   75.84
  4259.6   75.13  4279.6   74.04  4323.8   74.14  4409.6   74.32  4459.6   73.91
  4619.6   74.91  4691.4   74.43  4712.2   74.39  4712.3   74.39  4763.2   73.99
  4809.6   73.93  4813.3   73.93  4899.7   74.03  4902.4   74.03  4938.5   74.63
 4969.89   74.56    4970   74.56 4970.11   74.56  4976.2   74.54  4977.3   74.54
 4979.61   73.27  4979.7   73.22  4981.4   72.29  4987.4   68.99  4989.8   66.56
  4993.1   65.41  4996.7   65.17  5002.2   64.62  5006.8   65.21  5010.1   66.57
  5013.2   70.08  5018.2   72.19    5019   72.53 5020.59   73.17  5020.7   73.21
  5023.1   74.18  5026.2   74.32  5026.7   74.34 5031.89   74.36    5032   74.36
 5032.11   74.36  5086.8   74.55  5107.9   74.62  5160.2   74.39  5164.5   74.37
    5221   74.14  5225.5   73.65  5227.8    73.4  5267.8   73.63  5288.7   73.06
  5348.7   74.01  5426.3   74.34  5468.7   74.52  5508.7   74.51  5558.7   75.55
  5758.7   73.81  5808.7   73.89  5878.7    74.2  5927.8   76.39  5928.7   76.43
  5968.7   88.73
BR D #Mann= 3
  2246.7      .1  4977.3    .035  5023.1      .1
BR D Banks=4977.3,5023.1
BC Design=,, 0 ,, 0 ,,,,,,

Type RM Length L Ch R = 1 ,13016.5 ,55.5,55.5,55.5
BEGIN DESCRIPTION:
Downstream Section of Bridge/Culvert/Weir
END DESCRIPTION:
XS GIS Cut Line= 6
      3115522.87     13901294.33      3115906.31     13899785.26
      3116185.69     13898656.69      3116203.39     13898583.91
      3116283.45     13898260.27      3116409.23     13897679.69
#Sta/Elev= 30
  2246.7   80.04  2486.7   77.06  2556.7   77.45  2616.7   75.85  2846.7   74.89
  3219.6   75.72  3409.6    74.9  4069.6    75.7  4259.6   74.99  4279.6    73.9
  4459.6   73.77  4619.6   74.77  4809.6   73.79  4977.3    74.4  4987.4   68.85
  4989.8   66.42  4993.1   65.27  5002.2   64.48  5010.1   66.43  5013.2   69.94
  5023.1   74.04  5107.9   74.48  5288.7   72.92  5348.7   73.87  5508.7   74.37
  5558.7   75.41  5758.7   73.67  5878.7   74.06  5928.7   76.29  5968.7   88.59
#Mann= 3 , 1 , 0
  2246.7      .1       0  4977.3    .035       0  5023.1      .1       0
#XS Ineff= 2 , 0
       0    4916    79.6    5087       0    79.6
Permanent Ineff=
       F       F
Bank Sta=4977.3,5023.1
XS Rating Curve= 0
Exp/Cntr=.5,.3