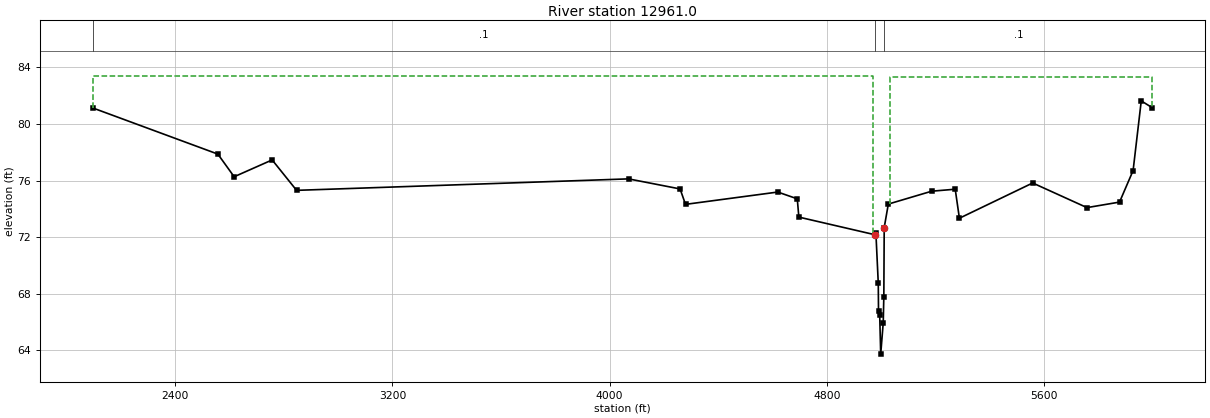
HEC-RAS study P138-00-00.prj: P138-00-00

--- P138-00-00.g01 (geometry) --- (continued)

Type RM Length L Ch R = 1 ,12961.0 ,50,50,50
BEGIN DESCRIPTION:
Upstream Section of Bridge/Culvert/Weir
END DESCRIPTION:
XS GIS Cut Line= 6
      3115516.06     13901435.24      3115822.36     13900305.05
      3116227.03      13898698.9      3116246.08      13898624.4
      3116265.21     13898555.36      3116474.12     13897650.92
#Sta/Elev= 30
  2095.8   81.13  2556.7   77.87  2616.7   76.27  2756.7   77.46  2846.7   75.31
  4069.6   76.12  4259.6   75.41  4279.6   74.32  4619.6   75.19  4691.4   74.71
  4697.2   73.42  4976.2   72.18  4981.1   72.28  4989.8   68.75  4990.7   66.76
  4995.1   66.49  4998.8   63.74  5008.1   65.96  5010.3   67.81  5011.7   72.68
  5026.8   74.34  5186.7   75.25  5273.3   75.39  5288.7   73.34  5558.7   75.83
  5758.7   74.09  5878.7   74.48  5928.7   76.71  5958.7   81.63  5999.9   81.14
#Mann= 3 , 1 , 0
  2095.8      .1       0  4976.2     .04       0  5011.7      .1       0
#XS Ineff= 2 , 0
       0    4971    83.4    5032       0    83.3
Permanent Ineff=
       F       F
Bank Sta=4976.2,5011.7
XS Rating Curve= 0
Exp/Cntr=.5,.3