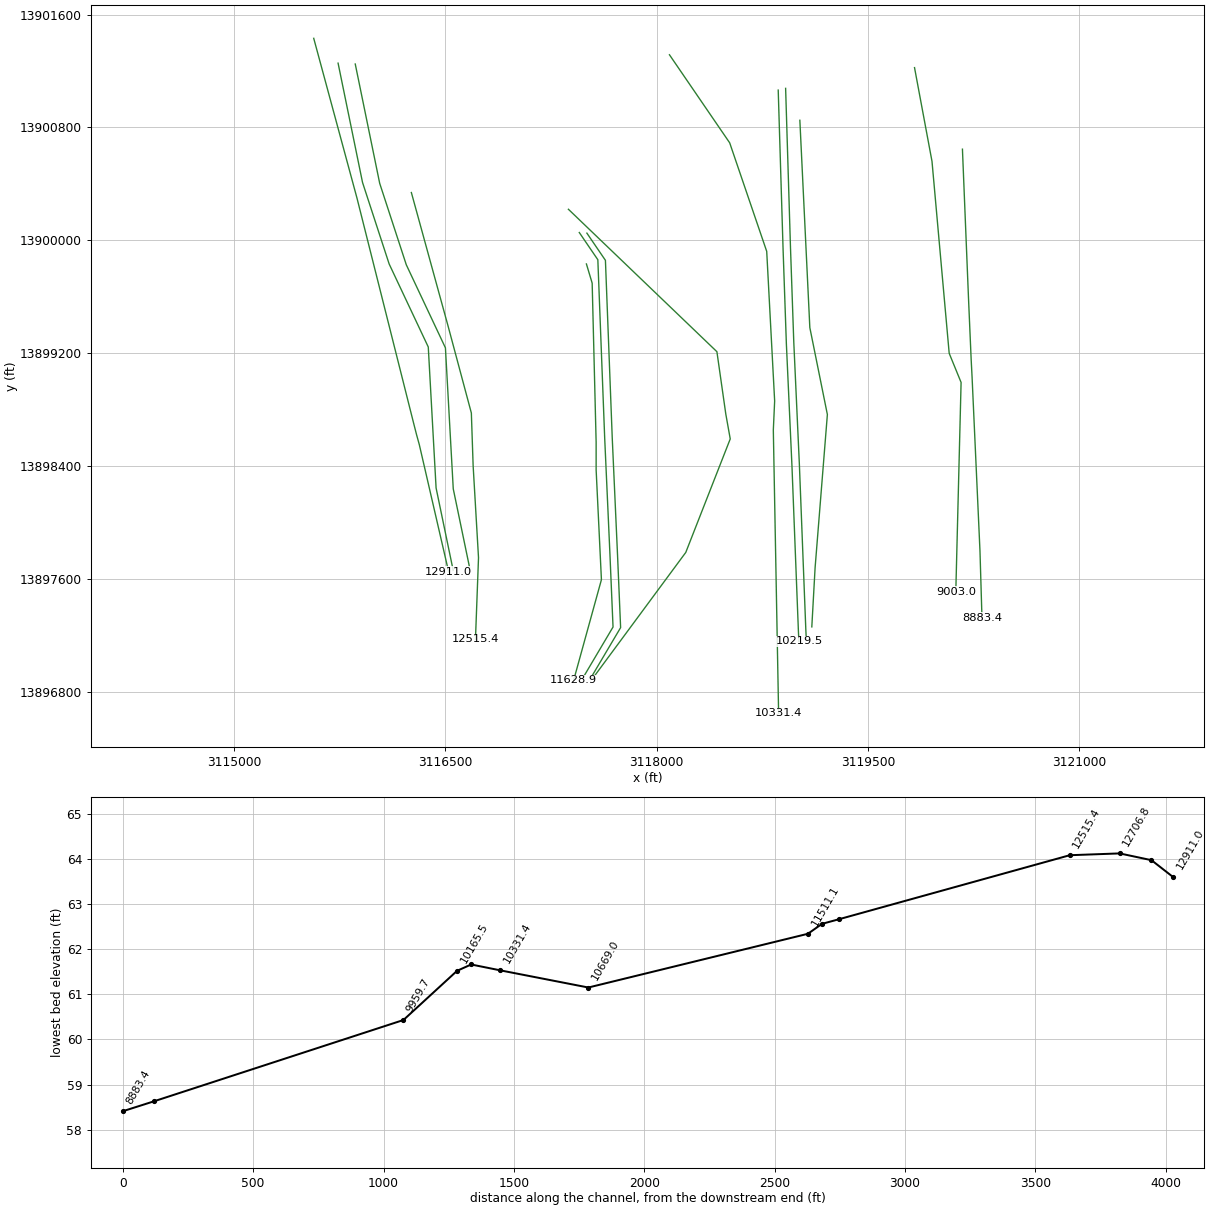
HEC-RAS study P138-00-00.prj: P138-00-00

--- P138-00-00.g01 (geometry) --- (continued)

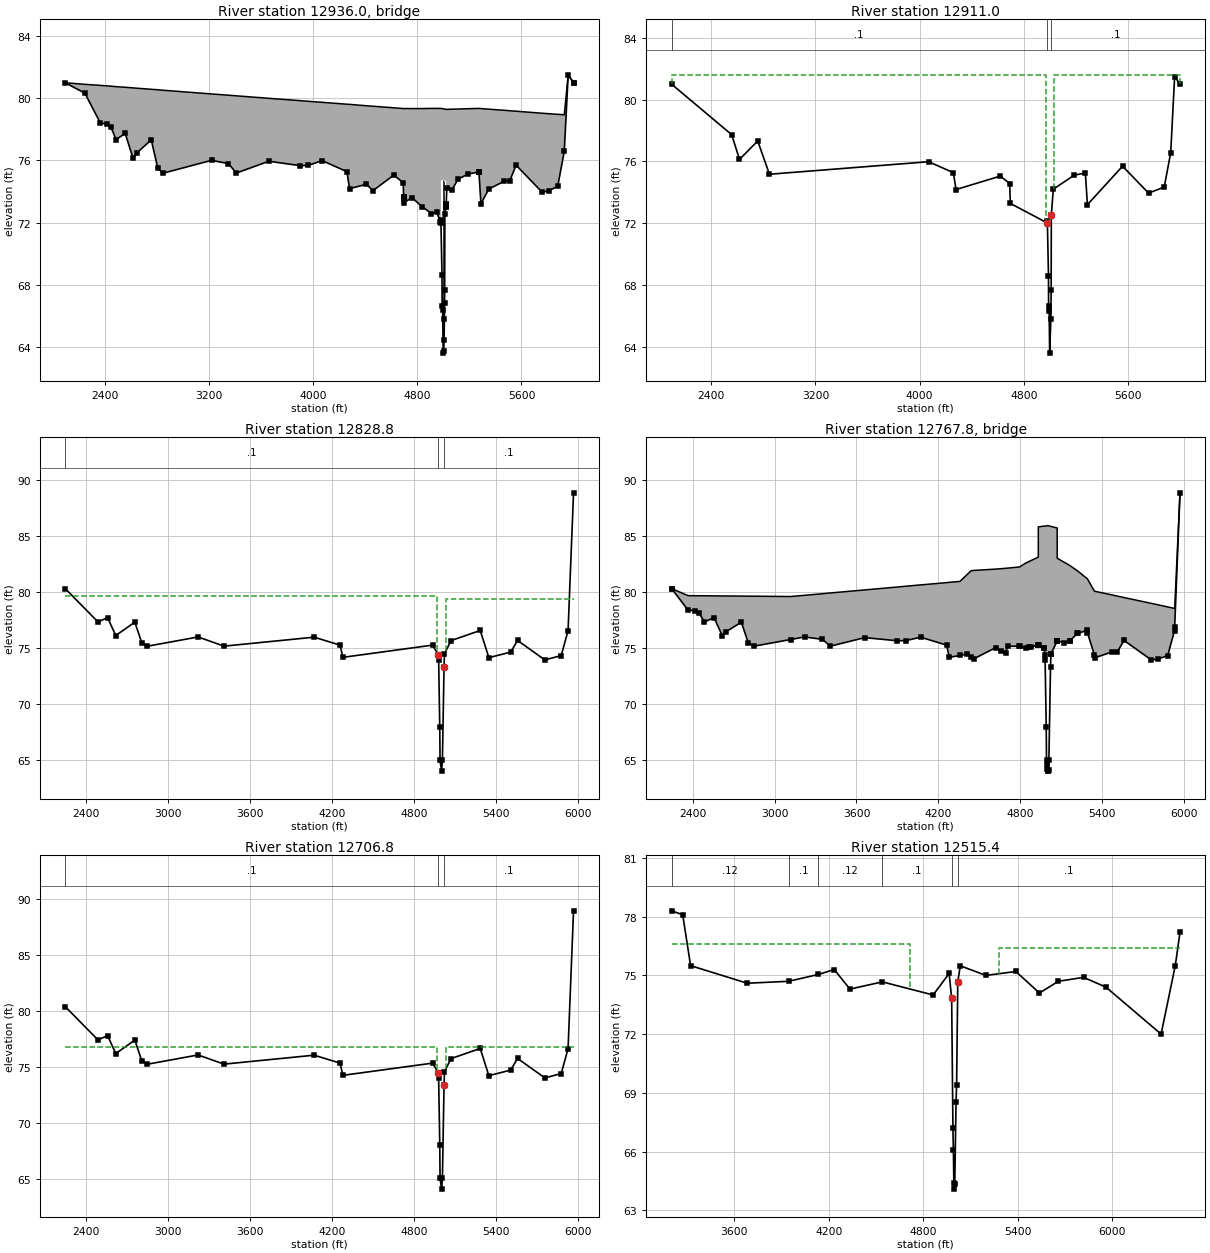
Type RM Length L Ch R = 3 ,12936.0 ,,,
BEGIN DESCRIPTION:
MISSOURI PACIFIC RAILROAD
Structure ID: P38-09
END DESCRIPTION:
Bridge Culvert--1,0,-1,-1, 0
Deck Dist Width WeirC Skew NumUp NumDn MinLoCord MaxHiCord MaxSubmerge Is_Ogee
10,30,2.6,0, 53, 53, , , .95, 0, 1,1,,
  2095.8  2246.6  2366.7  2416.7  2446.7  2486.7  2556.7  2616.7  2646.7  2756.7
  2806.7  2846.7  3219.6  3349.6  3409.6  3659.6  3899.6  3959.6  4069.6  4259.6
  4279.6  4409.6  4459.6  4619.6  4691.4  4697.2  4759.2  4834.8  4908.9  4950.3
  4976.2  4981.1 4981.43  4981.5 5021.59  5021.7  5026.8  5067.5  5112.5  5186.7
  5272.9  5273.3  5288.7  5348.7  5468.7  5508.7  5558.7  5758.7  5808.7  5878.7
  5928.7  5958.7  5999.9
   80.99   80.89   80.82   80.79   80.77   80.74    80.7   80.66   80.64   80.57
   80.54   80.51   80.27   80.19   80.15   79.99   79.84    79.8   79.73   79.61
    79.6   79.51   79.48   79.38   79.33   79.33   79.33   79.33   79.34   79.34
   79.34   79.34   79.34   79.34   79.28   79.28   79.28   79.29    79.3   79.32
   79.34   79.34   79.33   79.29   79.22   79.19   79.16   79.03      79   78.96
   78.93    81.5      81
   80.99   80.32   78.39   78.34   78.14   77.34   77.73   76.13   76.48   77.32
    75.5   75.17      76   75.79   75.18   75.94   75.66   75.67   75.98   75.27
   74.18   74.46   74.05   75.05   74.57   73.28    73.6   73.03   72.58   72.66
   72.04   72.14   72.01   74.74   74.68   73.17    74.2   74.12   74.78   75.11
   75.25   75.25    73.2   74.15   74.66   74.65   75.69   73.95   74.03   74.34
   76.57   81.49      81
  2095.8  2246.6  2366.7  2416.7  2446.7  2486.7  2556.7  2616.7  2646.7  2756.7
  2806.7  2846.7  3219.6  3349.6  3409.6  3659.6  3899.6  3959.6  4069.6  4259.6
  4279.6  4409.6  4459.6  4619.6  4691.4  4697.2  4759.2  4834.8  4908.9  4950.3
  4976.2  4981.1 4981.43  4981.5 5021.59  5021.7  5026.8  5067.5  5112.5  5186.7
  5272.9  5273.3  5288.7  5348.7  5468.7  5508.7  5558.7  5758.7  5808.7  5878.7
  5928.7  5958.7  5999.9
   80.99   80.89   80.82   80.79   80.77   80.74    80.7   80.66   80.64   80.57
   80.54   80.51   80.27   80.19   80.15   79.99   79.84    79.8   79.73   79.61
    79.6   79.51   79.48   79.38   79.33   79.33   79.33   79.33   79.34   79.34
   79.34   79.34   79.34   79.34   79.28   79.28   79.28   79.29    79.3   79.32
   79.34   79.34   79.33   79.29   79.22   79.19   79.16   79.03      79   78.96
   78.93    81.5      81
   80.94   80.27   78.34   78.29   78.09   77.29   77.68   76.08   76.43   77.27
   75.45   75.12   75.95   75.74   75.13   75.89   75.61   75.62   75.93   75.22
   74.13   74.41      74      75   74.52   73.23   73.55   72.98   72.53   72.61
   71.99   72.09   71.96   74.69   74.63   73.12   74.15   74.07   74.73   75.06
    75.2    75.2   73.15    74.1   74.61    74.6   75.64    73.9   73.98   74.29
   76.52   81.44   80.95
Pier Skew, UpSta & Num, DnSta & Num=  ,4995.1, 2 ,4995.1, 2 , 0 , 0 , 0 ,,
       1       1
   64.98   75.72
       1       1
   64.93   75.67
Pier Skew, UpSta & Num, DnSta & Num=  ,5008.1, 2 ,5008.1, 2 , 0 , 0 , 0 ,,
       1       1
   64.54    75.7
       1       1
   64.49   75.65
BR Coef= 1 , 1 , 0 ,1.25, 0 ,,,.8,0,2,0,
WSPro=,,,, 1 ,,,, 0 ,,,, 0 ,,,,-1 ,-1 ,-1 , 0 , 0 , 0 , 0 , 0
BR U #Sta/Elev= 76
  2095.8   80.99  2246.6   80.32  2366.7   78.39  2416.7   78.34  2446.7   78.14
  2486.7   77.34  2556.7   77.73  2616.7   76.13  2646.7   76.48  2756.7   77.32
  2806.7    75.5  2846.7   75.17  3219.6      76  3349.6   75.79  3409.6   75.18
  3659.6   75.94  3899.6   75.66  3959.6   75.67  4069.6   75.98  4259.6   75.27
  4279.6   74.18  4409.6   74.46  4459.6   74.05  4619.6   75.05  4691.4   74.57
  4695.6   73.64 4695.69   73.62  4695.8   73.59 4695.91   73.57  4697.2   73.28
  4759.2    73.6  4834.8   73.03  4908.9   72.58  4950.3   72.66  4976.2   72.04
  4981.1   72.14  4981.2    72.1 4981.31   72.05 4981.43   72.01  4981.5   71.98
  4989.8   68.61  4990.7   66.62  4995.1   66.35  4998.8    63.6  5002.5   63.72
  5005.6   64.42  5008.1   65.82  5009.3    66.8  5010.3   67.67  5011.7   72.54
  5020.9   73.01    5021   73.03 5021.59   73.15  5021.7   73.17  5021.8   73.19
  5026.8    74.2  5067.5   74.12  5112.5   74.78  5186.7   75.11  5272.9   75.25
 5272.99   75.25  5273.1   75.25 5273.21   75.25  5273.3   75.25  5288.7    73.2
  5348.7   74.15  5468.7   74.66  5508.7   74.65  5558.7   75.69  5758.7   73.95
  5808.7   74.03  5878.7   74.34  5928.7   76.57  5958.7   81.49  5999.8      81
  5999.9      81
BR U #Mann= 3
  2095.8      .1  4976.2     .04  5011.7      .1
BR U Banks=4976.2,5011.7
BR D #Sta/Elev= 76
  2095.8   80.94  2246.6   80.27  2366.7   78.34  2416.7   78.29  2446.7   78.09
  2486.7   77.29  2556.7   77.68  2616.7   76.08  2646.7   76.43  2756.7   77.27
  2806.7   75.45  2846.7   75.12  3219.6   75.95  3349.6   75.74  3409.6   75.13
  3659.6   75.89  3899.6   75.61  3959.6   75.62  4069.6   75.93  4259.6   75.22
  4279.6   74.13  4409.6   74.41  4459.6      74  4619.6      75  4691.4   74.52
  4695.6   73.59 4695.69   73.57  4695.8   73.54 4695.91   73.52  4697.2   73.23
  4759.2   73.55  4834.8   72.98  4908.9   72.53  4950.3   72.61  4976.2   71.99
  4981.1   72.09  4981.2   72.05 4981.31      72 4981.43   71.96  4981.5   71.93
  4989.8   68.56  4990.7   66.57  4995.1    66.3  4998.8   63.55  5002.5   63.67
  5005.6   64.37  5008.1   65.77  5009.3   66.75  5010.3   67.62  5011.7   72.49
  5020.9   72.96    5021   72.98 5021.59    73.1  5021.7   73.12  5021.8   73.14
  5026.8   74.15  5067.5   74.07  5112.5   74.73  5186.7   75.06  5272.9    75.2
 5272.99    75.2  5273.1    75.2 5273.21    75.2  5273.3    75.2  5288.7   73.15
  5348.7    74.1  5468.7   74.61  5508.7    74.6  5558.7   75.64  5758.7    73.9
  5808.7   73.98  5878.7   74.29  5928.7   76.52  5958.7   81.44  5999.8   80.95
  5999.9   80.95
BR D #Mann= 3
  2095.8      .1  4976.2     .04  5011.7      .1
BR D Banks=4976.2,5011.7
BC Design=,, 0 ,, 0 ,,,,,,

Type RM Length L Ch R = 1 ,12911.0 ,82.2,82.2,82.2
BEGIN DESCRIPTION:
Downstream Section of Bridge/Culvert/Weir
END DESCRIPTION:
XS GIS Cut Line= 6
      3115565.94     13901431.87      3115872.24     13900301.67
      3116276.91     13898695.52      3116295.96     13898621.02
      3116315.09     13898551.98        3116524.     13897647.55
#Sta/Elev= 30
  2095.8   80.99  2556.7   77.73  2616.7   76.13  2756.7   77.32  2846.7   75.17
  4069.6   75.98  4259.6   75.27  4279.6   74.18  4619.6   75.05  4691.4   74.57
  4697.2   73.28  4976.2   72.04  4981.1   72.14  4989.8   68.61  4990.7   66.62
  4995.1   66.35  4998.8    63.6  5008.1   65.82  5010.3   67.67  5011.7   72.54
  5026.8    74.2  5186.7   75.11  5273.3   75.25  5288.7    73.2  5558.7   75.69
  5758.7   73.95  5878.7   74.34  5928.7   76.57  5958.7   81.49  5999.9      81
#Mann= 3 , 1 , 0
  2095.8      .1       0  4976.2     .04       0  5011.7      .1       0
#XS Ineff= 2 , 0
       0    4971    81.6    5032       0    81.6
Permanent Ineff=
       F       F
Bank Sta=4976.2,5011.7
XS Rating Curve= 0
Exp/Cntr=.5,.3

Type RM Length L Ch R = 1 ,12828.8 ,122,122,122
BEGIN DESCRIPTION:
Upstream Section of Bridge/Culvert/Weir
END DESCRIPTION:
XS GIS Cut Line= 6
       3115738.8     13901255.89      3115912.37      13900409.8
      3116101.25     13899832.05      3116379.01      13899243.2
      3116434.56     13898243.26       3116555.9     13897659.18
#Sta/Elev= 30
  2246.7   80.27  2486.7   77.29  2556.7   77.68  2616.7   76.08  2756.7   77.27
  2806.7   75.45  2846.7   75.12  3219.6   75.95  3409.6   75.13  4069.6   75.93
  4259.6   75.22  4279.6   74.13  4936.1   75.22  4978.5   74.37  4981.1   73.86
  4989.3   67.87  4991.3   64.93  5002.8   63.97  5008.7   64.97  5020.5   73.23
  5023.6   74.43  5070.8   75.62  5285.6   76.53  5348.7    74.1  5508.7    74.6
  5558.7   75.64  5758.7    73.9  5878.7   74.29  5928.7   76.52  5968.7   88.82
#Mann= 3 , 1 , 0
  2246.7      .1       0  4978.5     .04       0  5020.5      .1       0
#XS Ineff= 2 , 0
       0    4968    79.6    5033       0    79.3
Permanent Ineff=
       F       F
Bank Sta=4978.5,5020.5
XS Rating Curve= 0
Exp/Cntr=.5,.3

Type RM Length L Ch R = 3 ,12767.8 ,,,
BEGIN DESCRIPTION:
HARDY ROAD
Structure ID: P38-08
END DESCRIPTION:
Bridge Culvert--1,0,-1,-1, 0
Deck Dist Width WeirC Skew NumUp NumDn MinLoCord MaxHiCord MaxSubmerge Is_Ogee
10,102,2.6,0, 54, 54, , , .95, 0, 1,1,,
  2246.7  2366.7  2416.7  2446.7  2486.7  2556.7  2616.7  2646.7  2756.7  2806.7
  2846.7  3117.6  3219.6  3349.6  3409.6  3659.6  3899.6  3959.6  4069.6  4259.6
  4279.6  4357.3  4409.6  4440.1  4459.6  4619.6  4691.4  4707.4  4793.9  4837.7
 4931.19  4931.3  4975.9  4978.5  5002.8  5020.5  5069.4 5069.51  5119.1  5160.7
  5217.4  5285.6  5290.6  5342.1  5348.7  5468.7  5508.7  5558.7  5758.7  5808.7
  5878.7  5928.7  5929.7  5968.7
   80.32   79.69   79.68   79.68   79.68   79.67   79.66   79.66   79.65   79.64
   79.64   79.61   79.72   79.86   79.93    80.2   80.46   80.53   80.65   80.85
   80.88   80.96   81.57   81.92   81.94   82.06   82.13   82.15   82.25   82.59
   83.13   85.83    85.9    85.9   85.94   85.88   85.73   83.03   82.68   82.39
   81.91   81.24   81.19   80.09   80.07   79.76   79.65   79.52      79   78.87
   78.68   78.55   78.55   88.87
   80.32   78.39   78.34   78.14   77.34   77.73   76.13   76.48   77.32    75.5
   75.17   75.77      76   75.79   75.18   75.94   75.66   75.67   75.98   75.27
   74.18   74.35   74.46   74.21   74.05   75.05   74.57   75.17   75.15   74.98
   75.26   75.26   75.04   74.42   74.44   74.38   75.63   75.64   75.48   75.65
   76.31   76.58   76.39    74.4   74.15   74.66   74.65   75.69   73.95   74.03
   74.34   76.57   76.88   88.87
  2246.7  2366.7  2416.7  2446.7  2486.7  2556.7  2616.7  2646.7  2756.7  2806.7
  2846.7  3117.6  3219.6  3349.6  3409.6  3659.6  3899.6  3959.6  4069.6  4259.6
  4279.6  4357.3  4409.6  4440.1  4459.6  4619.6  4691.4  4707.4  4793.9  4837.7
 4931.19  4931.3  4975.9  4978.5  5002.8  5020.5  5069.4 5069.51  5119.1  5160.7
  5217.4  5285.6  5290.6  5342.1  5348.7  5468.7  5508.7  5558.7  5758.7  5808.7
  5878.7  5928.7  5929.7  5968.7
   80.42   79.69   79.68   79.68   79.68   79.67   79.66   79.66   79.65   79.64
   79.64   79.61   79.72   79.86   79.93    80.2   80.46   80.53   80.65   80.85
   80.88   80.96   81.57   81.92   81.94   82.06   82.13   82.15   82.25   82.59
   83.13   85.83    85.9    85.9   85.94   85.88   85.73   83.03   82.68   82.39
   81.91   81.24   81.19   80.09   80.07   79.76   79.65   79.52      79   78.87
   78.68   78.55   78.55   88.97
   80.42   78.49   78.44   78.24   77.44   77.83   76.23   76.58   77.42    75.6
   75.27   75.87    76.1   75.89   75.28   76.04   75.76   75.77   76.08   75.37
   74.28   74.45   74.56   74.31   74.15   75.15   74.67   75.27   75.25   75.08
   75.36   75.36   75.14   74.52   74.54   74.48   75.73   75.74   75.58   75.75
   76.41   76.68   76.49    74.5   74.25   74.76   74.75   75.79   74.05   74.13
   74.44   76.67   76.98   88.97
Abutment Skew #Up #Dn= , 2 , 2
  4931.8  4975.9
   75.26   75.04
  4931.8  4975.9
   75.36   75.14
Abutment Skew #Up #Dn= , 2 , 2
  5023.7 5069.79
   74.48   75.64
  5023.7 5069.79
   74.58   75.74
BR Coef= 1 , 1 , 0 ,1.25, 0 ,,,.8,-1,2,0,
WSPro=,,,, 1 ,,,, 0 ,,,, 0 ,,,,-1 ,-1 ,-1 , 0 , 0 , 0 , 0 , 0
BR U #Sta/Elev= 82
  2246.7   80.32  2247.7    80.3  2366.7   78.39  2416.7   78.34  2446.7   78.14
  2486.7   77.34  2556.7   77.73  2616.7   76.13  2646.7   76.48  2756.7   77.32
  2806.7    75.5  2846.7   75.17  3117.6   75.77  3219.6      76  3349.6   75.79
  3409.6   75.18  3659.6   75.94  3899.6   75.66  3959.6   75.67  4069.6   75.98
  4259.6   75.27  4279.6   74.18  4357.3   74.35  4409.6   74.46  4440.1   74.21
  4459.6   74.05  4619.6   75.05  4659.9   74.78  4691.4   74.57  4707.4   75.17
  4789.9   75.17  4793.9   75.15  4837.7   74.98  4862.3   75.06  4875.3    75.1
 4931.19   75.26  4931.3   75.26 4931.41   75.26  4931.8   75.26 4931.91   75.26
    4932   75.26  4936.1   75.27  4975.8   75.04  4975.9   75.04  4978.5   74.42
  4981.1   73.91  4989.3   67.92  4991.3   64.98  4994.4   64.66  4996.6   64.24
  5002.1   64.04  5002.8   64.02  5006.8   64.16  5008.7   65.02  5020.5   73.28
  5023.6   74.48  5023.7   74.48 5069.29   75.63  5069.4   75.63 5069.51   75.64
 5069.59   75.64  5069.7   75.64  5069.8   75.64  5070.8   75.67  5119.1   75.48
  5160.7   75.65  5162.5   75.66  5217.4   76.31  5218.4   76.31  5285.6   76.58
  5290.6   76.39  5342.1    74.4  5348.7   74.15  5468.7   74.66  5508.7   74.65
  5558.7   75.69  5758.7   73.95  5808.7   74.03  5878.7   74.34  5928.7   76.57
  5929.7   76.88  5968.7   88.87
BR U #Mann= 3
  2246.7      .1  4978.5     .04  5020.5      .1
BR U Banks=4978.5,5020.5
BR D #Sta/Elev= 82
  2246.7   80.42  2247.7    80.4  2366.7   78.49  2416.7   78.44  2446.7   78.24
  2486.7   77.44  2556.7   77.83  2616.7   76.23  2646.7   76.58  2756.7   77.42
  2806.7    75.6  2846.7   75.27  3117.6   75.87  3219.6    76.1  3349.6   75.89
  3409.6   75.28  3659.6   76.04  3899.6   75.76  3959.6   75.77  4069.6   76.08
  4259.6   75.37  4279.6   74.28  4357.3   74.45  4409.6   74.56  4440.1   74.31
  4459.6   74.15  4619.6   75.15  4659.9   74.88  4691.4   74.67  4707.4   75.27
  4789.9   75.27  4793.9   75.25  4837.7   75.08  4862.3   75.16  4875.3    75.2
 4931.19   75.36  4931.3   75.36 4931.41   75.36  4931.8   75.36 4931.91   75.36
    4932   75.36  4936.1   75.37  4975.8   75.14  4975.9   75.14  4978.5   74.52
  4981.1   74.01  4989.3   68.02  4991.3   65.08  4994.4   64.76  4996.6   64.34
  5002.1   64.14  5002.8   64.12  5006.8   64.26  5008.7   65.12  5020.5   73.38
  5023.6   74.58  5023.7   74.58 5069.29   75.73  5069.4   75.73 5069.51   75.74
 5069.59   75.74  5069.7   75.74  5069.8   75.74  5070.8   75.77  5119.1   75.58
  5160.7   75.75  5162.5   75.76  5217.4   76.41  5218.4   76.41  5285.6   76.68
  5290.6   76.49  5342.1    74.5  5348.7   74.25  5468.7   74.76  5508.7   74.75
  5558.7   75.79  5758.7   74.05  5808.7   74.13  5878.7   74.44  5928.7   76.67
  5929.7   76.98  5968.7   88.97
BR D #Mann= 3
  2246.7      .1  4978.5     .04  5020.5      .1
BR D Banks=4978.5,5020.5
BC Design=,, 0 ,, 0 ,,,,,,

Type RM Length L Ch R = 1 ,12706.8 ,191.4,191.4,191.4
BEGIN DESCRIPTION:
Downstream Section of Bridge/Culvert/Weir
END DESCRIPTION:
XS GIS Cut Line= 6
      3115860.65      13901249.8      3116034.21      13900403.7
      3116223.09     13899825.95      3116500.85      13899237.1
       3116556.4     13898237.16      3116677.74     13897653.09
#Sta/Elev= 30
  2246.7   80.42  2486.7   77.44  2556.7   77.83  2616.7   76.23  2756.7   77.42
  2806.7    75.6  2846.7   75.27  3219.6    76.1  3409.6   75.28  4069.6   76.08
  4259.6   75.37  4279.6   74.28  4936.1   75.37  4978.5   74.52  4981.1   74.01
  4989.3   68.02  4991.3   65.08  5002.8   64.12  5008.7   65.12  5020.5   73.38
  5023.6   74.58  5070.8   75.77  5285.6   76.68  5348.7   74.25  5508.7   74.75
  5558.7   75.79  5758.7   74.05  5878.7   74.44  5928.7   76.67  5968.7   88.97
#Mann= 3 , 1 , 0
  2246.7      .1       0  4978.5     .04       0  5020.5      .1       0
#XS Ineff= 2 , 0
       0    4968    76.8    5033       0    76.8
Permanent Ineff=
       F       F
Bank Sta=4978.5,5020.5
XS Rating Curve= 0
Exp/Cntr=.5,.3

Type RM Length L Ch R = 1 ,12515.4 ,911.3,886.5,872.3
BEGIN DESCRIPTION:
Cross Section 12515.4
END DESCRIPTION:
XS GIS Cut Line= 6
      3116259.01     13900338.43      3116519.63     13899391.54
      3116684.85     13898775.14      3116697.56     13898400.22
      3116735.68     13897748.87      3116714.02     13897169.35
#Sta/Elev= 30
  3202.7    78.3  3272.7    78.1  3322.7    75.5  3682.7    74.6  3945.7    74.7
  4134.7   75.05  4234.8    75.3  4334.8    74.3    4540   74.67  4862.9      74
 4964.55    75.1 4980.55   73.83 4988.65   67.19 4991.55   66.07 4994.45   64.39
 4997.75   64.08 5000.25   64.35 5008.45   68.55 5011.95   69.41 5019.45   74.68
 5035.45   75.49  5198.1      75  5388.1    75.2  5538.1    74.1  5658.1    74.7
  5818.1    74.9  5960.5    74.4  6310.5      72  6400.5    75.5  6430.5    77.2
#Mann= 6 , 1 , 0
  3202.7     .12       0  3945.7      .1       0  4134.7     .12       0
    4540      .1       0 4980.55     .04       0 5019.45      .1       0
#XS Ineff= 2 , 0
       0    4718    76.6    5283       0    76.4
Permanent Ineff=
       F       F
Bank Sta=4980.55,5019.45
XS Rating Curve= 0
Exp/Cntr=.3,.1

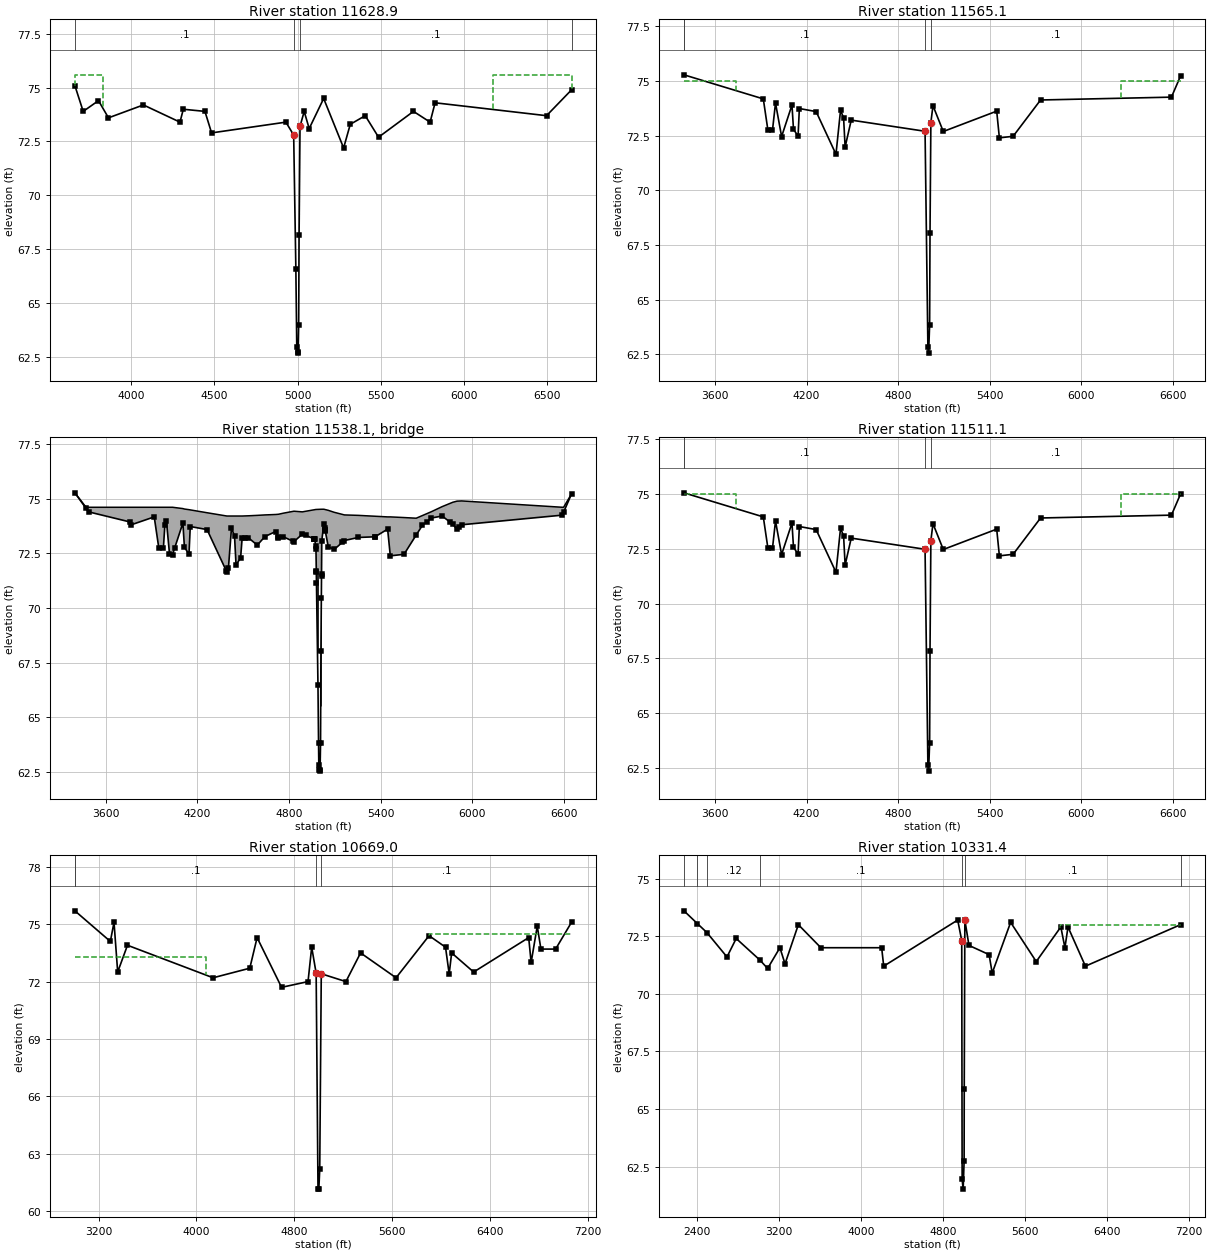
Type RM Length L Ch R = 1 ,11628.9 ,61.7,63.8,72.9
BEGIN DESCRIPTION:
Cross Section 11628.9-Interpolated
END DESCRIPTION:
XS GIS Cut Line= 6
       3117501.7     13899831.87       3117542.5     13899695.87
      3117570.66     13898569.45      3117570.66     13898372.32
      3117608.21     13897593.21      3117411.08     13896879.81
#Sta/Elev= 30
    3661    75.1    3711    73.9    3803    74.4    3863    73.6    4073    74.2
    4293    73.4    4313      74    4443    73.9    4483    72.9  4929.8    73.4
  4976.6    72.8  4989.7   66.58  4995.2   62.95  4999.9   62.66  5003.5   62.73
  5006.6   63.96  5009.1   68.14  5014.7    73.2  5039.8    73.9  5069.8    73.1
  5156.9    74.5  5276.9    72.2  5316.9    73.3  5406.9    73.7  5486.9    72.7
  5696.9    73.9  5796.9    73.4  5826.9    74.3  6496.9    73.7  6647.1    74.9
#Mann= 4 , 1 , 0
    3661      .1       0  4976.6     .04       0  5014.7      .1       0
  6647.1      .2       0
#XS Ineff= 2 , 0
       0    3828    75.6    6173       0    75.6
Permanent Ineff=
       F       F
Bank Sta=4976.6,5014.7
XS Rating Curve= 0
Exp/Cntr=.5,.3

Type RM Length L Ch R = 1 ,11565.1 ,54,54,54
BEGIN DESCRIPTION:
Upstream Section of Bridge/Culvert/Weir
END DESCRIPTION:
XS GIS Cut Line= 6
      3117451.19     13900054.74      3117582.78     13899861.94
      3117631.32     13898599.22      3117668.84     13897769.66
      3117690.63     13897257.49      3117479.03      13896900.4
#Sta/Elev= 30
  3396.3   75.28  3916.4   74.18  3946.4   72.76  3976.4   72.74  3996.4   73.99
  4036.4   72.46  4104.3    73.9  4114.3   72.79  4144.3   72.48  4152.7   73.74
  4262.7    73.6  4392.7   71.65  4422.7   73.66  4442.7   73.31  4452.7   71.98
  4492.7   73.21  4976.6    72.7  4995.2   62.85  4999.9   62.56  5006.6   63.86
  5009.1   68.04  5014.7    73.1  5028.5   73.87  5096.1   72.69  5446.2   73.62
  5463.8    72.4  5553.8   72.47  5733.8   74.13  6591.5   74.26  6651.5   75.23
#Mann= 4 , 1 , 0
  3396.3      .2       0  3396.3      .1       0  4976.6     .04       0
  5014.7      .1       0
#XS Ineff= 2 , 0
       0    3738      75    6260       0      75
Permanent Ineff=
       F       F
Bank Sta=4976.6,5014.7
XS Rating Curve= 0
Exp/Cntr=.5,.3

Type RM Length L Ch R = 3 ,11538.1 ,,,
BEGIN DESCRIPTION:
LUTHE ROAD
Structure ID: P38-06
END DESCRIPTION:
Bridge Culvert--1,0,-1,-1, 0
Deck Dist Width WeirC Skew NumUp NumDn MinLoCord MaxHiCord MaxSubmerge Is_Ogee
10,34,2.6,0, 58, 58, , , .95, 0, 1,1,,
  3396.3  3469.6  3486.3  3756.4  3766.4  3916.4  3946.4  3976.4  3986.4  3996.4
  4016.4  4036.4  4104.3  4114.3  4144.3  4152.7  4262.7  4392.7  4402.7  4422.7
  4442.7  4452.7  4482.7  4492.7  4532.7  4591.9  4641.9  4711.9  4730.1  4762.9
  4832.1  4887.3  4968.7  4976.6  4978.8  4979.8 5012.89    5013  5014.7  5028.5
  5057.4  5096.1  5163.4  5253.9  5363.8  5446.2  5463.8  5553.8  5633.4  5673.8
  5733.8  5803.8  5873.8  5901.5  5931.5  6591.5  6599.6  6651.5
   75.26    74.6    74.6    74.6    74.6    74.6    74.6    74.6    74.6    74.6
    74.6    74.6   74.54   74.52   74.49   74.48   74.35    74.2    74.2    74.2
    74.2    74.2    74.2    74.2   74.21   74.23   74.25   74.27   74.28   74.33
   74.42   74.39   74.49    74.5    74.5    74.5   74.51   74.51   74.51   74.51
   74.46   74.37   74.25   74.23   74.19   74.16   74.16   74.13    74.1   74.22
    74.4   74.63   74.83   74.88   74.89    74.6    74.6   75.21
   75.26   74.55   74.39   73.93    73.8   74.16   72.74   72.72   73.81   73.97
   72.48   72.44   73.88   72.77   72.46   73.72   73.58   71.63   71.81   73.64
   73.29   71.96   72.29   73.19   73.21   72.87   73.26   73.49    73.2   73.25
   73.03   73.37   73.15   72.68   71.64    71.6   71.61   71.54   73.08   73.85
   72.79   72.67   73.08   73.22   73.25    73.6   72.38   72.45   73.33   73.77
   74.11    74.2   73.82   73.59    73.8   74.24   74.37   75.21
  3396.3  3469.6  3486.3  3756.4  3766.4  3916.4  3946.4  3976.4  3986.4  3996.4
  4016.4  4036.4  4104.3  4114.3  4144.3  4152.7  4262.7  4392.7  4402.7  4422.7
  4442.7  4452.7  4482.7  4492.7  4532.7  4591.9  4641.9  4711.9  4730.1  4762.9
  4832.1  4887.3  4968.7  4976.6  4978.8  4979.8 5012.89    5013  5014.7  5028.5
  5057.4  5096.1  5163.4  5253.9  5363.8  5446.2  5463.8  5553.8  5633.4  5673.8
  5733.8  5803.8  5873.8  5901.5  5931.5  6591.5  6599.6  6651.5
   75.26    74.6    74.6    74.6    74.6    74.6    74.6    74.6    74.6    74.6
    74.6    74.6   74.54   74.52   74.49   74.48   74.35    74.2    74.2    74.2
    74.2    74.2    74.2    74.2   74.21   74.23   74.25   74.27   74.28   74.33
   74.42   74.39   74.49    74.5    74.5    74.5   74.51   74.51   74.51   74.51
   74.46   74.37   74.25   74.23   74.19   74.16   74.16   74.13    74.1   74.22
    74.4   74.63   74.83   74.88   74.89    74.6    74.6   75.21
   75.07   74.36    74.2   73.74   73.61   73.97   72.55   72.53   73.62   73.78
   72.29   72.25   73.69   72.58   72.27   73.53   73.39   71.44   71.62   73.45
    73.1   71.77    72.1      73   73.02   72.68   73.07    73.3   73.01   73.06
   72.84   73.18   72.96   72.49   71.45   71.41   71.42   71.35   72.89   73.66
    72.6   72.48   72.89   73.03   73.06   73.41   72.19   72.26   73.14   73.58
   73.92   74.01   73.63    73.4   73.61   74.05   74.18   75.02
Pier Skew, UpSta & Num, DnSta & Num=  ,4986.5, 2 ,4986.5, 2 , 0 , 0 , 0 ,,
      .7      .7
   66.81    72.6
      .7      .7
   66.62   72.41
Pier Skew, UpSta & Num, DnSta & Num=  ,5007.6, 2 ,5007.6, 2 , 0 , 0 , 0 ,,
      .7      .7
   63.93   72.61
      .7      .7
   63.74   72.42
Abutment Skew #Up #Dn= , 2 , 2
  4978.6  4979.8
   71.64   71.16
  4978.6  4979.8
   71.45   70.97
Abutment Skew #Up #Dn= , 2 , 2
  5011.9 5013.09
   70.55   71.61
  5011.9 5013.09
   70.36   71.42
BR Coef= 1 , 1 , 0 ,1.25, 0 ,,,.8,0,2,0,
WSPro=,,,, 1 ,,,, 0 ,,,, 0 ,,,,-1 ,-1 ,-1 , 0 , 0 , 0 , 0 , 0
BR U #Sta/Elev= 87
  3396.3   75.26  3469.6   74.55  3486.3   74.39  3756.4   73.93  3766.4    73.8
  3916.4   74.16  3946.4   72.74  3976.4   72.72  3986.4   73.81  3996.4   73.97
  4016.4   72.48  4036.4   72.44  4049.6   72.72  4104.3   73.88  4114.3   72.77
  4144.3   72.46  4152.7   73.72  4262.7   73.58  4389.6   71.68  4392.7   71.63
  4402.7   71.81  4422.7   73.64  4442.7   73.29  4452.7   71.96  4482.7   72.29
  4492.7   73.19  4509.6    73.2  4532.7   73.21  4591.9   72.87  4641.9   73.26
  4711.9   73.49  4726.7   73.25  4730.1    73.2  4762.9   73.25  4827.8   73.04
  4832.1   73.03  4887.3   73.37  4909.7   73.31 4964.79   73.16  4964.9   73.16
 4965.01   73.16  4968.7   73.15  4973.8   72.85  4976.6   72.68 4978.71   71.68
  4978.8   71.64  4979.8   71.16  4989.7   66.46  4993.5   63.81  4995.2   62.83
  4997.5    62.6  4999.9   62.54  5003.5   62.61  5006.6   63.84  5009.1   68.02
  5011.8   70.46 5012.89   71.44    5013   71.54  5014.7   73.08  5028.5   73.85
  5033.9   73.65 5036.89   73.54    5037   73.54 5037.11   73.53  5057.4   72.79
  5096.1   72.67  5147.9   72.99  5163.4   73.08  5253.9   73.22  5363.3   73.25
  5363.8   73.25  5446.2    73.6  5463.8   72.38  5553.8   72.45  5633.4   73.33
  5673.8   73.77  5703.4   73.94  5733.8   74.11  5803.8    74.2  5853.8   73.93
  5873.8   73.82  5901.5   73.59  5913.8   73.68  5931.5    73.8  6591.5   74.24
  6599.6   74.37  6651.5   75.21
BR U #Mann= 4
  3396.3      .2  3396.3      .1  4976.6     .04  5014.7      .1
BR U Banks=4976.6,5014.7
BR D #Sta/Elev= 87
  3396.3   75.07  3469.6   74.36  3486.3    74.2  3756.4   73.74  3766.4   73.61
  3916.4   73.97  3946.4   72.55  3976.4   72.53  3986.4   73.62  3996.4   73.78
  4016.4   72.29  4036.4   72.25  4049.6   72.53  4104.3   73.69  4114.3   72.58
  4144.3   72.27  4152.7   73.53  4262.7   73.39  4389.6   71.49  4392.7   71.44
  4402.7   71.62  4422.7   73.45  4442.7    73.1  4452.7   71.77  4482.7    72.1
  4492.7      73  4509.6   73.01  4532.7   73.02  4591.9   72.68  4641.9   73.07
  4711.9    73.3  4726.7   73.06  4730.1   73.01  4762.9   73.06  4827.8   72.85
  4832.1   72.84  4887.3   73.18  4909.7   73.12 4964.79   72.97  4964.9   72.97
 4965.01   72.97  4968.7   72.96  4973.8   72.66  4976.6   72.49 4978.71   71.49
  4978.8   71.45  4979.8   70.97  4989.7   66.27  4993.5   63.62  4995.2   62.64
  4997.5   62.41  4999.9   62.35  5003.5   62.42  5006.6   63.65  5009.1   67.83
  5011.8   70.27 5012.89   71.25    5013   71.35  5014.7   72.89  5028.5   73.66
  5033.9   73.46 5036.89   73.35    5037   73.35 5037.11   73.34  5057.4    72.6
  5096.1   72.48  5147.9    72.8  5163.4   72.89  5253.9   73.03  5363.3   73.06
  5363.8   73.06  5446.2   73.41  5463.8   72.19  5553.8   72.26  5633.4   73.14
  5673.8   73.58  5703.4   73.75  5733.8   73.92  5803.8   74.01  5853.8   73.74
  5873.8   73.63  5901.5    73.4  5913.8   73.49  5931.5   73.61  6591.5   74.05
  6599.6   74.18  6651.5   75.02
BR D #Mann= 4
  3396.3      .2  3396.3      .1  4976.6     .04  5014.7      .1
BR D Banks=4976.6,5014.7
BC Design=,, 0 ,, 0 ,,,,,,

Type RM Length L Ch R = 1 ,11511.1 ,842.1,842.1,842.1
BEGIN DESCRIPTION:
Downstream Section of Bridge/Culvert/Weir
END DESCRIPTION:
XS GIS Cut Line= 6
      3117505.03     13900050.53      3117636.62     13899857.72
      3117685.16       13898595.      3117722.68     13897765.44
      3117744.47     13897253.27      3117532.87     13896896.18
#Sta/Elev= 30
  3396.3   75.06  3916.4   73.96  3946.4   72.54  3976.4   72.52  3996.4   73.77
  4036.4   72.24  4104.3   73.68  4114.3   72.57  4144.3   72.26  4152.7   73.52
  4262.7   73.38  4392.7   71.43  4422.7   73.44  4442.7   73.09  4452.7   71.76
  4492.7   72.99  4976.6   72.48  4995.2   62.63  4999.9   62.34  5006.6   63.64
  5009.1   67.82  5014.7   72.88  5028.5   73.65  5096.1   72.47  5446.2    73.4
  5463.8   72.18  5553.8   72.25  5733.8   73.91  6591.5   74.04  6651.5   75.01
#Mann= 4 , 1 , 0
  3396.3      .2       0  3396.3      .1       0  4976.6     .04       0
  5014.7      .1       0
#XS Ineff= 2 , 0
       0    3738      75    6260       0      75
Permanent Ineff=
       F       F
Bank Sta=4976.6,5014.7
XS Rating Curve= 0
Exp/Cntr=.5,.3

Type RM Length L Ch R = 1 ,10669.0 ,332.2,337.6,441.5
BEGIN DESCRIPTION:
Cross Section 10669.0
END DESCRIPTION:
XS GIS Cut Line= 6
      3117373.85     13900219.76      3118427.95     13899209.84
      3118491.07       13898768.      3118522.63     13898591.27
      3118207.03     13897786.49      3117546.91     13896894.11
#Sta/Elev= 30
  3006.2    75.7  3296.2    74.1  3326.2    75.1  3356.2    72.5  3436.2    73.9
  4136.2    72.2  4436.2    72.7    4496    74.3    4696    71.7  4912.3      72
  4942.3    73.8  4978.7   72.44  4993.8   61.16  5000.6   61.15    5008   62.18
  5020.6   72.41  5221.9      72  5341.9    73.5  5631.9    72.2  5901.9    74.4
  6036.3    73.8  6066.3    72.4  6086.3    73.5  6266.3    72.5  6716.3    74.3
  6736.3      73  6786.3    74.9  6816.3    73.7  6936.3    73.7  7066.3    75.1
#Mann= 4 , 1 , 0
  3006.2      .2       0  3006.2      .1       0  4978.7     .04       0
  5020.6      .1       0
#XS Ineff= 2 , 0
       0    4080    73.3    5900       0    74.5
Permanent Ineff=
       F       F
Bank Sta=4978.7,5020.6
XS Rating Curve= 0
Exp/Cntr=.3,.1

Type RM Length L Ch R = 1 ,10331.4 ,69.1,111.9,130.1
BEGIN DESCRIPTION:
Cross Section 10331.4-Interpolated
END DESCRIPTION:
XS GIS Cut Line= 6
      3118091.19     13901315.23      3118518.73     13900690.88
      3118781.57     13899921.16      3118837.89     13898860.44
       3118828.5     13898653.93      3118866.05     13896645.14
#Sta/Elev= 30
  2272.5    73.6  2402.5   73.05  2495.9   72.66  2692.5    71.6  2782.5    72.4
    3015   71.46  3089.2    71.1  3209.2      72  3259.2    71.3  3389.2      73
  3609.2      72  4202.5      72  4222.5    71.2  4944.7    73.2  4984.2   72.31
  4988.1   61.95  4998.1   61.53  5007.4   62.74  5008.6   65.86  5014.7    73.2
  5054.7    72.1  5251.5    71.7  5281.5    70.9  5461.5    73.1  5711.5    71.4
  5951.5    72.9  5991.5      72  6021.5    72.9  6191.5    71.2  7120.6      73
#Mann= 7 , 1 , 0
  2272.5      .1       0  2402.5     .07       0  2495.9     .12       0
    3015      .1       0  4984.2     .04       0  5014.7      .1       0
  7120.6      .2       0
#XS Ineff= 2 , 0
       0  3389.2      73    5942       0      73
Permanent Ineff=
       F       F
Bank Sta=4984.2,5014.7
XS Rating Curve= 0
Exp/Cntr=.5,.3

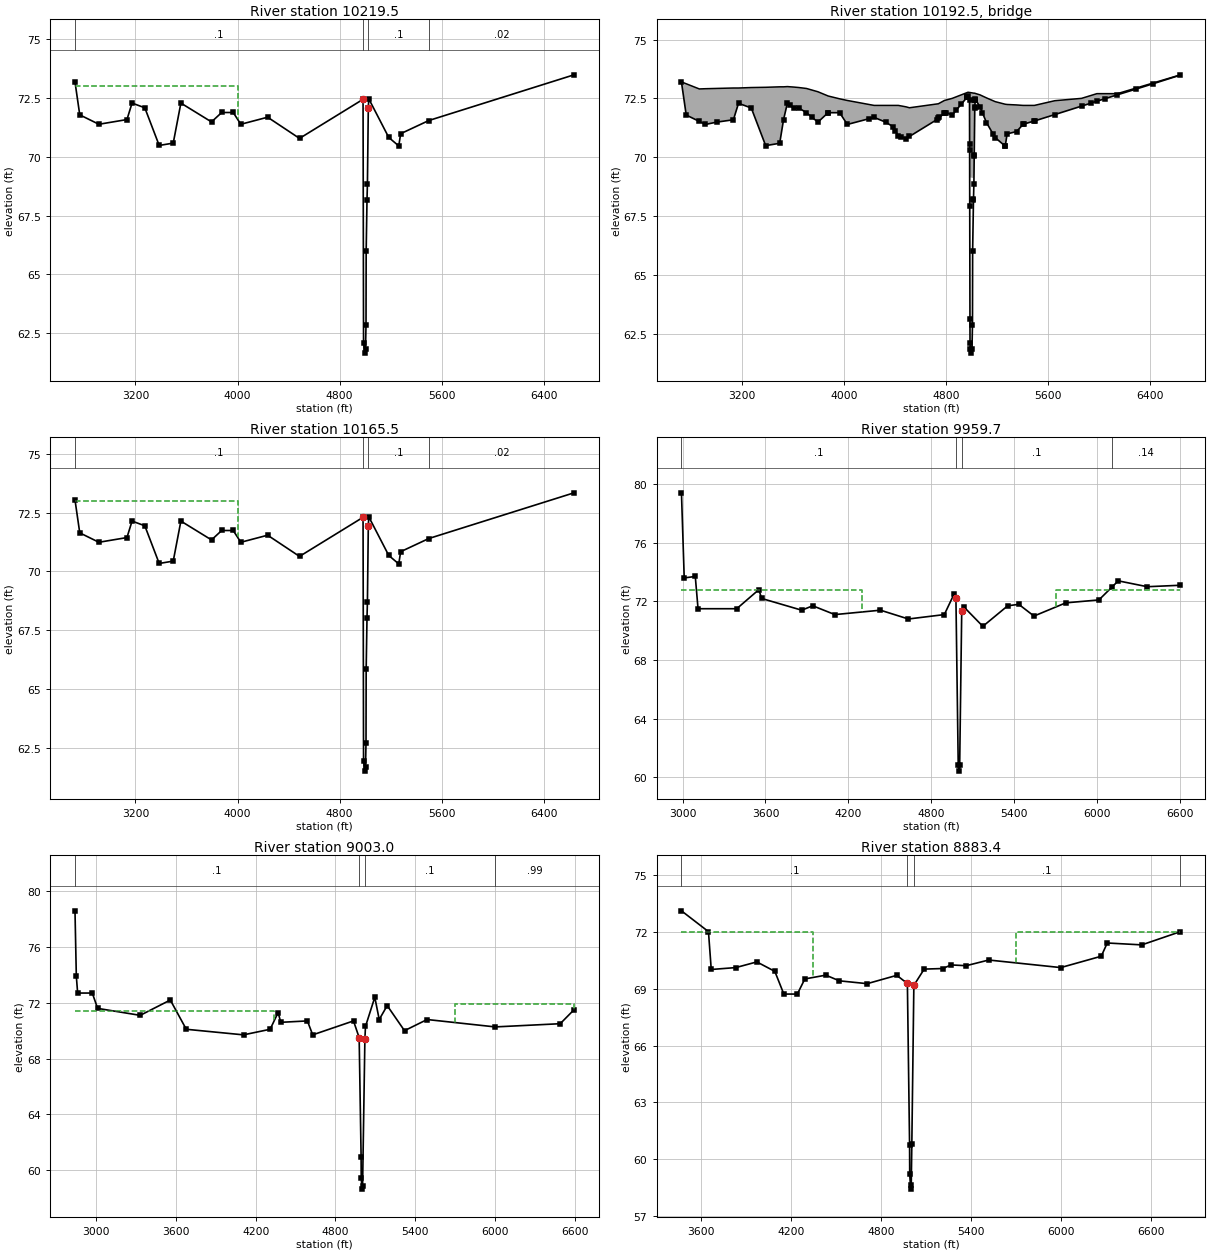
Type RM Length L Ch R = 1 ,10219.5 ,54,54,54
BEGIN DESCRIPTION:
Upstream Section of Bridge/Culvert/Weir
END DESCRIPTION:
XS GIS Cut Line= 6
      3118863.21     13901064.83      3118897.67     13899938.15
      3118921.12     13899265.96      3118960.76     13898400.12
      3119006.52     13897228.89      3119010.06     13897155.95
#Sta/Elev= 30
  2726.1   73.18  2763.4   71.78  2913.4   71.38  3133.4   71.58  3173.4   72.28
  3273.4   72.08  3386.2   70.48  3496.2   70.58  3556.2   72.28  3796.2   71.48
  3876.2   71.88  3966.2   71.88  4026.2   71.38  4236.2   71.68  4486.2   70.78
  4984.2   72.44  4988.1   62.08  4998.1   61.66  5003.5   61.84  5007.4   62.87
  5008.6   65.99  5015.2   68.18  5018.5   68.86  5025.4   72.09  5029.2   72.46
  5185.7   70.82  5264.2   70.46    5279   70.98    5500   71.54  6637.8   73.48
#Mann= 4 , 1 , 0
  2726.1      .1       0  4984.2     .04       0  5025.4      .1       0
    5500     .02       0
#XS Ineff= 2 , 0
       0    4000      73    5028       0    72.2
Permanent Ineff=
       F       F
Bank Sta=4984.2,5025.4
XS Rating Curve= 0
Exp/Cntr=.5,.3

Type RM Length L Ch R = 3 ,10192.5 ,,,
BEGIN DESCRIPTION:
REEVESTON ROAD
Structure ID: P38-05
END DESCRIPTION:
Bridge Culvert--1,0,-1,-1, 0
Deck Dist Width WeirC Skew NumUp NumDn MinLoCord MaxHiCord MaxSubmerge Is_Ogee
10,34,2.6,0, 47, 47, , , .95, 0, 1,1,,
  2726.1  2763.4  2866.1  2913.4  3133.4  3173.4  3273.4  3386.2  3496.2  3526.2
  3556.2  3606.2  3646.2  3706.2  3796.2  3876.2  3966.2  4026.2  4236.2  4386.2
  4426.2  4486.2  4513.3  4739.9  4787.5    4849  4972.2  4984.2    4985  4985.9
  5018.5 5020.99  5025.4  5029.2  5065.8  5117.1  5185.7  5264.2    5279  5353.5
  5403.5  5492.7  5652.7  5862.7  5982.7  6142.7  6637.8
    73.2   73.12    72.9   72.91   72.94   72.94   72.96   72.97   72.99   72.99
      73   72.98   72.96   72.92   72.78    72.6   72.48   72.41    72.2    72.2
    72.2   72.14    72.1   72.27   72.41    72.5   72.76   72.75   72.75   72.75
   72.72   72.72   72.72   72.71   72.65   72.52   72.36   72.25   72.24   72.22
    72.2    72.2    72.4    72.5    72.7    72.7    73.5
   73.19   71.79   71.52   71.39   71.59   72.29   72.09   70.49   70.59   71.59
   72.29   72.09   72.09   71.89   71.49   71.89   71.89   71.39   71.69   71.29
   70.89   70.79   70.88   71.66   71.86   71.79   72.59   72.45   70.31   69.14
   69.11   70.04    72.1   72.47   72.14   71.47   70.83   70.47   70.99   71.09
   71.39   71.54   71.81   72.17   72.38   72.65   73.49
  2726.1  2763.4  2866.1  2913.4  3133.4  3173.4  3273.4  3386.2  3496.2  3526.2
  3556.2  3606.2  3646.2  3706.2  3796.2  3876.2  3966.2  4026.2  4236.2  4386.2
  4426.2  4486.2  4513.3  4739.9  4787.5    4849  4972.2  4984.2    4985  4985.9
  5018.5 5020.99  5025.4  5029.2  5065.8  5117.1  5185.7  5264.2    5279  5353.5
  5403.5  5492.7  5652.7  5862.7  5982.7  6142.7  6637.8
    73.2   73.12    72.9   72.91   72.94   72.94   72.96   72.97   72.99   72.99
      73   72.98   72.96   72.92   72.78    72.6   72.48   72.41    72.2    72.2
    72.2   72.14    72.1   72.27   72.41    72.5   72.76   72.75   72.75   72.75
   72.72   72.72   72.72   72.71   72.65   72.52   72.36   72.25   72.24   72.22
    72.2    72.2    72.4    72.5    72.7    72.7    73.5
   73.09   71.69   71.42   71.29   71.49   72.19   71.99   70.39   70.49   71.49
   72.19   71.99   71.99   71.79   71.39   71.79   71.79   71.29   71.59   71.19
   70.79   70.69   70.78   71.56   71.76   71.69   72.49   72.35   70.21   69.04
   69.01   69.94      72   72.37   72.04   71.37   70.73   70.37   70.89   70.99
   71.29   71.44   71.71   72.07   72.28   72.55   73.39
Abutment Skew #Up #Dn= , 2 , 2
  4984.8  4985.9
   70.31   67.91
  4984.8  4985.9
   70.21   67.81
Abutment Skew #Up #Dn= , 2 , 2
  5015.3 5021.19
   68.21   70.04
  5015.3 5021.19
   68.11   69.94
BR Coef= 1 , 1 , 0 ,1.25, 0 ,,,.8,0,2,0,
WSPro=,,,, 1 ,,,, 0 ,,,, 0 ,,,,-1 ,-1 ,-1 , 0 , 0 , 0 , 0 , 0
BR U #Sta/Elev= 89
  2726.1   73.19  2763.4   71.79  2866.1   71.52  2913.4   71.39  3003.4   71.49
  3133.4   71.59  3173.4   72.29  3273.4   72.09  3386.2   70.49  3496.2   70.59
  3526.2   71.59  3556.2   72.29  3575.6   72.21  3606.2   72.09  3646.2   72.09
  3706.2   71.89  3745.6   71.71  3796.2   71.49  3873.3   71.88  3876.2   71.89
  3966.2   71.89  4026.2   71.39  4193.3   71.63  4236.2   71.69  4326.2   71.49
  4386.2   71.29  4403.3   71.12  4426.2   70.89  4443.3   70.86  4486.2   70.79
  4513.3   70.88  4726.3   71.59  4739.9   71.66  4747.1   71.69  4787.5   71.86
  4793.5   71.87  4802.1   71.89    4849   71.79  4881.9   72.01  4917.6   72.24
  4964.1   72.54 4967.69   72.56  4967.8   72.56 4967.91   72.56  4972.2   72.59
  4984.2   72.45 4984.91   70.55    4985   70.31  4985.9   67.91  4987.7    63.1
  4988.1   62.09  4991.4   61.83  4998.1   61.67  5003.5   61.85  5007.4   62.88
  5008.6      66  5015.2   68.19  5015.3   68.21  5018.5   68.87 5020.99   70.04
  5021.1   70.09  5025.4    72.1  5025.6   72.12 5028.69   72.42  5028.8   72.43
 5028.91   72.44  5029.2   72.47  5065.8   72.14  5085.8   71.88  5117.1   71.47
  5170.2   70.97  5185.7   70.83  5261.4   70.48  5264.2   70.47    5279   70.99
  5353.5   71.09  5403.5   71.39  5412.7   71.41  5492.7   71.54    5500   71.55
  5652.7   71.81  5862.7   72.17  5932.7   72.29  5982.7   72.38  6042.7   72.48
  6142.7   72.65  6292.7    72.9  6422.7   73.12  6637.8   73.49
BR U #Mann= 4
  2726.1      .1  4984.2     .04  5025.4      .1    5500     .02
BR U Banks=4984.2,5025.4
BR D #Sta/Elev= 89
  2726.1   73.09  2763.4   71.69  2866.1   71.42  2913.4   71.29  3003.4   71.39
  3133.4   71.49  3173.4   72.19  3273.4   71.99  3386.2   70.39  3496.2   70.49
  3526.2   71.49  3556.2   72.19  3575.6   72.11  3606.2   71.99  3646.2   71.99
  3706.2   71.79  3745.6   71.61  3796.2   71.39  3873.3   71.78  3876.2   71.79
  3966.2   71.79  4026.2   71.29  4193.3   71.53  4236.2   71.59  4326.2   71.39
  4386.2   71.19  4403.3   71.02  4426.2   70.79  4443.3   70.76  4486.2   70.69
  4513.3   70.78  4726.3   71.49  4739.9   71.56  4747.1   71.59  4787.5   71.76
  4793.5   71.77  4802.1   71.79    4849   71.69  4881.9   71.91  4917.6   72.14
  4964.1   72.44 4967.69   72.46  4967.8   72.46 4967.91   72.46  4972.2   72.49
  4984.2   72.35 4984.91   70.45    4985   70.21  4985.9   67.81  4987.7      63
  4988.1   61.99  4991.4   61.73  4998.1   61.57  5003.5   61.75  5007.4   62.78
  5008.6    65.9  5015.2   68.09  5015.3   68.11  5018.5   68.77 5020.99   69.94
  5021.1   69.99  5025.4      72  5025.6   72.02 5028.69   72.32  5028.8   72.33
 5028.91   72.34  5029.2   72.37  5065.8   72.04  5085.8   71.78  5117.1   71.37
  5170.2   70.87  5185.7   70.73  5261.4   70.38  5264.2   70.37    5279   70.89
  5353.5   70.99  5403.5   71.29  5412.7   71.31  5492.7   71.44    5500   71.45
  5652.7   71.71  5862.7   72.07  5932.7   72.19  5982.7   72.28  6042.7   72.38
  6142.7   72.55  6292.7    72.8  6422.7   73.02  6637.8   73.39
BR D #Mann= 4
  2726.1      .1  4984.2     .04  5025.4      .1    5500     .02
BR D Banks=4984.2,5025.4
BC Design=,, 0 ,, 0 ,,,,,,

Type RM Length L Ch R = 1 ,10165.5 ,205.8,205.8,205.8
BEGIN DESCRIPTION:
Downstream Section of Bridge/Culvert/Weir
END DESCRIPTION:
XS GIS Cut Line= 6
      3118915.79     13901077.14      3118950.25     13899950.45
       3118973.7     13899278.26      3119013.34     13898412.42
       3119059.1     13897241.19      3119062.64     13897168.26
#Sta/Elev= 30
  2726.1   73.04  2763.4   71.64  2913.4   71.24  3133.4   71.44  3173.4   72.14
  3273.4   71.94  3386.2   70.34  3496.2   70.44  3556.2   72.14  3796.2   71.34
  3876.2   71.74  3966.2   71.74  4026.2   71.24  4236.2   71.54  4486.2   70.64
  4984.2    72.3  4988.1   61.94  4998.1   61.52  5003.5    61.7  5007.4   62.73
  5008.6   65.85  5015.2   68.04  5018.5   68.72  5025.4   71.95  5029.2   72.32
  5185.7   70.68  5264.2   70.32    5279   70.84    5500    71.4  6637.8   73.34
#Mann= 4 , 1 , 0
  2726.1      .1       0  4984.2     .04       0  5025.4      .1       0
    5500     .02       0
#XS Ineff= 2 , 0
       0    4000      73    5028       0    71.7
Permanent Ineff=
       F       F
Bank Sta=4984.2,5025.4
XS Rating Curve= 0
Exp/Cntr=.5,.3

Type RM Length L Ch R = 1 ,9959.7  ,992.5,956.7,950.3
BEGIN DESCRIPTION:
Cross Section 9959.7
END DESCRIPTION:
XS GIS Cut Line= 5
      3119016.81      13900850.9      3119087.67     13899380.53
      3119212.19     13898764.17      3119125.03     13897677.76
      3119101.74      13897258.4
#Sta/Elev= 30
    2992    79.4    3012    73.6    3092    73.7    3112    71.5    3392    71.5
    3552    72.8    3572    72.2    3862    71.4    3942    71.7    4102    71.1
    4432    71.4    4634    70.8    4894    71.1  4963.6   72.48    4978   72.25
  4994.7   60.85  5003.4   60.43  5005.2   60.87    5020   71.35  5036.8   71.61
  5172.8    70.3  5352.8    71.7  5432.8    71.8  5542.8      71  5772.8    71.9
  6012.8    72.1  6105.2   72.96  6152.8    73.4  6362.8      73  6602.8    73.1
#Mann= 4 , 1 , 0
    2992      .1       0    4978     .04       0    5020      .1       0
  6105.2     .14       0
#XS Ineff= 2 , 0
       0    4300    72.8    5700       0    72.8
Permanent Ineff=
       F       F
Bank Sta=4978,5020
XS Rating Curve= 0
Exp/Cntr=.3,.1

Type RM Length L Ch R = 1 ,9003.0  ,188.2,119.6,92.1
BEGIN DESCRIPTION:
Cross Section 9003.0-Interpolated
END DESCRIPTION:
XS GIS Cut Line= 5
      3119830.84      13901224.2      3119954.92     13900559.46
      3120076.95     13899198.37      3120161.43     13898991.86
      3120123.89     13897508.73
#Sta/Elev= 30
  2842.7    78.6  2852.7    73.9  2862.7    72.7  2972.7    72.7  3012.7    71.6
  3332.7    71.1  3558.9    72.2  3678.9    70.1  4108.9    69.7  4308.9    70.1
  4368.9    71.3  4388.9    70.6  4588.9    70.7  4628.9    69.7  4935.4    70.7
  4977.9    69.5  4992.5   60.96  4993.4   59.42  4999.7   58.63  5003.6   58.85
    5021    69.4  5025.4    70.3  5095.4    72.4  5128.6    70.8  5188.6    71.8
  5318.6      70  5488.6    70.8    6000   70.27  6488.6    70.5  6592.2    71.5
#Mann= 4 , 1 , 0
  2842.7      .1       0  4977.9     .04       0    5021      .1       0
    6000     .99       0
#XS Ineff= 2 , 0
       0  4338.9    71.4    5700       0    71.9
Permanent Ineff=
       F       F
Bank Sta=4977.9,5021
XS Rating Curve= 0
Exp/Cntr=.5,.3

Type RM Length L Ch R = 1 ,8883.4  ,54,54,54
BEGIN DESCRIPTION:
Upstream Section of Bridge/Culvert/Weir
END DESCRIPTION:
XS GIS Cut Line= 6
      3120170.97     13900645.96      3120214.28     13899582.92
      3120232.86     13899155.77      3120239.38      13899030.1
      3120295.56     13897794.73      3120309.61     13897323.01
#Sta/Elev= 30
  3472.1   73.12  3652.1   72.02  3670.6   70.02  3834.4   70.12  3974.4   70.42
  4094.4   69.92  4154.4   68.72  4244.4   68.72  4294.4   69.52  4434.4   69.72
  4524.4   69.42    4710   69.27    4907   69.71  4977.9   69.28  4992.5   60.74
  4993.4    59.2  4999.7   58.41  5003.6   58.63  5007.5   60.81    5021   69.18
  5089.8   70.04  5213.9   70.07  5268.7   70.26    5370   70.22    5520   70.52
    6000   70.12    6270   70.72    6310   71.42    6540   71.32  6797.9   72.02
#Mann= 4 , 1 , 0
  3472.1      .1       0  4977.9    .042       0    5021      .1       0
  6797.9      .2       0
#XS Ineff= 2 , 0
       0    4350      72    5700       0      72
Permanent Ineff=
       F       F
Bank Sta=4977.9,5021
XS Rating Curve= 0
Exp/Cntr=.5,.3