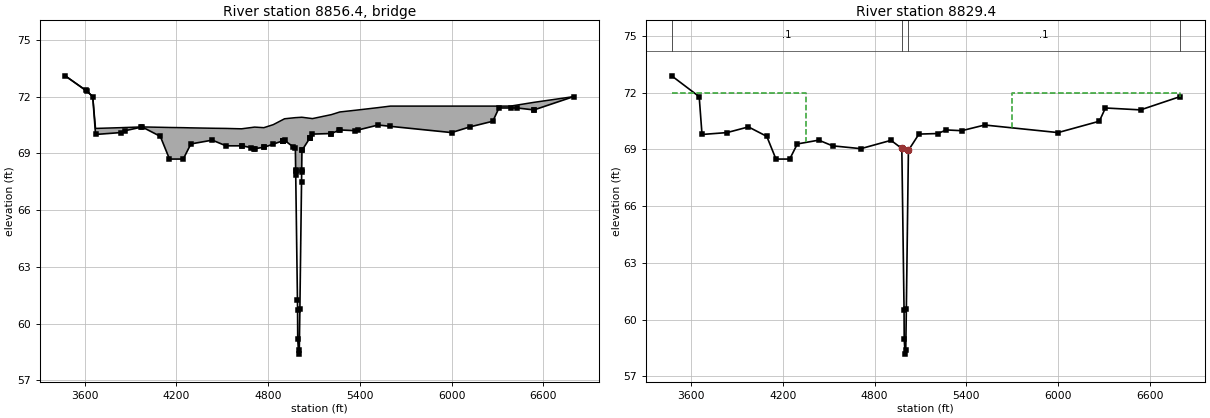
HEC-RAS study P138-00-00.prj: P138-00-00

--- P138-00-00.g01 (geometry) --- (continued)

Type RM Length L Ch R = 3 ,8856.4  ,,,
BEGIN DESCRIPTION:
CHRISMAN ROAD
Structure ID: P38-04
END DESCRIPTION:
Bridge Culvert--1,0,-1,-1, 0
Deck Dist Width WeirC Skew NumUp NumDn MinLoCord MaxHiCord MaxSubmerge Is_Ogee
10,34,2.6,0, 33, 33, , , .95, 0, 1,1,,
  3472.1  3612.1  3652.1  3670.6  3834.4  3974.4  4094.4  4154.4  4244.4  4294.4
  4434.4  4524.4    4626  4711.3  4771.5  4833.3    4907  4977.9  4979.9  5019.3
    5021  5089.8  5213.9  5268.7    5370    5520  5599.4    6000    6270    6310
    6386    6540  6797.9
    73.1   72.31   72.01   70.32   70.36    70.4   70.38   70.37   70.36   70.35
   70.33   70.32    70.3   70.39   70.36   70.52   70.83   70.89   70.89   70.91
   70.91   70.84   71.05   71.19   71.28   71.42    71.5    71.5    71.5    71.5
    71.5    71.7      72
    73.1    72.3      72      70    70.1    70.4    69.9    68.7    68.7    69.5
    69.7    69.4    69.4   69.25   69.32   69.49   69.69   69.26   68.09   68.11
   69.16   70.02   70.05   70.24    70.2    70.5   70.43    70.1    70.7    71.4
    71.4    71.3      72
  3472.1  3612.1  3652.1  3670.6  3834.4  3974.4  4094.4  4154.4  4244.4  4294.4
  4434.4  4524.4    4626  4711.3  4771.5  4833.3    4907  4977.9  4979.9  5019.3
    5021  5089.8  5213.9  5268.7    5370    5520  5599.4    6000    6270    6310
    6386    6540  6797.9
    73.1   72.31   72.01   70.32   70.36    70.4   70.38   70.37   70.36   70.35
   70.33   70.32    70.3   70.39   70.36   70.52   70.83   70.89   70.89   70.91
   70.91   70.84   71.05   71.19   71.28   71.42    71.5    71.5    71.5    71.5
    71.5    71.7      72
   72.91   72.11   71.81   69.81   69.91   70.21   69.71   68.51   68.51   69.31
   69.51   69.21   69.21   69.06   69.13    69.3    69.5   69.07    67.9   67.92
   68.97   69.83   69.86   70.05   70.01   70.31   70.24   69.91   70.51   71.21
   71.21   71.11   71.81
Abutment Skew #Up #Dn= , 2 , 2
  5018.3 5019.39
   67.49   68.11
  5018.3 5019.39
    67.3   67.92
BR Coef= 1 , 1 , 0 ,1.25, 0 ,,,.8,0,2,0,
WSPro=,,,, 1 ,,,, 0 ,,,, 0 ,,,,-1 ,-1 ,-1 , 0 , 0 , 0 , 0 , 0
BR U #Sta/Elev= 65
  3472.1    73.1  3606.1   72.33  3612.1    72.3  3652.1      72  3670.6      70
  3834.4    70.1  3864.4    70.2  3966.1   70.38  3974.4    70.4  4094.4    69.9
  4154.4    68.7  4244.4    68.7  4294.4    69.5  4434.4    69.7  4524.4    69.4
    4626    69.4  4629.7    69.4  4689.7    69.3    4710   69.25  4711.3   69.25
  4769.8   69.32  4771.5   69.32  4833.3   69.49  4894.2   69.66 4898.49   69.67
  4898.6   69.67 4898.71   69.67    4907   69.69  4964.6   69.34  4977.9   69.26
 4979.81   68.14  4979.9   68.09  4980.3   67.86  4991.6   61.25  4992.5   60.72
  4993.4   59.18  4999.7   58.39  5003.6   58.61  5007.5   60.79  5018.3   67.49
 5019.19   68.04  5019.3   68.11    5021   69.16  5022.8   69.18 5073.49   69.82
  5073.6   69.82 5073.71   69.82  5089.8   70.02  5212.7   70.05  5213.9   70.05
  5265.4   70.23  5268.7   70.24    5370    70.2  5389.4   70.24    5520    70.5
  5599.4   70.43    6000    70.1    6120    70.4    6270    70.7    6310    71.4
    6386    71.4    6430    71.4    6536    71.3    6540    71.3  6797.9      72
BR U #Mann= 4
  3472.1      .1  4977.9    .042    5021      .1  6797.9      .2
BR U Banks=4977.9,5021
BR D #Sta/Elev= 65
  3472.1   72.91  3606.1   72.14  3612.1   72.11  3652.1   71.81  3670.6   69.81
  3834.4   69.91  3864.4   70.01  3966.1   70.19  3974.4   70.21  4094.4   69.71
  4154.4   68.51  4244.4   68.51  4294.4   69.31  4434.4   69.51  4524.4   69.21
    4626   69.21  4629.7   69.21  4689.7   69.11    4710   69.06  4711.3   69.06
  4769.8   69.13  4771.5   69.13  4833.3    69.3  4894.2   69.47 4898.49   69.48
  4898.6   69.48 4898.71   69.48    4907    69.5  4964.6   69.15  4977.9   69.07
 4979.81   67.95  4979.9    67.9  4980.3   67.67  4991.6   61.06  4992.5   60.53
  4993.4   58.99  4999.7    58.2  5003.6   58.42  5007.5    60.6  5018.3    67.3
 5019.19   67.85  5019.3   67.92    5021   68.97  5022.8   68.99 5073.49   69.63
  5073.6   69.63 5073.71   69.63  5089.8   69.83  5212.7   69.86  5213.9   69.86
  5265.4   70.04  5268.7   70.05    5370   70.01  5389.4   70.05    5520   70.31
  5599.4   70.24    6000   69.91    6120   70.21    6270   70.51    6310   71.21
    6386   71.21    6430   71.21    6536   71.11    6540   71.11  6797.9   71.81
BR D #Mann= 4
  3472.1      .1  4977.9    .042    5021      .1  6797.9      .2
BR D Banks=4977.9,5021
BC Design=,, 0 ,, 0 ,,,,,,

Type RM Length L Ch R = 1 ,8829.4  ,262.6,262.6,262.6
BEGIN DESCRIPTION:
Downstream Section of Bridge/Culvert/Weir
END DESCRIPTION:
XS GIS Cut Line= 6
       3120222.9     13900660.75      3120266.22      13899597.7
       3120284.8     13899170.55      3120291.32     13899044.88
       3120347.5     13897809.51      3120361.55     13897337.79
#Sta/Elev= 30
  3472.1   72.89  3652.1   71.79  3670.6   69.79  3834.4   69.89  3974.4   70.19
  4094.4   69.69  4154.4   68.49  4244.4   68.49  4294.4   69.29  4434.4   69.49
  4524.4   69.19    4710   69.04    4907   69.48  4977.9   69.05  4992.5   60.51
  4993.4   58.97  4999.7   58.18  5003.6    58.4  5007.5   60.58    5021   68.95
  5089.8   69.81  5213.9   69.84  5268.7   70.03    5370   69.99    5520   70.29
    6000   69.89    6270   70.49    6310   71.19    6540   71.09  6797.9   71.79
#Mann= 4 , 1 , 0
  3472.1      .1       0  4977.9    .042       0    5021      .1       0
  6797.9      .2       0
#XS Ineff= 2 , 0
       0    4350      72    5700       0      72
Permanent Ineff=
       F       F
Bank Sta=4977.9,5021
XS Rating Curve= 0
Exp/Cntr=.5,.3