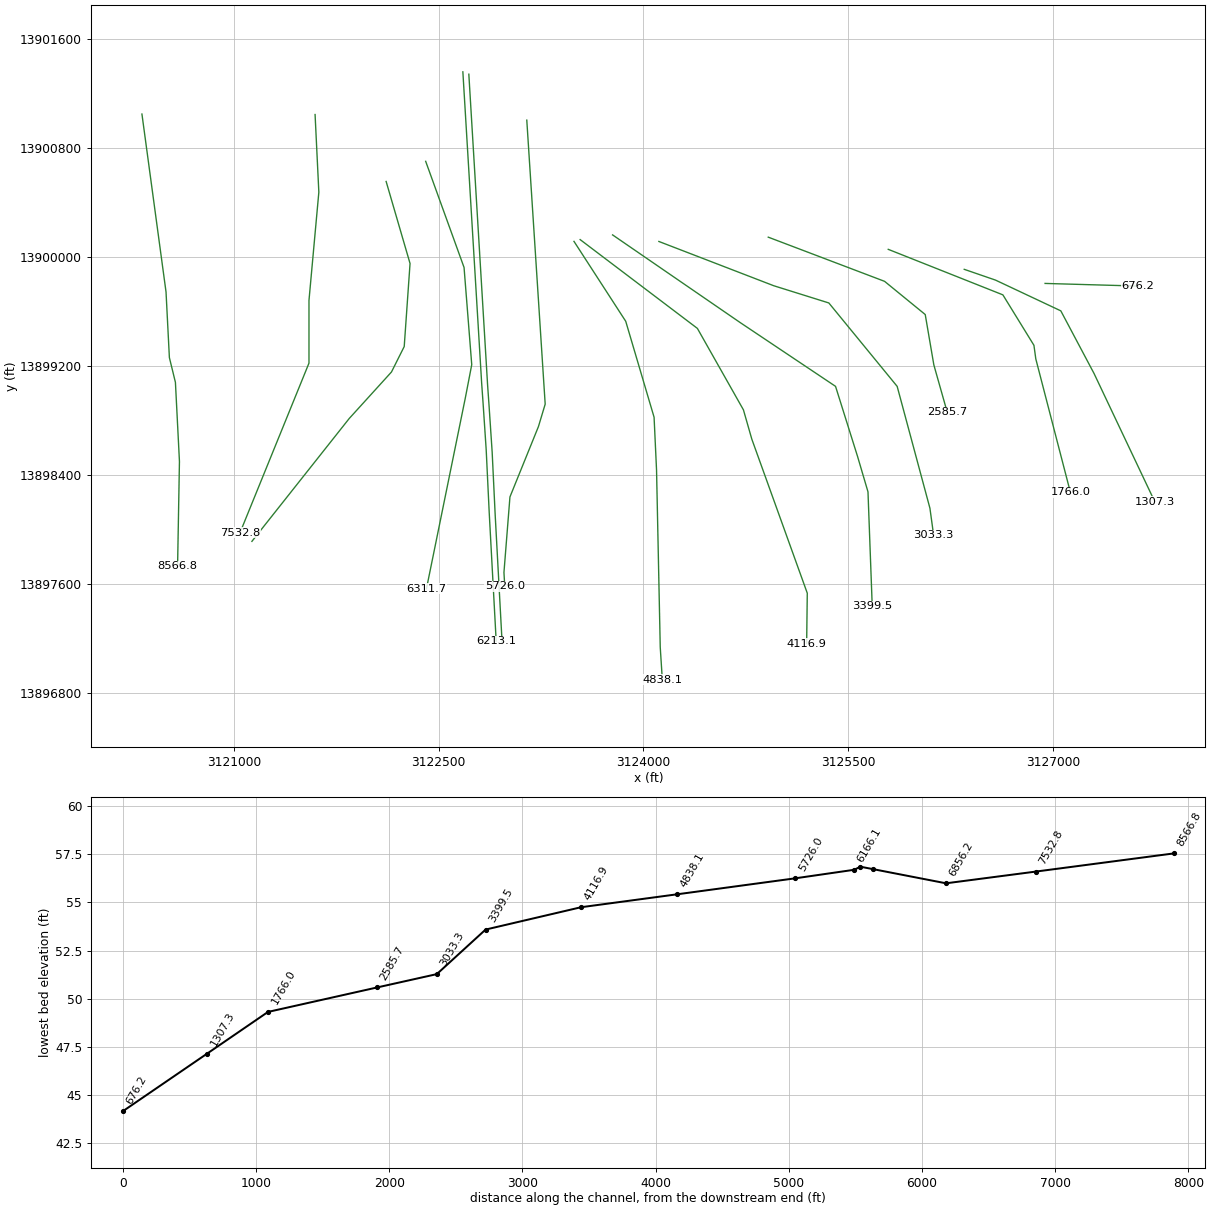
HEC-RAS study P138-00-00.prj: P138-00-00

--- P138-00-00.g01 (geometry) --- (continued)

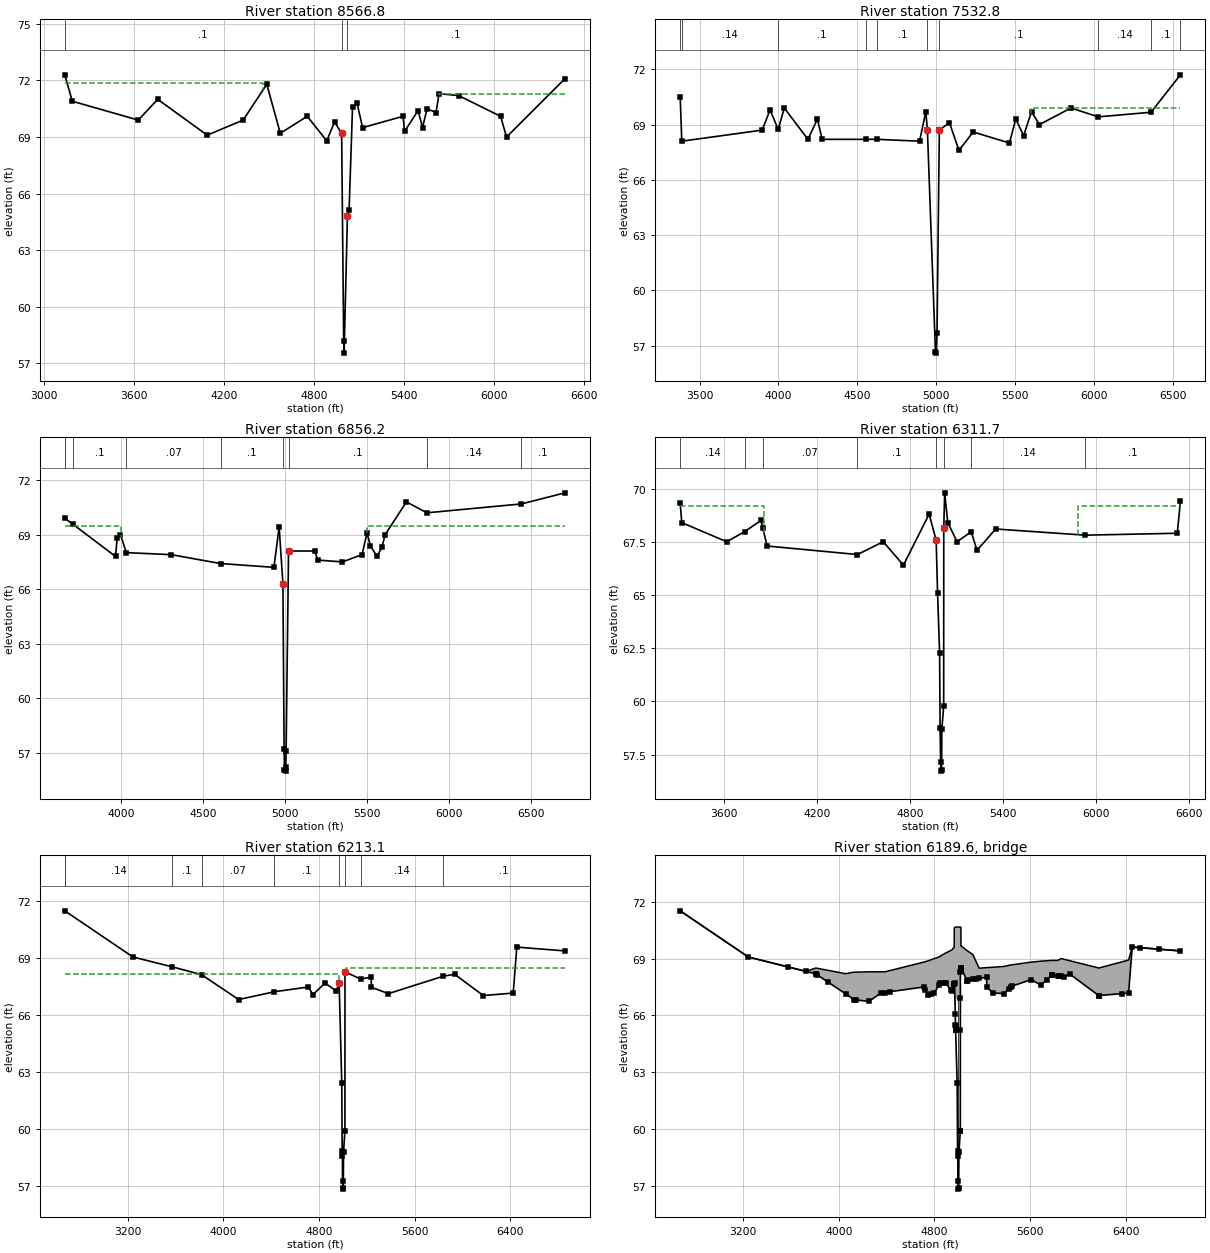
Type RM Length L Ch R = 1 ,8566.8  ,1102.5,1034,893.9
BEGIN DESCRIPTION:
Cross Section 8566.8
END DESCRIPTION:
XS GIS Cut Line= 6
      3120327.44     13901047.05      3120503.91     13899741.21
      3120528.48     13899259.65       3120572.7     13899077.84
      3120602.18       13898498.       3120588.5     13897728.12
#Sta/Elev= 30
  3136.6    72.3  3186.6    70.9  3626.6    69.9  3756.6      71  4086.6    69.1
  4326.6    69.9  4484.3    71.8  4574.3    69.2  4754.3    70.1  4884.3    68.8
  4936.5    69.8  4983.8   69.19  4997.4   58.17  5000.3   57.54  5022.4   64.81
  5033.4   65.11  5056.5    70.6  5086.5    70.8  5123.6    69.5  5393.6    70.1
  5403.6    69.3  5493.6    70.4  5523.6    69.5  5553.6    70.5  5613.6    70.3
  5633.6    71.3  5764.2    71.2  6044.2    70.1  6084.2      69  6474.2    72.1
#Mann= 3 , 1 , 0
  3136.6      .1       0  4983.8     .04       0  5022.4      .1       0
#XS Ineff= 2 , 0
       0    4461   71.85    5632       0    71.3
Permanent Ineff=
       F       F
Bank Sta=4983.8,5022.4
XS Rating Curve= 0
Exp/Cntr=.3,.1

Type RM Length L Ch R = 1 ,7532.8  ,756.9,676.6,609.7
BEGIN DESCRIPTION:
Cross Section 7532.8-Interpolated
END DESCRIPTION:
XS GIS Cut Line= 5
      3121595.49     13901043.44      3121623.04     13900473.79
      3121550.83     13899679.47      3121550.83     13899219.12
      3121045.36     13897973.49
#Sta/Elev= 30
  3377.3    70.5  3387.3    68.1  3897.3    68.7  3947.3    69.8  3998.9   68.74
  4037.6    69.9  4187.6    68.2  4247.6    69.3  4277.6    68.2    4557    68.2
  4626.2    68.2  4895.2    68.1  4935.2    69.7  4945.2    68.7  4996.2   56.66
  5002.8    56.6  5006.1    57.7    5021   68.71  5085.2    69.1  5145.2    67.6
  5235.5    68.6  5465.5      68  5505.5    69.3  5555.5    68.4  5605.5    69.7
  5655.5      69  5855.5    69.9  6029.3   69.42  6363.5   69.67  6549.8    71.7
#Mann= 10 , 1 , 0
  3377.3      .2       0  3387.3     .14       0  3998.9      .1       0
    4557     .07       0  4626.2      .1       0  4945.2     .04       0
    5021      .1       0  6029.3     .14       0  6363.5      .1       0
  6549.8      .2       0
#XS Ineff= 2 , 0
       0  4037.6    69.9    5600       0    69.9
Permanent Ineff=
       F       F
Bank Sta=4945.2,5021
XS Rating Curve= 0
Exp/Cntr=.3,.1

Type RM Length L Ch R = 1 ,6856.2  ,459.9,544.5,662.5
BEGIN DESCRIPTION:
Cross Section 6856.2
END DESCRIPTION:
XS GIS Cut Line= 6
      3122115.86     13900552.26      3122290.99     13899950.26
      3122248.32     13899340.73      3122154.96       13899154.
      3121845.39     13898812.49      3121132.81     13897910.98
#Sta/Elev= 30
  3653.7    69.9  3700.9   69.59  3963.7    67.8  3973.7    68.8  3993.7      69
  4029.6   68.01  4302.7    67.9  4605.8   67.41  4931.6    67.2  4963.5   69.42
  4986.6   66.31  4993.9   57.23  4996.2   56.05  5002.8   55.99  5004.1   56.19
  5006.1   57.09    5021    68.1  5180.4    68.1  5200.4    67.6  5350.4    67.5
  5470.4    67.9  5500.4    69.1  5520.4    68.4  5561.4    67.8  5591.4    68.3
  5611.4      69  5741.4    70.8  5866.4    70.2  6444.5   70.69  6710.5    71.3
#Mann= 9 , 1 , 0
  3653.7      .2       0  3653.7     .14       0  3700.9      .1       0
  4029.6     .07       0  4605.8      .1       0  4986.6     .04       0
    5021      .1       0  5866.4     .14       0  6444.5      .1       0
#XS Ineff= 2 , 0
       0    4000    69.5    5500       0    69.5
Permanent Ineff=
       F       F
Bank Sta=4986.6,5021
XS Rating Curve= 0
Exp/Cntr=.3,.1

Type RM Length L Ch R = 1 ,6311.7  ,66.7,98.6,228.2
BEGIN DESCRIPTION:
Cross Section 6311.7-Interpolated
END DESCRIPTION:
XS GIS Cut Line= 5
      3122405.47     13900700.01       3122686.5     13899921.16
      3122742.82     13899207.75      3122695.89      13898963.7
      3122410.89     13897562.44
#Sta/Elev= 30
  3320.1    69.3  3330.1    68.4  3620.1    67.5  3735.9   67.98  3840.1    68.5
  3851.7   68.15  3880.1    67.3  4461.6    66.9  4628.1    67.5  4758.1    66.4
  4923.7    68.8 4968.97   67.57 4977.98   65.08 4990.99   62.29 4994.36   58.74
 4997.54   57.15 5001.36   56.72 5003.73   56.79 5005.73   58.69 5017.38   59.79
 5017.93   68.16  5023.7    69.8  5043.7    68.4  5103.7    67.5  5194.3   67.97
  5232.2    67.1  5352.2    68.1  5929.6   67.81  6522.2    67.9  6542.2    69.4
#Mann= 8 , 1 , 0
  3320.1     .14       0  3735.9      .1       0  3851.7     .07       0
  4461.6      .1       0 4968.97     .04       0 5017.93      .1       0
  5194.3     .14       0  5929.6      .1       0
#XS Ineff= 2 , 0
       0    3860    69.2    5880       0    69.2
Permanent Ineff=
       F       F
Bank Sta=4968.97,5017.93
XS Rating Curve= 0
Exp/Cntr=.5,.3

Type RM Length L Ch R = 1 ,6213.1  ,47,47,47
BEGIN DESCRIPTION:
Upstream Section of Bridge/Culvert/Weir
END DESCRIPTION:
XS GIS Cut Line= 6
       3122677.8     13901356.78      3122815.28     13899074.68
      3122825.99       13898923.      3122848.66     13898582.88
      3122870.92     13898119.32      3122921.87      13897178.6
#Sta/Elev= 30
  2673.5    71.5  3243.5   69.07  3573.1   68.55  3817.6   68.14  4127.9   66.83
  4427.1   67.24  4711.5   67.49 4749.75   67.09 4851.49    67.7 4944.31   67.28
 4968.97    67.7 4990.99   62.42 4994.36   58.87 4996.27    58.6 4997.54   57.28
 5001.36   56.85 5003.73   56.92 5005.73   58.82 5017.38   59.92 5017.93   68.29
    5148   67.91 5237.78   68.01 5238.24   67.48  5380.7   67.14    5841   68.06
  5935.5   68.16  6175.5   67.04  6425.5   67.17  6455.5   69.59  6858.9   69.39
#Mann= 9 , 1 , 0
  2673.5      .2       0  2673.5     .14       0  3573.1      .1       0
  3817.6     .07       0  4427.1      .1       0 4968.97     .04       0
 5017.93      .1       0    5148     .14       0    5841      .1       0
#XS Ineff= 2 , 0
       0    4967    68.2    5028       0   68.47
Permanent Ineff=
       F       F
Bank Sta=4968.97,5017.93
XS Rating Curve= 0
Exp/Cntr=.5,.3

Type RM Length L Ch R = 3 ,6189.6  ,,,
BEGIN DESCRIPTION:
ALDINE WESTFIELD, SKEW ANGLE OF 25 DEGREES
Structure ID: P38-02
END DESCRIPTION:
Bridge Culvert--1,0,-1,-1, 0
Deck Dist Width WeirC Skew NumUp NumDn MinLoCord MaxHiCord MaxSubmerge Is_Ogee
10,27,2.6,0, 46, 46, , , .95, 0, 1,1,,
  2673.5  3243.5  3727.9  3807.9  4057.6  4127.9  4252.3  4352.3  4387.6  4711.5
 4749.75 4795.98  4838.9 4851.49 4894.08 4944.31 4966.29  4966.4 4968.97 4976.98
 4977.07 5017.73 5017.84 5017.93  5022.6 5022.71 5026.48 5070.89    5122  5175.2
 5237.78 5238.24  5290.7  5380.7  5440.7  5610.7  5690.7  5780.7  5832.7  5862.7
  5885.5  5935.5  6176.8  6425.5  6455.5  6858.9
   71.51   69.08   68.32    68.5    68.2   68.28    68.3    68.3    68.3   68.81
   68.88   68.99   69.08   69.13   69.29   69.44    69.6    70.6   70.62   70.66
   70.66   70.65   70.65   70.65   70.65   69.65   69.65   69.43   69.21   68.49
   68.52   68.52   68.54   68.58   68.66   68.81   68.86    68.9    68.9      69
   68.96   68.88    68.5   68.92   69.61    69.4
   71.51   69.08   68.32   68.19   67.14   66.84   66.74   67.18   67.21    67.5
    67.1   67.17   67.59   67.71   67.71   67.29   67.66   67.67   67.71    65.5
   66.86   66.85   66.93    68.3   68.41   68.41    68.5   67.84    67.9   67.95
   68.02   67.49   67.19   67.15   67.52   67.89    67.6   68.11   68.08   68.06
   68.04   68.17   67.05   67.18    69.6    69.4
  2673.5  3243.5  3727.9  3807.9  4057.6  4127.9  4252.3  4352.3  4387.6  4711.5
 4749.75 4795.98  4838.9 4851.49 4894.08 4944.31 4966.29  4966.4 4968.97 4976.98
 4977.07 5017.73 5017.84 5017.93  5022.6 5022.71 5026.48 5070.89    5122  5175.2
 5237.78 5238.24  5290.7  5380.7  5440.7  5610.7  5690.7  5780.7  5832.7  5862.7
  5885.5  5935.5  6176.8  6425.5  6455.5  6858.9
   71.51   69.08   68.32    68.5    68.2   68.28    68.3    68.3    68.3   68.81
   68.88   68.99   69.08   69.13   69.29   69.44    69.6    70.6   70.62   70.66
   70.66   70.65   70.65   70.65   70.65   69.65   69.65   69.43   69.21   68.49
   68.52   68.52   68.54   68.58   68.66   68.81   68.86    68.9    68.9      69
   68.96   68.88    68.5   68.92   69.61    69.4
   71.35   68.92   68.16   68.03   66.98   66.68   66.58   67.02   67.05   67.34
   66.94   67.01   67.43   67.55   67.55   67.13    67.5   67.51   67.55   65.34
    66.7   66.69   66.77   68.14   68.25   68.25   68.34   67.68   67.74   67.79
   67.86   67.33   67.03   66.99   67.36   67.73   67.44   67.95   67.92    67.9
   67.88   68.01   66.89   67.02   69.44   69.24
Pier Skew, UpSta & Num, DnSta & Num=  ,4996.3, 2 ,4996.3, 2 , 0 , 0 , 0 ,,
       1       1
   57.09   67.86
       1       1
   56.93    67.7
Abutment Skew #Up #Dn= , 2 , 2
 4976.87 4977.98
   66.86   65.22
 4976.87 4977.98
    66.7   65.06
BR Coef= 1 , 1 , 0 ,1.25, 0 ,,,.8,0,2,0,
WSPro=,,,, 1 ,,,, 0 ,,,, 0 ,,,,-1 ,-1 ,-1 , 0 , 0 , 0 , 0 , 0
BR U #Sta/Elev= 83
  2673.5   71.51  3243.5   69.08  3573.1   68.56  3727.9   68.32  3807.6   68.19
  3807.9   68.19  3817.6   68.15  3907.6   67.77  4057.6   67.14  4127.9   66.84
  4147.6   66.82  4252.3   66.74  4352.3   67.18  4387.6   67.21  4427.1   67.25
  4711.5    67.5  4725.6   67.35 4749.75    67.1    4775   67.14 4795.98   67.17
  4838.9   67.59 4851.49   67.71  4883.5   67.71 4894.08   67.71  4939.4   67.33
 4944.31   67.29 4966.29   67.66  4966.4   67.67 4966.51   67.67 4968.97   67.71
  4974.8    66.1 4976.98    65.5 4977.07   65.47 4977.88   65.25 4977.98   65.22
 4990.99   62.43 4994.36   58.88 4996.27   58.61 4997.54   57.29 5001.36   56.86
 5003.73   56.93 5005.73   58.83 5017.28   59.92 5017.38   59.93 5017.73   65.26
 5017.84   66.93 5017.93    68.3 5022.49   68.41  5022.6   68.41 5022.71   68.41
 5026.48    68.5    5027   68.49 5070.89   67.84 5070.98   67.84  5078.3   67.85
    5122    67.9    5148   67.92  5175.2   67.95 5237.78   68.02 5238.24   67.49
  5290.7   67.19  5380.7   67.15  5421.8    67.4  5440.7   67.52  5452.7   67.55
  5610.7   67.89  5690.7    67.6  5742.7   67.89  5780.7   68.11  5782.7   68.11
  5832.7   68.08    5841   68.07  5862.7   68.06  5885.5   68.04  5935.5   68.17
  6175.5   67.05  6176.8   67.05  6366.8   67.15  6425.5   67.18  6455.5    69.6
  6516.8   69.57  6676.8   69.49  6858.9    69.4
BR U #Mann= 9
  2673.5      .2  2673.5     .14  3573.1      .1  3817.6     .07  4427.1      .1
 4968.97     .04 5017.93      .1    5148     .14    5841      .1
BR U Banks=4968.97,5017.93
BR D #Sta/Elev= 83
  2673.5   71.35  3243.5   68.92  3573.1    68.4  3727.9   68.16  3807.6   68.03
  3807.9   68.03  3817.6   67.99  3907.6   67.61  4057.6   66.98  4127.9   66.68
  4147.6   66.66  4252.3   66.58  4352.3   67.02  4387.6   67.05  4427.1   67.09
  4711.5   67.34  4725.6   67.19 4749.75   66.94    4775   66.98 4795.98   67.01
  4838.9   67.43 4851.49   67.55  4883.5   67.55 4894.08   67.55  4939.4   67.17
 4944.31   67.13 4966.29    67.5  4966.4   67.51 4966.51   67.51 4968.97   67.55
  4974.8   65.94 4976.98   65.34 4977.07   65.31 4977.88   65.09 4977.98   65.06
 4990.99   62.27 4994.36   58.72 4996.27   58.45 4997.54   57.13 5001.36    56.7
 5003.73   56.77 5005.73   58.67 5017.28   59.76 5017.38   59.77 5017.73    65.1
 5017.84   66.77 5017.93   68.14 5022.49   68.25  5022.6   68.25 5022.71   68.25
 5026.48   68.34    5027   68.33 5070.89   67.68 5070.98   67.68  5078.3   67.69
    5122   67.74    5148   67.76  5175.2   67.79 5237.78   67.86 5238.24   67.33
  5290.7   67.03  5380.7   66.99  5421.8   67.24  5440.7   67.36  5452.7   67.39
  5610.7   67.73  5690.7   67.44  5742.7   67.73  5780.7   67.95  5782.7   67.95
  5832.7   67.92    5841   67.91  5862.7    67.9  5885.5   67.88  5935.5   68.01
  6175.5   66.89  6176.8   66.89  6366.8   66.99  6425.5   67.02  6455.5   69.44
  6516.8   69.41  6676.8   69.33  6858.9   69.24
BR D #Mann= 9
  2673.5      .2  2673.5     .14  3573.1      .1  3817.6     .07  4427.1      .1
 4968.97     .04 5017.93      .1    5148     .14    5841      .1
BR D Banks=4968.97,5017.93
BC Design=,, 0 ,, 0 ,,,,,,

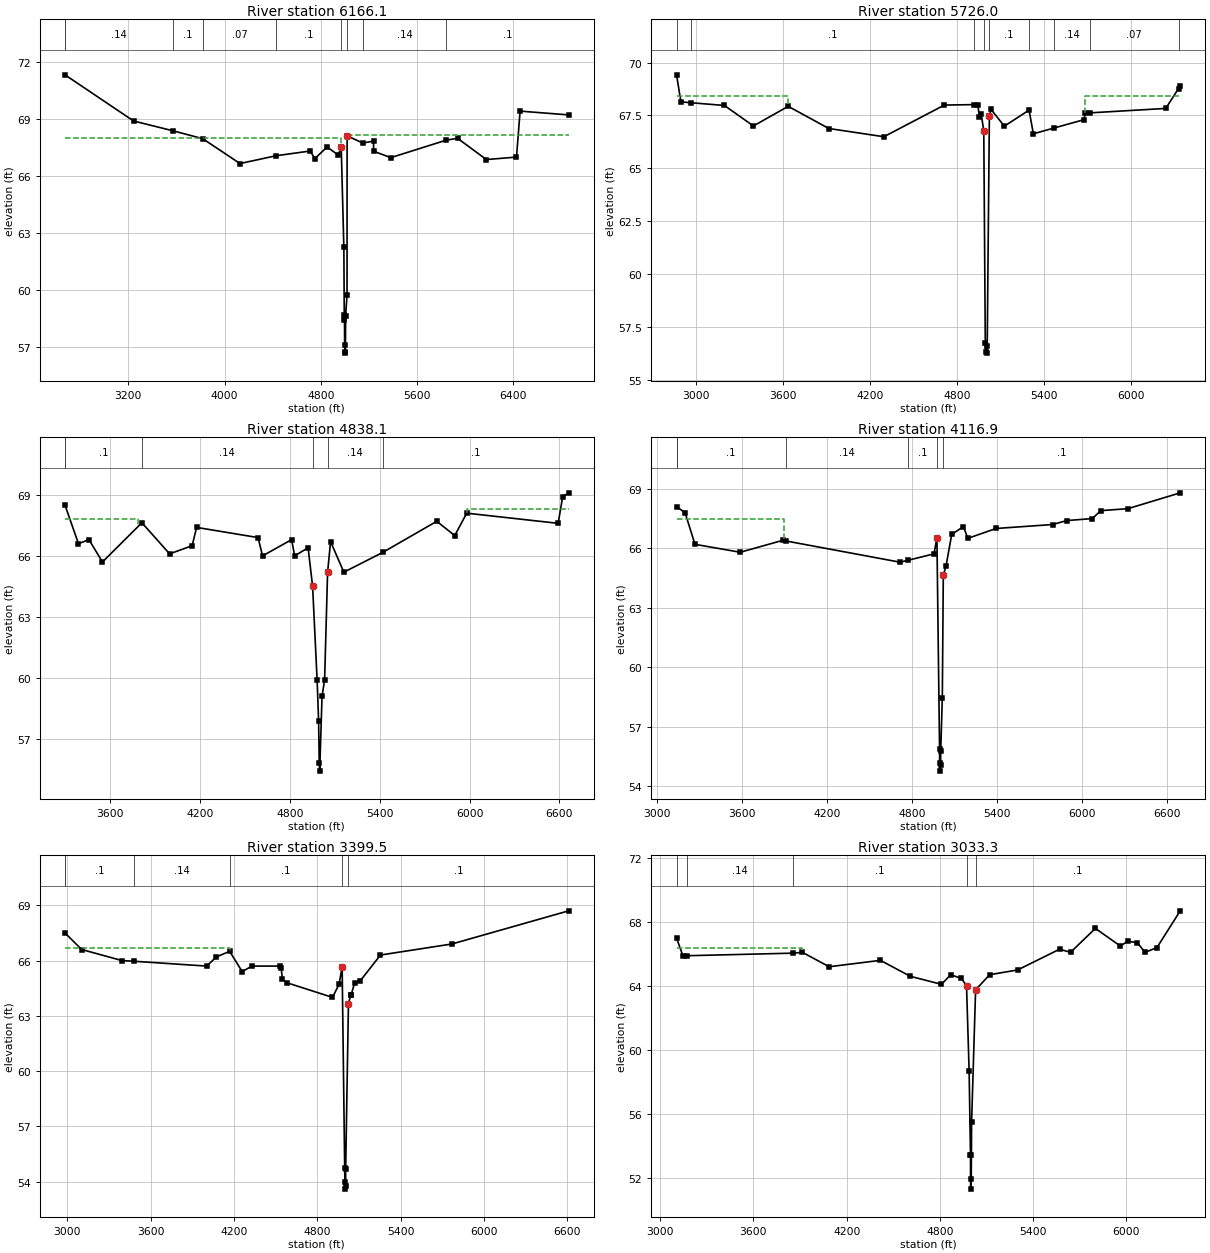
Type RM Length L Ch R = 1 ,6166.1  ,440.1,440.1,440.1
BEGIN DESCRIPTION:
Downstream Section of Bridge/Culvert/Weir
END DESCRIPTION:
XS GIS Cut Line= 6
      3122721.53     13901339.54        3122859.     13899057.44
      3122869.71     13898905.76      3122892.38     13898565.64
      3122914.64     13898102.08      3122965.59     13897161.36
#Sta/Elev= 30
  2673.5   71.34  3243.5   68.91  3573.1   68.39  3817.6   67.98  4127.9   66.67
  4427.1   67.08  4711.5   67.33 4749.75   66.93 4851.49   67.54 4944.31   67.12
 4968.97   67.54 4990.99   62.26 4994.36   58.71 4996.27   58.44 4997.54   57.12
 5001.36   56.69 5003.73   56.76 5005.73   58.66 5017.38   59.76 5017.93   68.13
    5148   67.75 5237.78   67.85 5238.24   67.32  5380.7   66.98    5841    67.9
  5935.5      68  6175.5   66.88  6425.5   67.01  6455.5   69.43  6858.9   69.23
#Mann= 9 , 1 , 0
  2673.5      .2       0  2673.5     .14       0  3573.1      .1       0
  3817.6     .07       0  4427.1      .1       0 4968.97     .04       0
 5017.93      .1       0    5148     .14       0    5841      .1       0
#XS Ineff= 2 , 0
       0    4967      68    5028       0   68.15
Permanent Ineff=
       F       F
Bank Sta=4968.97,5017.93
XS Rating Curve= 0
Exp/Cntr=.5,.3

Type RM Length L Ch R = 1 ,5726.0  ,802.4,887.9,1194.5
BEGIN DESCRIPTION:
Cross Section 5726.0
END DESCRIPTION:
XS GIS Cut Line= 6
      3123145.93     13901002.43      3123280.69       13898918.
      3123231.27     13898753.27      3123022.61     13898237.09
      3122978.68     13897682.48      3122984.64     13897582.67
#Sta/Elev= 30
  2863.9   69.42  2893.9   68.14    2962    68.1  3193.9   67.97  3393.9      67
  3633.9   67.93  3913.9   66.88  4293.9   66.49  4711.3   67.99  4914.3   68.01
  4941.3   68.01  4952.9   67.44  4965.2   67.57  4982.9   66.76  4993.4   56.75
  4995.2   56.28  5005.8   56.25  5006.7   56.59  5021.6   67.49  5033.2   67.78
  5124.9   66.99  5295.4   67.75  5324.9   66.63  5466.1    66.9  5674.9    67.3
  5681.7   67.61  5715.3   67.62    6238   67.83  6326.2   68.77    6338   68.91
#Mann= 9 , 1 , 0
  2863.9     .14       0    2962      .1       0  4914.3     .14       0
  4982.9     .04       0  5021.6      .1       0  5295.4     .07       0
  5466.1     .14       0  5715.3     .07       0  6326.2      .1       0
#XS Ineff= 2 , 0
       0    3633    68.4    5682       0    68.4
Permanent Ineff=
       F       F
Bank Sta=4982.9,5021.6
XS Rating Curve= 0
Exp/Cntr=.3,.1

Type RM Length L Ch R = 1 ,4838.1  ,536.6,721.2,1028.3
BEGIN DESCRIPTION:
Cross Section 4838.1-Interpolated
END DESCRIPTION:
XS GIS Cut Line= 6
       3123491.5     13900112.73       3123870.6     13899526.02
      3124078.21     13898821.97      3124096.26     13898433.83
      3124123.34     13897134.04       3124138.6      13896894.5
#Sta/Elev= 30
  3299.9    68.5  3389.9    66.6  3459.9    66.8  3549.9    65.7  3813.1   67.63
  3998.4    66.1  4148.4    66.5  4178.4    67.4  4588.4    66.9  4618.4      66
  4812.5    66.8  4832.5      66  4922.5    66.4  4952.5    64.5  4982.5    59.9
  4992.5    57.9  4996.7   55.81  4999.8   55.42  5015.4    59.1  5032.5    59.9
  5052.5    65.2  5072.5    66.7    5161    65.2  5420.3   66.17    5781    67.7
    5901      67    5981    68.1  6591.1    67.6  6621.1    68.9  6661.1    69.1
#Mann= 6 , 1 , 0
  3299.9      .2       0  3299.9      .1       0  3813.1     .14       0
  4952.5     .04       0  5052.5     .14       0  5420.3      .1       0
#XS Ineff= 2 , 0
       0    3788    67.8    5985       0    68.3
Permanent Ineff=
       F       F
Bank Sta=4952.5,5052.5
XS Rating Curve= 0
Exp/Cntr=.3,.1

Type RM Length L Ch R = 1 ,4116.9  ,459.3,717.4,811.9
BEGIN DESCRIPTION:
Cross Section 4116.9
END DESCRIPTION:
XS GIS Cut Line= 6
      3123536.72     13900125.62      3124395.27     13899474.04
      3124732.56     13898876.12      3124793.89     13898661.48
      3125200.17     13897530.79      3125195.54     13897160.84
#Sta/Elev= 28
  3137.6    68.1  3197.6    67.8  3267.6    66.2  3587.6    65.8  3887.6    66.4
  3910.2   66.37  4715.4    65.3  4770.5   65.39  4956.9   65.72  4977.3   66.53
  4995.9   55.89  4996.7   55.14  4999.8   54.75  5003.3   55.08  5004.1   55.75
  5015.4   58.43  5022.4   64.63  5042.3   65.13  5081.9    66.7  5165.1    67.1
  5195.1    66.5  5395.1      67  5795.1    67.2  5895.1    67.4  6075.1    67.5
  6135.1    67.9  6326.6      68  6696.6    68.8
#Mann= 6 , 1 , 0
  3137.6      .2       0  3137.6      .1       0  3910.2     .14       0
  4770.5      .1       0  4977.3     .04       0  5022.4      .1       0
#XS Ineff= 2 , 0
       0    3900    67.5               0
Permanent Ineff=
       F       F
Bank Sta=4977.3,5022.4
XS Rating Curve= 0
Exp/Cntr=.3,.1

Type RM Length L Ch R = 1 ,3399.5  ,570.2,366.2,361.3
BEGIN DESCRIPTION:
Cross Section 3399.5
END DESCRIPTION:
XS GIS Cut Line= 6
      3123774.35     13900160.12      3124709.56      13899516.2
      3125407.14      13899048.6      3125568.12       13898535.
      3125644.78     13898274.36      3125675.87     13897434.87
#Sta/Elev= 29
  2983.2    67.5  3103.2    66.6  3393.2      66  3483.3   65.96  4003.2    65.7
  4073.2    66.2  4168.5    66.5  4258.7    65.4  4328.7    65.7  4528.7    65.7
  4538.7    65.6  4548.7      65  4578.7    64.8  4908.7      64  4956.1   64.71
  4978.1   65.66  4996.5   54.73    4998   53.98  5001.3   53.59  5003.3   53.78
  5003.5   54.68  5023.5   63.63  5039.6   64.14  5042.7   64.13  5068.5    64.8
  5108.5    64.9  5253.9    66.3  5768.4    66.9  6608.4    68.7
#Mann= 6 , 1 , 0
  2983.2      .2       0  2983.2      .1       0  3483.3     .14       0
  4168.5      .1       0  4978.1     .04       0  5023.5      .1       0
#XS Ineff= 2 , 0
       0    4173    66.7               0
Permanent Ineff=
       F       F
Bank Sta=4978.1,5023.5
XS Rating Curve= 0
Exp/Cntr=.3,.1

Type RM Length L Ch R = 1 ,3033.3  ,453.2,447.6,333
BEGIN DESCRIPTION:
Cross Section 3033.3
END DESCRIPTION:
XS GIS Cut Line= 6
      3124113.46     13900111.83      3124954.85     13899786.94
      3125358.06     13899660.63      3125858.45     13899048.52
       3126098.4     13898154.13      3126125.56     13897955.98
#Sta/Elev= 30
  3105.6      67  3145.6    65.9  3173.6   65.89  3852.3   66.05  3915.6    66.1
  4087.5    65.2  4417.5    65.6  4610.1    64.6  4810.1    64.1  4870.1    64.7
  4937.9   64.47  4971.5   64.02  4988.2   58.68    4997   53.43  4997.8   51.28
  5001.8   51.94  5002.9   53.42  5004.1   55.47  5029.9   63.75  5120.1    64.7
  5300.7      65  5570.7    66.3  5640.7    66.1  5800.7    67.6  5960.7    66.5
  6010.7    66.8  6070.7    66.7  6120.7    66.1  6196.7    66.4  6346.7    68.7
#Mann= 5 , 1 , 0
  3105.6      .1       0  3173.6     .14       0  3852.3      .1       0
  4971.5     .04       0  5029.9      .1       0
#XS Ineff= 2 , 0
       0    3910    66.4               0
Permanent Ineff=
       F       F
Bank Sta=4971.5,5029.9
XS Rating Curve= 0
Exp/Cntr=.3,.1

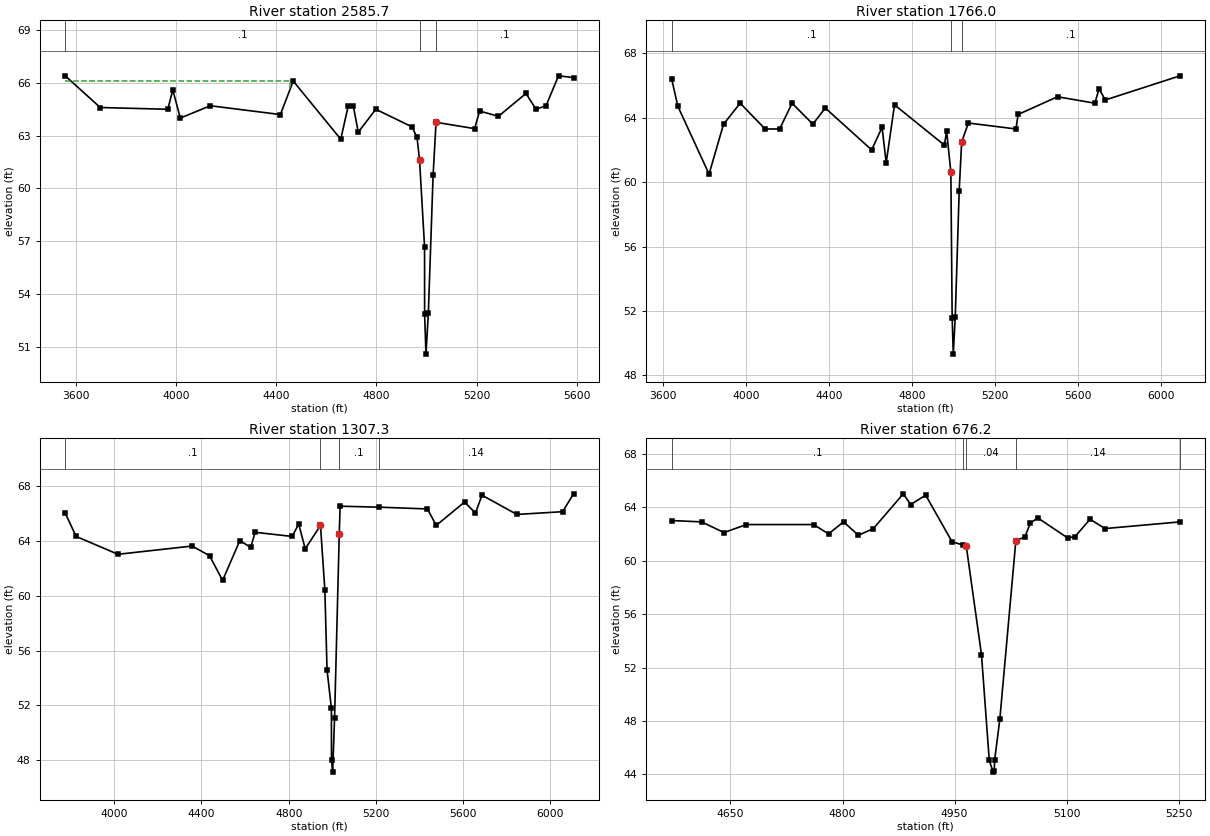
Type RM Length L Ch R = 1 ,2585.7  ,863.1,819.7,752.5
BEGIN DESCRIPTION:
Cross Section 2585.7-Interpolated
END DESCRIPTION:
XS GIS Cut Line= 5
       3124914.4     13900143.49      3125766.13     13899819.38
        3126064.     13899575.66      3126127.19     13899205.58
      3126224.95     13898859.13
#Sta/Elev= 30
  3556.1    66.4  3696.1    64.6  3966.1    64.5  3986.1    65.6  4016.1      64
  4136.1    64.7  4416.1    64.2  4467.4    66.1  4657.4    62.8  4687.4    64.7
  4707.4    64.7  4727.4    63.2  4797.4    64.5  4942.3    63.5  4962.3    62.9
  4972.3    61.6  4992.3    56.7  4992.5   52.86  4997.9   50.59  5007.4   52.91
  5026.4   60.74  5038.2   63.76  5192.3    63.4  5212.3    64.4  5287.7    64.1
  5397.7    65.4  5437.7    64.5  5477.7    64.7  5527.7    66.4  5587.7    66.3
#Mann= 3 , 1 , 0
  3556.1      .1       0  4972.3     .04       0  5038.2      .1       0
#XS Ineff= 2 , 0
       0  4456.1    66.1               0
Permanent Ineff=
       F       F
Bank Sta=4972.3,5038.2
XS Rating Curve= 0
Exp/Cntr=.3,.1

Type RM Length L Ch R = 1 ,1766.0  ,534.3,458.7,447.9
BEGIN DESCRIPTION:
Cross Section 1766.0
END DESCRIPTION:
XS GIS Cut Line= 5
      3125793.21     13900054.06      3126632.66     13899720.09
      3126860.14     13899349.82      3126873.78     13899250.13
      3127126.76     13898272.35
#Sta/Elev= 30
  3641.4    66.4  3671.4    64.7  3821.4    60.5  3891.4    63.6  3971.4    64.9
  4091.4    63.3  4161.4    63.3  4221.4    64.9  4321.4    63.6  4381.4    64.6
  4604.8      62  4654.8    63.4  4674.8    61.2  4714.8    64.8  4954.8    62.3
    4966   63.15  4986.2   60.63  4992.5   51.59  4997.9   49.32  5007.4   51.64
  5026.4   59.47  5038.2   62.49  5070.5   63.67    5300    63.3    5310    64.2
    5500    65.3    5680    64.9    5700    65.8    5730    65.1    6090    66.6
#Mann= 3 , 1 , 0
  3641.4      .1       0  4986.2     .04       0  5038.2      .1       0
#XS Ineff= 2 , 0
       0  4221.4    64.9               0
Permanent Ineff=
       F       F
Bank Sta=4986.2,5038.2
XS Rating Curve= 0
Exp/Cntr=.3,.1

Type RM Length L Ch R = 1 ,1307.3  ,511.8,631.1,756
BEGIN DESCRIPTION:
Cross Section 1307.3-Interpolated
END DESCRIPTION:
XS GIS Cut Line= 5
      3126349.67      13899907.4       3126578.5      13899828.4
       3127056.9     13899602.74      3127300.61      13899142.4
      3127745.08     13898202.17
#Sta/Elev= 30
  3774.8      66  3824.8    64.3  4016.9      63  4356.9    63.6  4436.9    62.9
  4496.9    61.1  4575.9      64  4625.9    63.5  4645.9    64.6  4815.9    64.3
  4845.9    65.2  4875.9    63.4  4945.9    65.1  4965.9    60.4  4975.9    54.6
  4995.9    51.8  4996.4   48.03  5001.6   47.15  5010.5   51.09    5032   64.48
  5035.9    66.5  5212.2   66.43  5436.7    66.3  5476.7    65.1  5606.7    66.8
  5656.7      66  5686.7    67.3  5846.7    65.9  6056.7    66.1  6106.7    67.4
#Mann= 4 , 1 , 0
  3774.8      .1       0  4945.9     .04       0    5032      .1       0
  5212.2     .14       0
#XS Ineff= 2 , 0
       0  4945.9    65.1               0
Permanent Ineff=
       F       F
Bank Sta=4945.9,5032
XS Rating Curve= 0
Exp/Cntr=.3,.1

Type RM Length L Ch R = 1 ,676.2   ,0,0,0
BEGIN DESCRIPTION:
Cross Section 676.2
END DESCRIPTION:
XS GIS Cut Line= 2
      3126941.81     13899803.95      3127621.92     13899784.51
#Sta/Elev= 30
  4571.3      63  4611.3    62.9  4641.3    62.1  4671.3    62.7  4761.3    62.7
  4781.3      62  4801.3    62.9  4821.3    61.9  4841.3    62.4  4881.3      65
  4891.3    64.2  4911.3    64.9  4946.6   61.41  4961.2   61.17  4965.6    61.1
    4986   52.95  4996.4   45.05  5001.6   44.17    5003   44.24  5003.6   45.07
  5010.5   48.11    5032    61.5  5044.1   61.77  5051.3    62.8  5061.3    63.2
  5101.3    61.7  5111.3    61.8  5131.3    63.1  5151.3    62.4  5251.7    62.9
#Mann= 5 , 1 , 0
  4571.3      .1       0  4961.2     .14       0  4965.6     .04       0
    5032     .14       0  5251.7      .2       0
Bank Sta=4965.6,5032
XS Rating Curve= 0
Exp/Cntr=.3,.1

Chan Stop Cuts=-1